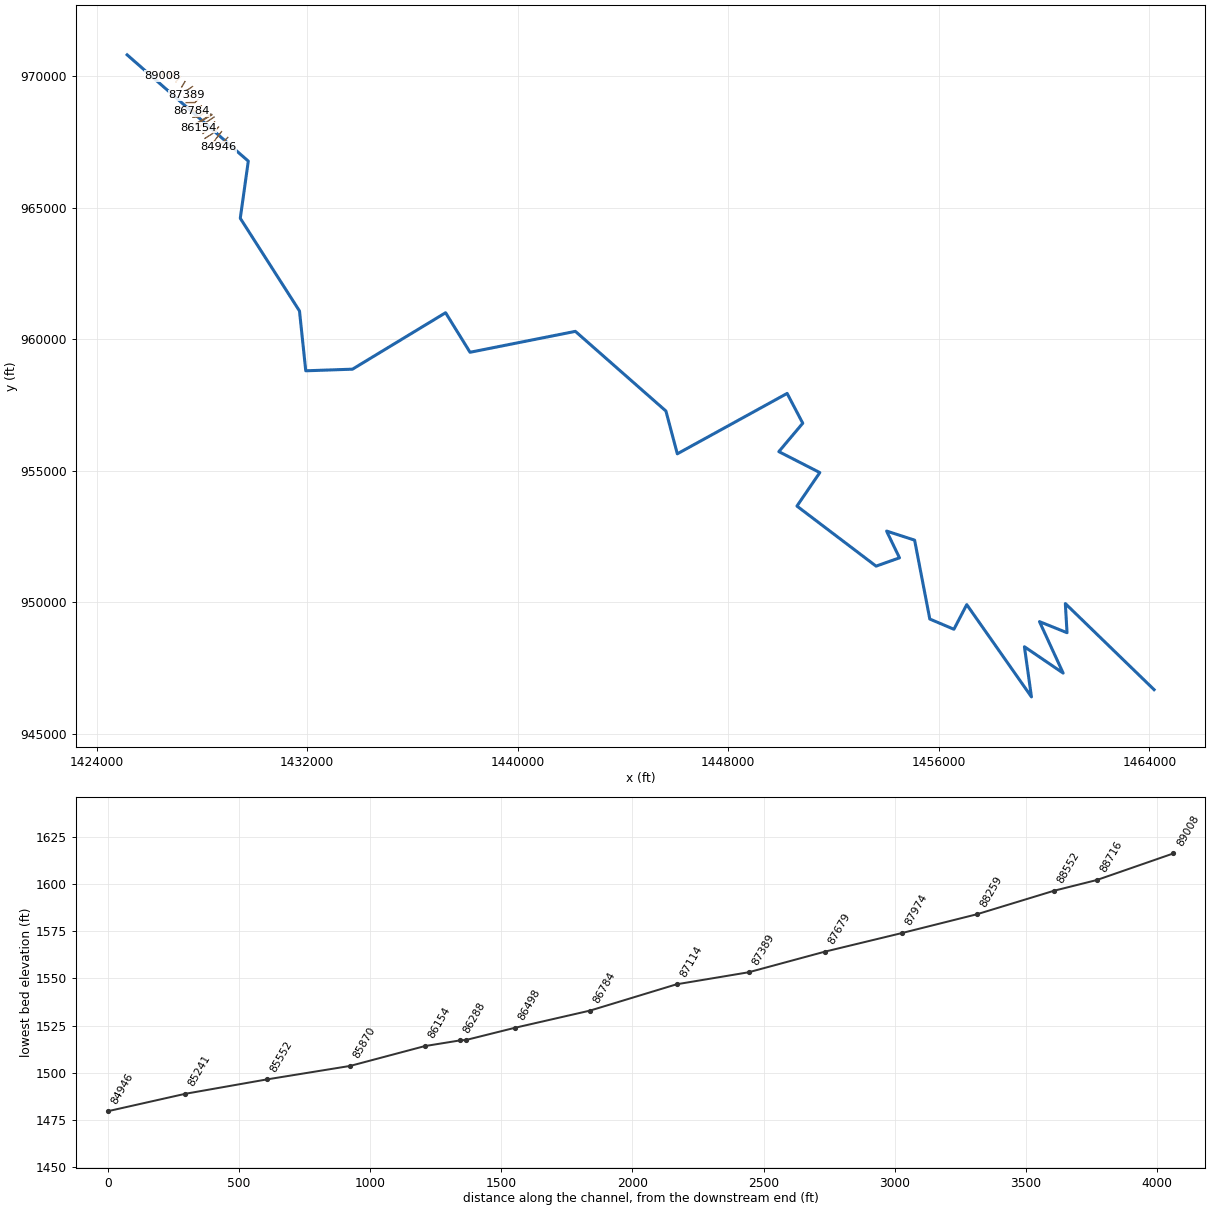
--- South Fork.prj (project) ---

Proj Title=South Fork Limited Detail Study
Current Plan=p01
Default Exp/Contr=0.3,0.1
English Units
Geom File=g01
Flow File=f01
Plan File=p01
Y Axis Title=Elevation
X Axis Title(PF)=Main Channel Distance
X Axis Title(XS)=Station
BEGIN DESCRIPTION:
South Fork
END DESCRIPTION:
DSS Export Rating Curves= 0
DSS Export Rating Curve Sorted= 0
DSS Export Volume Flow Curves= 0
DXF OffsetX= 0
DXF OffsetY= 0
DXF ScaleX= 1
DXF ScaleY= 10

--- South Fork.p01 (plan) ---

Plan Title=Floodway Run
Program Version=3.12
Short Identifier=Floodway
Geom File=g01
Flow File=f01
Subcritical Flow
K Sum by GR= 0
Std Step Tol= 0.01
Critical Tol= 0.01
Num of Std Step Trials= 20
Max Error Tol= 0.3
Flow Tol Ratio= 0.001
Split Flow NTrial= 30
Split Flow Tol= 0.02
Split Flow Ratio= 0.02
Log Output Level= 0
Friction Slope Method= 1
Unsteady Friction Slope Method= 2
Unsteady Bridges Friction Slope Method= 1
Parabolic Critical Depth
Global Vel Dist= 0 , 0 , 0
Global Log Level= 0
CheckData=True
Encroach Param=-1 ,0,0, 2
Encroach River=South Fork
Encroach Reach=Reach-1
Encroach Node=89008
       1 4961.76  5025.3
Encroach Node=88716
       1 4971.21 5046.24
Encroach Node=88552
       1 4974.43 5055.31
Encroach Node=88259
       1    4974 5020.39
Encroach Node=87974
       1    4954 5016.45
Encroach Node=87679
       1 4991.08 5048.43
Encroach Node=87389
       1 4970.69 5019.72
Encroach Node=87114
       1 4934.45  5027.8
Encroach Node=86784
       1    4952  5027.8
Encroach Node=86498
       1 4902.38 5046.92
Encroach Node=86312
       1 4987.28  5012.5
Encroach Node=86288
       1    4975    5010
Encroach Node=86154
       1 4971.12    5080
Encroach Node=85870
       1 4983.34 5157.28
Encroach Node=85552
       1 4935.71 5076.61
Encroach Node=85241
       1 4942.64 5070.88
Encroach Node=84946
       1 4910.33 5079.56
Encroach Node=84694
       1    4900    5090
Encroach Node=84377
       1 4855.72    5087
Encroach Node=84017
       1    4950 5013.75
Encroach Node=83640
       1 4984.02 5020.15
Encroach Node=83203
       1 4988.63    5060
Encroach Node=82885
       1  4969.2 5041.28
Encroach Node=82618
       1    4959    5069
Encroach Node=82415
       1 4924.07 5153.85
Encroach Node=82380
       1 4924.07 5153.85
Encroach Node=82065
       1 4978.91  5202.1
Encroach Node=81769
       1 4982.36 5124.71
Encroach Node=81534
       1    4940    5030
Encroach Node=81234
       1 4957.45 5012.32
Encroach Node=80994
       1  4907.8 5025.42
Encroach Node=80745
       1  4987.3 5024.49
Encroach Node=80517
       1    4905    5015
Encroach Node=80485
       1    4830    5021
Encroach Node=80194
       1 4985.96  5017.6
Encroach Node=79902
       1 4973.68    5028
Encroach Node=79861
       1    4945    5072
Encroach Node=79548
       1    4940    5014
Encroach Node=79240
       1    4940 5014.02
Encroach Node=78962
       1    4978    5020
Encroach Node=78651
       1    4940    5050
Encroach Node=78351
       1    4920    5090
Encroach Node=78071
       1    4930    5023
Encroach Node=77739
       1    4940    5015
Encroach Node=77416
       1 4979.64 5010.44
Encroach Node=77135
       1 4960.18 5010.91
Encroach Node=76835
       1 4957.31 5014.15
Encroach Node=76518
       1 4983.14 5014.96
Encroach Node=76435
       1    4981    5019
Encroach Node=76408
       1    4978  5031.8
Encroach Node=76113
       1 4941.37 5020.72
Encroach Node=75896
       1 4910.56  5009.6
Encroach Node=75606
       1 4979.43  5035.7
Encroach Node=75337
       1    4950 5011.15
Encroach Node=75037
       1  4982.3    5050
Encroach Node=74593
       1 4975.22 5019.03
Encroach Node=74506
       1    4961    5022
Encroach Node=74391
       1 4988.21    5041
Encroach Node=74137
       1    4900    5061
Encroach Node=73870
       1    4875    5081
Encroach Node=73483
       1    4862  5018.2
Encroach Node=73175
       1    4880    5020
Encroach Node=72894
       1 4884.87  5013.3
Encroach Node=72614
       1    4945 5025.92
Encroach Node=72295
       1  4966.7 5025.73
Encroach Node=72037
       1 4977.18 5023.19
Encroach Node=71745
       1 4956.87    5075
Encroach Node=71398
       1 4967.02    5050
Encroach Node=71007
       1 4941.32  5029.3
Encroach Node=70681
       1 4974.73    5114
Encroach Node=70493
       1 4959.45 5044.32
Encroach Node=70337
       1    4986    5016
Encroach Node=70174
       1  4980.2    5030
Encroach Node=69895
       1 4945.45  5011.2
Encroach Node=69629
       1 4925.75    5050
Encroach Node=69368
       1 4822.65  5006.9
Encroach Node=68976
       1 4833.79 5046.42
Encroach Node=68682
       1 4986.17 5175.98
Encroach Node=68362
       1 4980.31    5187
Encroach Node=68083
       1 4881.85 5011.65
Encroach Node=67785
       1 4857.14    5020
Encroach Node=67529
       1    4850    5013
Encroach Node=67146
       1    4800  5013.9
Encroach Node=66798
       1 4904.09 5059.04
Encroach Node=66593
       1 4967.05 5145.11
Encroach Node=66364
       1 4915.71  5142.1
Encroach Node=66100
       1    4890    5035
Encroach Node=66011
       1    4925  5147.9
Encroach Node=65420
       1    4977    5160
Encroach Node=65085
       1    4950 5167.28
Encroach Node=64820
       1 4957.98    5200
Encroach Node=64607
       1 4982.77    5200
Encroach Node=64192
       1  4985.2  5168.9
Encroach Node=63958
       1 4870.87  5038.3
Encroach Node=63547
       1 4832.93    5040
Encroach Node=63323
       1    4830 5015.65
Encroach Node=62841
       1    4916    5030
Encroach Node=62470
       1    4850 5030.81
Encroach Node=62112
       1  4855.9 5036.51
Encroach Node=61729
       1    4797    5024
Encroach Node=61255
       1    4950    5084
Encroach Node=60913
       1 4955.57 5026.01
Encroach Node=60591
       1 4950.49    5020
Encroach Node=60160
       1    4820    5025
Encroach Node=59726
       1 4820.31  5020.6
Encroach Node=59045
       1 4789.37  5024.5
Encroach Node=58739
       1 4796.92  5019.9
Encroach Node=58264
       1    4850  5020.6
Encroach Node=57596
       1    4966    5098
Encroach Node=57171
       1 4909.02 5083.67
Encroach Node=56889
       1  4881.6    5070
Encroach Node=56439
       1    4851  5020.6
Encroach Node=56131
       1    4810 5028.37
Encroach Node=55860
       1  4802.9 5028.84
Encroach Node=54940
       1    4800    5064
Encroach Node=54428
       1    4800    5064
Encroach Node=53983
       1 4926.37    5064
Encroach Node=53526
       1  4920.5    5064
Encroach Node=53163
       1    4900    5026
Encroach Node=52812
       1    4930    5050
Encroach Node=52424
       1    4850    5040
Encroach Node=52070
       1    4790    5060
Encroach Node=51792
       1    4940    5060
Encroach Node=51713
       1    4934    5066
Encroach Node=51177
       1    4940    5039
Encroach Node=50739
       1    4894    5040
Encroach Node=50352
       1 4950.85 5163.66
Encroach Node=49800
       1    4809  5026.5
Encroach Node=48812
       1    4850    5050
Encroach Node=48172
       1    4960    5050
Encroach Node=47652
       1    4940    5041
Encroach Node=47075
       1  4969.7    5030
Encroach Node=46500
       1  4965.1  5034.9
Encroach Node=45837
       1  4974.3  5033.5
Encroach Node=45409
       1  4969.7    5034
Encroach Node=44904
       1 4956.14    5025
Encroach Node=44623
       1    4974    5026
Encroach Node=44565
       1    4974    5026
Encroach Node=43974
       1  4965.2  5034.8
Encroach Node=43452
       1  4969.4  5030.6
Encroach Node=42900
       1  4973.7  5026.3
Encroach Node=42219
       1  4970.9  5029.1
Encroach Node=41887
       1    4978    5050
Encroach Node=41635
       1 4929.24    5100
Encroach Node=41400
       1 4957.15    5150
Encroach Node=41180
       1 4958.76  5027.5
Encroach Node=40927
       1 4967.32 5026.07
Encroach Node=40370
       1    4970    5024
Encroach Node=39960
       1    4970    5037
Encroach Node=39600
       1    4954    5040
Encroach Node=39325
       1    4950 5026.67
Encroach Node=38776
       1    4955    5034
Encroach Node=38343
       1  4968.9  5031.1
Encroach Node=37800
       1  4980.5 5030.76
Encroach Node=37419
       1  4971.8  5028.2
Encroach Node=36271
       1  4973.1  5026.9
Encroach Node=35665
       1  4965.8  5034.2
Encroach Node=35301
       1  4967.3  5032.7
Encroach Node=34938
       1  4967.3 5030.58
Encroach Node=34482
       1  4947.3  5026.9
Encroach Node=34073
       1    4940    5035
Encroach Node=33699
       1    4940    5040
Encroach Node=33147
       1    4940    5040
Encroach Node=32682
       1    4940  5028.8
Encroach Node=32280
       1    4960    5025
Encroach Node=31716
       1  4972.5  5032.5
Encroach Node=31320
       1    4966    5036
Encroach Node=30826
       1    4960  5024.3
Encroach Node=30058
       1  4967.6  5032.4
Encroach Node=29420
       1  4969.4 5028.98
Encroach Node=29195
       1  4956.5 5045.37
Encroach Node=29095
       1 4953.55  5051.5
Encroach Node=28490
       1  4976.9    5050
Encroach Node=28011
       1  4972.8    5023
Encroach Node=27548
       1  4971.1  5028.9
Encroach Node=26954
       1    4972  5028.9
Encroach Node=26495
       1  4974.5 5040.11
Encroach Node=26082
       1  4971.1    5033
Encroach Node=25759
       1 4968.63 5046.82
Encroach Node=25303
       1    4969  5032.4
Encroach Node=24900
       1    4972    5040
Encroach Node=24342
       1  4974.2  5025.8
Encroach Node=23931
       1    4971  5022.3
Encroach Node=23234
       1    4976 5033.67
Encroach Node=22800
       1    4969  5022.3
Encroach Node=22109
       1  4974.2    5032
Encroach Node=21637
       1  4969.1    5031
Encroach Node=21143
       1  4965.6    5040
Encroach Node=20732
       1  4972.5    5040
Encroach Node=20571
       1    4975  5022.3
Encroach Node=20022
       1    4965 5025.37
Encroach Node=19371
       1    4967    5024
Encroach Node=18807
       1  4972.4    5035
Encroach Node=18321
       1  4965.4  5034.6
Encroach Node=17764
       1    4955    5045
Encroach Node=17070
       1  4935.1    5059
Encroach Node=17020
       1  4935.1 5053.86
Encroach Node=16262
       1    4900    5050
Encroach Node=15653
       1    4925    5100
Encroach Node=14934
       1  4967.1    5130
Encroach Node=14151
       1    4885  5063.6
Encroach Node=13651
       1 4765.55  5037.6
Encroach Node=13018
       1    4785    5032
Encroach Node=12340
       1    4900    5076
Encroach Node=11732
       1    4933 5064.19
Encroach Node=11196
       1 4958.09 5047.56
Encroach Node=10655
       1    4958    5050
Encroach Node=10138
       1 4964.04 5032.51
Encroach Node=9722
       1  4971.4 5041.01
Encroach Node=9456
       1  4973.7    5041
Encroach Node=9040
       1  4965.9  5034.1
Encroach Node=8821
       1    4955  5021.4
Encroach Node=8200
       1  4971.7  5028.3
Encroach Node=7500
       1    4965  5028.3
Encroach Node=7200
       1  4971.7  5028.3
Encroach Node=6882
       1  4969.8    5025
Encroach Node=6600
       1  4973.7  5026.3
Encroach Node=6265
       1  4971.7  5028.3
Encroach Node=5964
       1  4971.7  5028.3
Encroach Node=5680
       1    4955  5024.4
Encroach Node=5400
       1  4969.8 5026.84
Encroach Node=5100
       1  4971.7    5025
Encroach Node=4873
       1  4975.6  5027.3
Encroach Node=4491
       1    4965  5026.3
Encroach Node=4218
       1  4971.7  5028.3
Encroach Node=3893
       1    4966  5024.4
Encroach Node=3645
       1    4970    5030
Encroach Node=3375
       1    4963    5026
Encroach Node=2987
       1 4963.68  5032.2
Encroach Node=2691
       1    4965    5033
Encroach Node=2372
       1  4975.6    5026
Encroach Node=2070
       1    4960    5036
Encroach Node=1789
       1    4970 5031.68
Encroach Node=1473
       1    4973  5021.5
Encroach Node=1190
       1  4973.7  5026.3
Encroach Node=907
       1  4973.7  5026.3
Encroach Node=643
       1  4971.7  5028.3
BEGIN DESCRIPTION:
Floodway Run
END DESCRIPTION:
Computation Interval=1HOUR
Output Interval=1HOUR
Run HTab= 0
Run UNet= 0
Run PostProcess= 0
UNET Theta= 1
UNET Theta Warmup= 1
UNET ZTol= 0.02
UNET ZSATol= 0.05
UNET MxIter= 20
UNET MaxInSteps= 0
UNET DtIC= 0
UNET DtMin= 0
UNET MaxCRTS= 20
UNET WFStab= 2
UNET SFStab= 1
UNET WFX= 1
UNET SFX= 1
UNET DSS MLevel= 4
UNET DZMax Abort= 100
UNET Convert EG Bridges=-1
UNET Use Existing IB Tables=-1
UNET Froude Reduction=False
UNET Froude Limit= 1
UNET Froude Power= 10
Instantaneous Interval=1HOUR
Write IC File= 0
Echo Input=False
Echo Output=False
Write Detailed= 0
Detailed Automatic Start=False, 10

--- South Fork.f01 (steady flow) ---

Flow Title=Floodway
Number of Profiles=2
Profile Names=100-year,100-FW
River Rch & RM= South Fork,Reach-1,89008
     746     746
River Rch & RM= South Fork,Reach-1,88259
     777     777
River Rch & RM= South Fork,Reach-1,86784
     889     889
River Rch & RM= South Fork,Reach-1,84017
    1329    1329
River Rch & RM= South Fork,Reach-1,81534
    1421    1421
River Rch & RM= South Fork,Reach-1,78071
    1559    1559
River Rch & RM= South Fork,Reach-1,73483
    1835    1835
River Rch & RM= South Fork,Reach-1,71398
    1886    1886
River Rch & RM= South Fork,Reach-1,69368
    1931    1931
River Rch & RM= South Fork,Reach-1,67785
    2053    2053
River Rch & RM= South Fork,Reach-1,65085
    2135    2135
River Rch & RM= South Fork,Reach-1,60160
    3238    3238
River Rch & RM= South Fork,Reach-1,56439
    3312    3312
River Rch & RM= South Fork,Reach-1,51177
    3518    3518
River Rch & RM= South Fork,Reach-1,49800
    3591    3591
River Rch & RM= South Fork,Reach-1,44904
    4326    4326
River Rch & RM= South Fork,Reach-1,39960
    4404    4404
River Rch & RM= South Fork,Reach-1,36271
    4444    4444
River Rch & RM= South Fork,Reach-1,33147
    4812    4812
River Rch & RM= South Fork,Reach-1,29420
    5046    5046
River Rch & RM= South Fork,Reach-1,24342
    5116    5116
River Rch & RM= South Fork,Reach-1,18807
    5131    5131
River Rch & RM= South Fork,Reach-1,17070
    5551    5551
River Rch & RM= South Fork,Reach-1,9456
    5587    5587
Boundary for River Rch & Prof#=South Fork,Reach-1,1
Up Type=0
Dn Type=3
Dn Slope=0.0024
Boundary for River Rch & Prof#=South Fork,Reach-1,2
Up Type=0
Dn Type=3
Dn Slope=0.0024

--- South Fork.g01 (geometry) ---

Geom Title=Existing Conditions

River Reach=South Fork,Reach-1
Reach XY= 30
      1425158.13       970816.00      1429761.63       966774.78
      1429457.05       964602.44      1431707.05       961078.13
      1431944.90       958803.83      1433720.47       958865.48
      1437258.26       961011.29      1438187.08       959507.82
      1442189.69       960302.96      1445630.66       957273.45
      1446062.95       955647.58      1450235.70       957943.59
      1450829.45       956809.90      1449920.28       955731.08
      1451477.01       954934.04      1450608.09       953660.60
      1453615.04       951377.61      1454504.79       951692.72
      1454014.34       952710.95      1455079.45       952365.46
      1455656.60       949366.69      1456572.85       948977.26
      1457060.13       949914.83      1459518.90       946407.02
      1459251.54       948313.27      1460723.76       947310.67
      1459824.02       949268.13      1460870.90       948846.26
      1460806.66       949953.90      1464178.00       946681.75

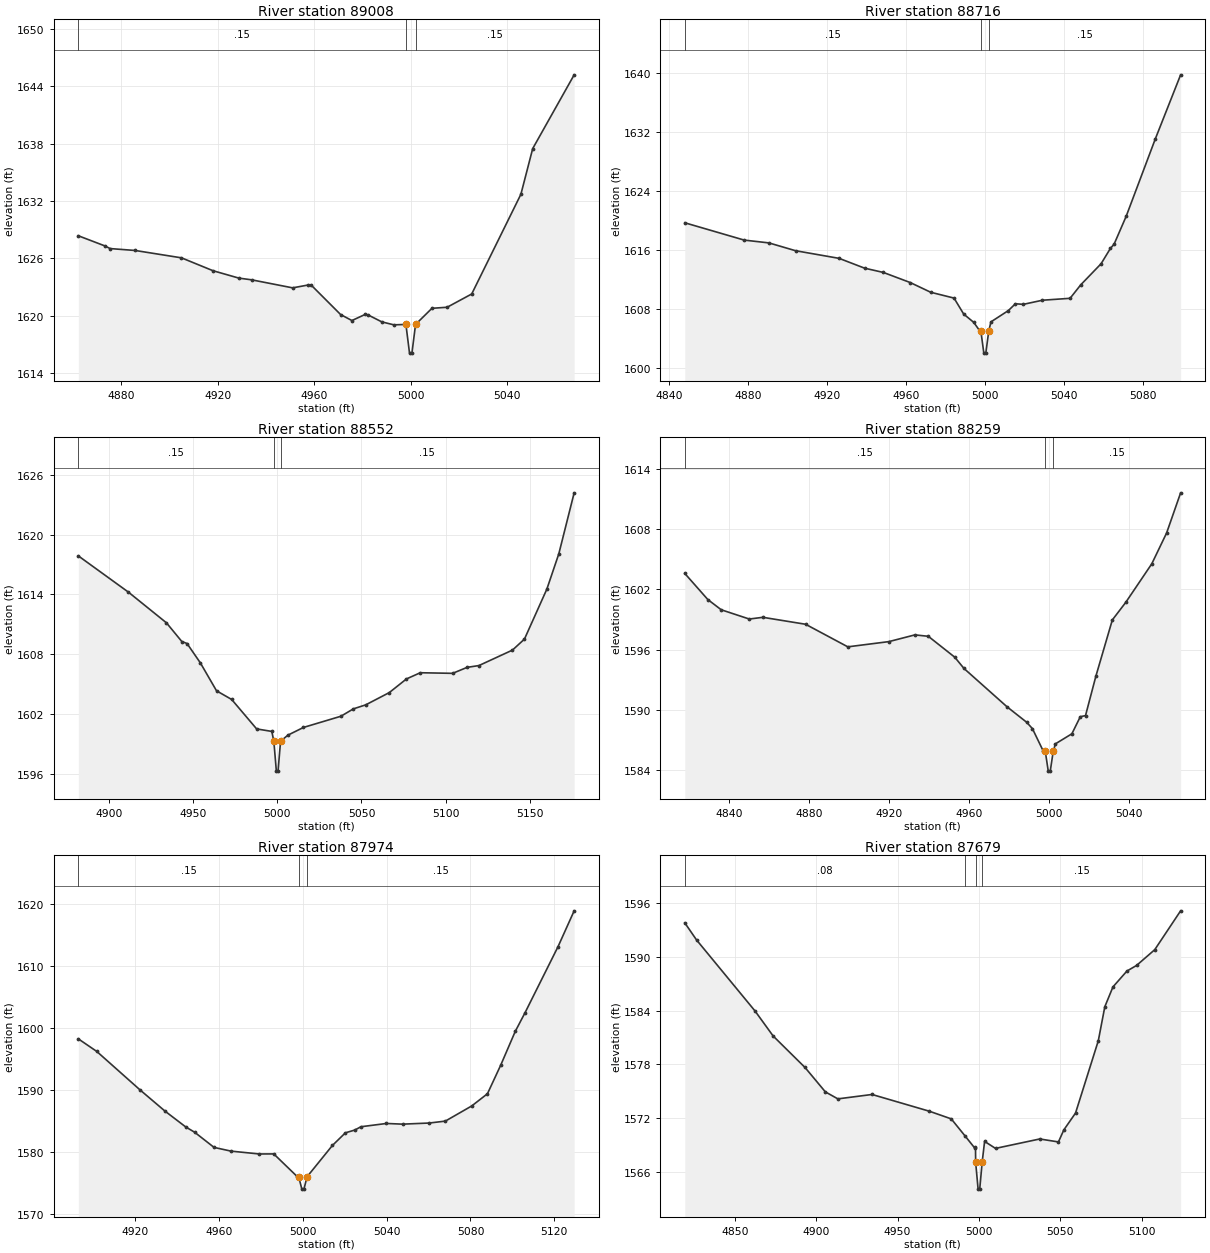
Type RM Length L Ch R = 1,89008,292,292,292
BEGIN DESCRIPTION:
South Fork 297.0
END DESCRIPTION:
XS GIS Cut Line= 4
      1426500.14       970210.90      1426525.42       970149.26
      1426514.54       970085.89      1426498.99       970012.74
#Sta/Elev= 27
  4862.1 1628.35  4873.1 1627.29  4875.3 1627.01  4885.7 1626.81  4904.9 1626.04
  4918.0 1624.69  4928.7 1623.92  4934.0 1623.74  4951.0 1622.90  4957.5 1623.20
  4958.7 1623.19  4970.9 1620.11  4975.6 1619.48  4981.1 1620.12  4982.2 1620.08
  4988.0 1619.34  4993.0 1619.03  4998.0 1619.07  4999.5 1616.07  5000.5 1616.07
  5002.0 1619.07  5008.8 1620.76  5015.1 1620.87  5025.3 1622.26  5045.7 1632.69
  5050.6 1637.47  5067.8 1645.19
#Mann=3,-1,0
  4862.1    0.15       0  4998.0    0.05       0  5002.0    0.15       0
Bank Sta=4998,5002
XS Rating Curve= 0
Exp/Cntr=0.3,0.1

Type RM Length L Ch R = 1,88716,164,164,164
BEGIN DESCRIPTION:
South Fork 296.0
END DESCRIPTION:
XS GIS Cut Line= 4
      1426723.88       970164.33      1426755.14       970091.40
      1426803.75       969980.29      1426784.67       969933.45
#Sta/Elev= 30
  4848.0 1619.69  4878.1 1617.34  4890.6 1616.96  4904.1 1615.90  4926.2 1614.86
  4939.1 1613.53  4948.6 1612.95  4962.2 1611.58  4972.6 1610.26  4984.4 1609.47
  4989.3 1607.30  4994.4 1606.17  4997.6 1604.96  4998.0 1605.00  4999.5 1602.00
  5000.5 1602.00  5002.0 1605.00  5003.1 1606.24  5011.9 1607.77  5015.5 1608.70
  5019.5 1608.62  5029.2 1609.18  5043.2 1609.44  5048.6 1611.27  5058.9 1614.13
  5063.6 1616.20  5065.5 1616.79  5071.6 1620.56  5086.4 1631.09  5099.2 1639.77
#Mann=3,-1,0
  4848.0    0.15       0  4998.0    0.05       0  5002.0    0.15       0
Bank Sta=4998,5002
XS Rating Curve= 0
Exp/Cntr=0.3,0.1

Type RM Length L Ch R = 1,88552,293,293,293
BEGIN DESCRIPTION:
South Fork 295.0
END DESCRIPTION:
XS GIS Cut Line= 3
      1426940.05       970202.56      1426923.39       970047.69
      1426843.02       969934.98
#Sta/Elev= 30
  4882.0 1617.86  4911.7 1614.23  4934.3 1611.15  4943.4 1609.28  4946.5 1609.08
  4954.4 1607.14  4964.0 1604.34  4973.0 1603.47  4987.8 1600.52  4996.8 1600.27
  4998.0 1599.29  4999.5 1596.29  5000.5 1596.29  5002.0 1599.29  5006.4 1599.90
  5015.6 1600.67  5037.8 1601.79  5045.2 1602.53  5052.5 1602.93  5066.5 1604.16
  5076.7 1605.53  5084.9 1606.15  5104.1 1606.09  5112.7 1606.69  5119.7 1606.87
  5139.6 1608.42  5146.7 1609.52  5160.0 1614.53  5167.1 1618.07  5176.2 1624.18
#Mann=3,-1,0
  4882.0    0.15       0  4998.0    0.05       0  5002.0    0.15       0
Bank Sta=4998,5002
XS Rating Curve= 0
Exp/Cntr=0.3,0.1

Type RM Length L Ch R = 1,88259,285,285,285
BEGIN DESCRIPTION:
South Fork 294.0
END DESCRIPTION:
XS GIS Cut Line= 4
      1427175.31       969987.27      1427116.89       969915.51
      1427062.43       969851.82      1427013.80       969799.71
#Sta/Elev= 30
  4818.0 1603.58  4829.5 1600.98  4836.2 1599.96  4850.2 1599.04  4857.0 1599.21
  4878.3 1598.52  4899.4 1596.27  4919.9 1596.79  4932.9 1597.46  4939.6 1597.32
  4952.8 1595.24  4957.4 1594.12  4978.9 1590.30  4988.7 1588.76  4991.6 1588.12
  4997.0 1585.89  4998.0 1585.89  4999.5 1583.89  5000.5 1583.89  5002.0 1585.89
  5003.1 1586.61  5011.3 1587.61  5015.5 1589.31  5018.1 1589.42  5023.3 1593.36
  5031.5 1598.95  5038.2 1600.70  5051.2 1604.54  5058.6 1607.61  5065.6 1611.61
#Mann=3,-1,0
  4818.0    0.15       0  4998.0    0.05       0  5002.0    0.15       0
Bank Sta=4998,5002
XS Rating Curve= 0
Exp/Cntr=0.3,0.1

Type RM Length L Ch R = 1,87974,295,295,295
BEGIN DESCRIPTION:
South Fork 293.0
END DESCRIPTION:
XS GIS Cut Line= 3
      1427354.10       969799.73      1427302.02       969711.19
      1427232.58       969596.62
#Sta/Elev= 30
  4892.8 1598.26  4901.6 1596.23  4922.3 1590.00  4934.2 1586.58  4944.1 1584.02
  4948.3 1583.18  4957.6 1580.72  4965.7 1580.12  4979.2 1579.66  4986.1 1579.67
  4997.1 1576.07  4998.0 1575.98  4999.5 1573.98  5000.5 1573.98  5002.0 1575.98
  5014.1 1581.04  5020.3 1583.08  5024.8 1583.53  5027.7 1584.06  5039.9 1584.59
  5047.6 1584.48  5060.3 1584.66  5068.0 1584.97  5080.6 1587.42  5088.1 1589.39
  5094.4 1593.98  5101.4 1599.48  5106.1 1602.52  5121.8 1613.16  5129.5 1618.95
#Mann=3,-1,0
  4892.8    0.15       0  4998.0    0.05       0  5002.0    0.15       0
Bank Sta=4998,5002
XS Rating Curve= 0
Exp/Cntr=0.3,0.1

Type RM Length L Ch R = 1,87679,290,290,290
BEGIN DESCRIPTION:
South Fork 292.0
END DESCRIPTION:
XS GIS Cut Line= 4
      1427640.58       969610.51      1427492.99       969509.80
      1427456.53       969480.29      1427380.11       969459.45
#Sta/Elev= 30
  4819.2 1593.77  4826.4 1591.87  4862.4 1583.94  4873.5 1581.16  4893.1 1577.65
  4905.6 1574.93  4913.3 1574.15  4934.3 1574.64  4969.6 1572.77  4983.0 1571.92
  4991.7 1569.97  4997.3 1568.70  4997.9 1568.78  4998.0 1567.09  4999.5 1564.09
  5000.5 1564.09  5002.0 1567.09  5003.5 1569.41  5010.2 1568.63  5037.4 1569.68
  5048.9 1569.35  5052.2 1570.69  5059.4 1572.57  5073.4 1580.63  5077.4 1584.42
  5082.4 1586.63  5091.0 1588.40  5096.9 1589.02  5108.1 1590.78  5124.0 1595.11
#Mann=4,-1,0
  4819.2    0.08       0  4991.7    0.15       0  4998.0    0.05       0
  5002.0    0.15       0
Bank Sta=4998,5002
XS Rating Curve= 0
Exp/Cntr=0.3,0.1

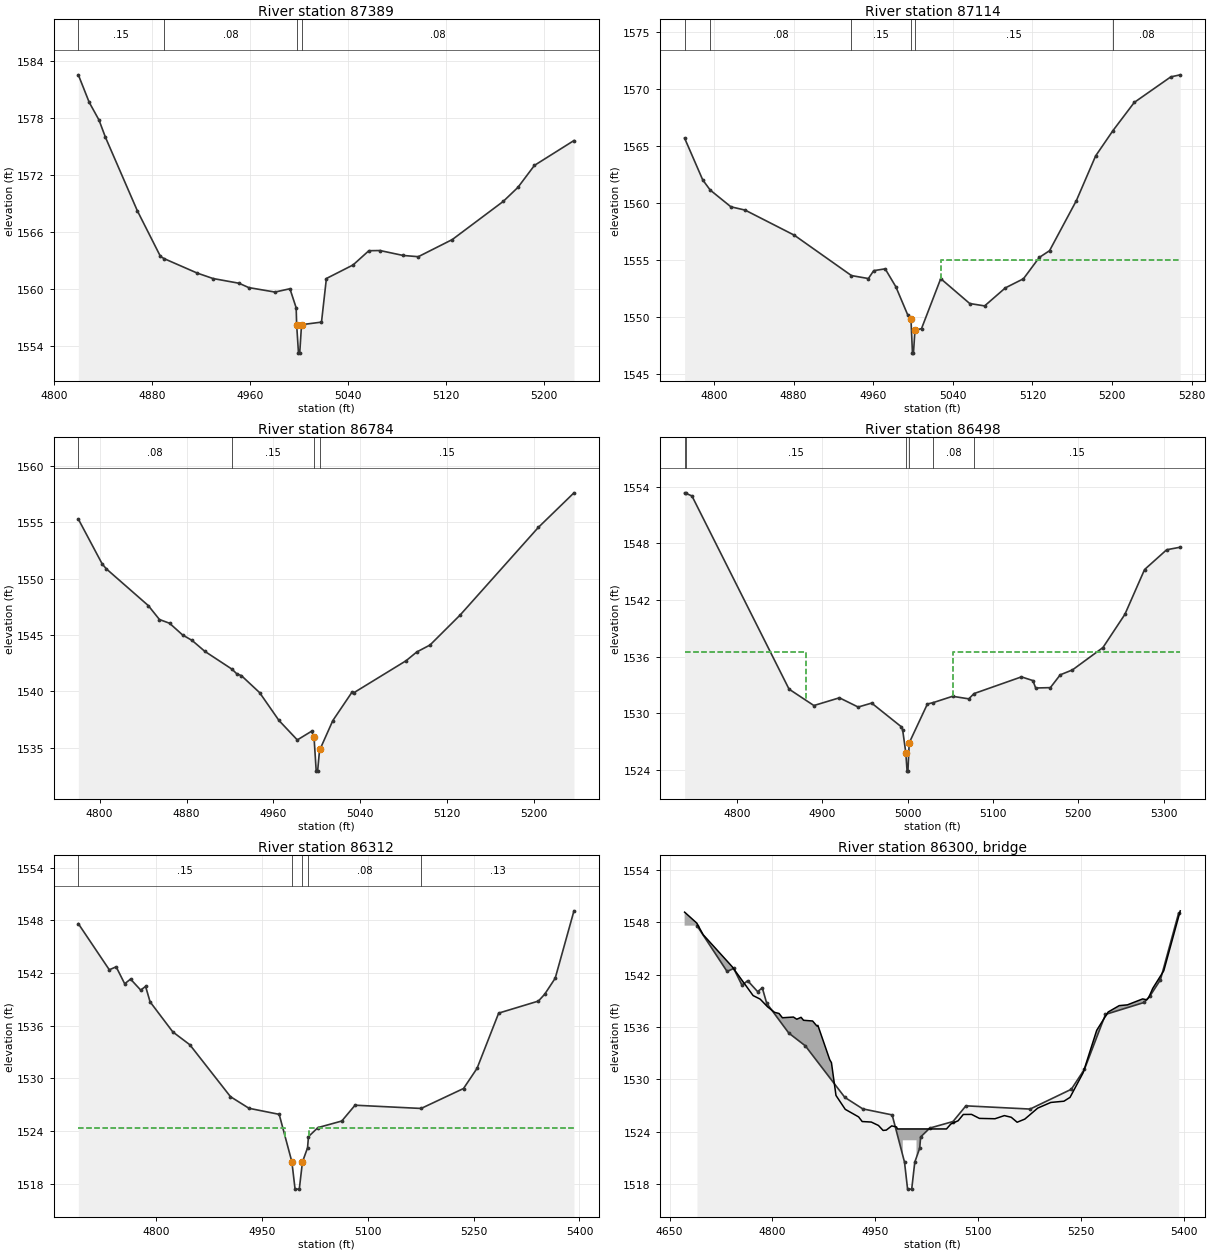
Type RM Length L Ch R = 1,87389,275,275,275
BEGIN DESCRIPTION:
South Fork 291.0
END DESCRIPTION:
XS GIS Cut Line= 3
      1427793.35       969344.88      1427543.34       969228.55
      1427423.58       969277.15
#Sta/Elev= 30
  4819.6 1582.56  4828.5 1579.66  4836.5 1577.79  4841.8 1575.96  4867.8 1568.23
  4886.7 1563.41  4889.8 1563.17  4916.8 1561.65  4929.6 1561.08  4950.9 1560.58
  4958.9 1560.12  4980.3 1559.65  4992.5 1560.00  4997.6 1557.99  4998.0 1556.21
  4999.5 1553.21  5000.5 1553.21  5002.0 1556.21  5018.3 1556.48  5022.3 1561.08
  5044.1 1562.51  5057.0 1564.01  5066.1 1564.03  5085.0 1563.51  5097.4 1563.38
  5125.2 1565.19  5166.8 1569.21  5178.8 1570.69  5192.3 1573.01  5224.6 1575.63
#Mann=4,-1,0
  4819.6    0.15       0  4889.8    0.08       0  4998.0    0.05       0
  5002.0    0.08       0
Bank Sta=4998,5002
XS Rating Curve= 0
Exp/Cntr=0.3,0.1

Type RM Length L Ch R = 1,87114,330,330,330
BEGIN DESCRIPTION:
South Fork 290.0
END DESCRIPTION:
XS GIS Cut Line= 3
      1427852.35       969119.17      1427734.31       969004.59
      1427400.98       968997.65
#Sta/Elev= 30
  4770.6 1565.69  4788.8 1562.03  4796.3 1561.14  4817.1 1559.67  4831.4 1559.38
  4880.8 1557.18  4938.2 1553.64  4955.2 1553.38  4960.6 1554.07  4972.1 1554.23
  4982.8 1552.66  4994.7 1550.20  4998.0 1549.84  4999.5 1546.84  5000.5 1546.84
  5002.0 1548.84  5008.6 1548.99  5027.9 1553.37  5057.0 1551.19  5072.0 1550.98
  5092.8 1552.56  5111.0 1553.36  5126.9 1555.23  5137.2 1555.82  5164.2 1560.22
  5183.5 1564.13  5200.9 1566.35  5222.3 1568.82  5259.0 1571.06  5268.5 1571.24
#Mann=6,-1,0
  4770.6    0.15       0  4796.3    0.08       0  4938.2    0.15       0
  4998.0    0.05       0  5002.0    0.15       0  5200.9    0.08       0
#XS Ineff=2,0
       0                 5027.90    0.00 1555.00
Permanent Ineff=
       F       F
Bank Sta=4998,5002
XS Rating Curve= 0
Exp/Cntr=0.3,0.1

Type RM Length L Ch R = 1,86784,286,286,286
BEGIN DESCRIPTION:
South Fork 289.0
END DESCRIPTION:
XS GIS Cut Line= 4
      1427979.08       968874.37      1427808.96       968742.44
      1427744.00       968685.49      1427590.20       968669.52
#Sta/Elev= 30
  4780.4 1555.30  4802.4 1551.31  4806.3 1550.87  4844.8 1547.62  4855.1 1546.38
  4864.4 1546.05  4876.4 1545.01  4885.2 1544.52  4896.8 1543.56  4921.9 1541.97
  4926.5 1541.54  4930.4 1541.41  4947.3 1539.89  4965.1 1537.42  4982.0 1535.69
  4995.1 1536.46  4997.4 1535.92  4999.4 1532.92  5000.7 1532.92  5002.6 1534.92
  5003.2 1534.92  5014.7 1537.41  5032.2 1539.91  5034.2 1539.89  5082.1 1542.72
  5092.0 1543.50  5104.2 1544.12  5132.1 1546.80  5203.9 1554.56  5236.7 1557.63
#Mann=4,-1,0
  4780.4    0.08       0  4921.9    0.15       0  4997.4    0.05       0
  5002.6    0.15       0
Bank Sta=4997.4,5002.6
XS Rating Curve= 0
Exp/Cntr=0.3,0.1

Type RM Length L Ch R = 1,86498,186,186,186
BEGIN DESCRIPTION:
South Fork 288.0
END DESCRIPTION:
XS GIS Cut Line= 4
      1428157.92       968681.67      1427966.95       968521.95
      1427887.78       968461.35      1427656.18       968445.57
#Sta/Elev= 30
  4738.8 1553.37  4740.7 1553.30  4747.4 1553.04  4861.2 1532.54  4890.3 1530.80
  4920.2 1531.62  4942.2 1530.64  4958.0 1531.06  4992.7 1528.55  4994.3 1528.23
  4998.0 1525.80  4999.5 1523.84  5000.5 1523.84  5002.0 1526.84  5023.3 1530.96
  5030.1 1531.11  5052.8 1531.78  5071.8 1531.51  5078.0 1532.07  5133.5 1533.84
  5146.9 1533.45  5150.2 1532.66  5167.4 1532.70  5179.0 1534.06  5193.3 1534.58
  5229.0 1536.95  5254.7 1540.47  5277.8 1545.23  5303.7 1547.33  5319.6 1547.60
#Mann=6,-1,0
  4738.8    0.08       0  4740.7    0.15       0  4998.0    0.05       0
  5002.0    0.15       0  5030.1    0.08       0  5078.0    0.15       0
#XS Ineff=2,0
    0.00 4881.00 1536.50 5052.80    0.00 1536.50
Permanent Ineff=
       F       F
Bank Sta=4998,5002
XS Rating Curve= 0
Exp/Cntr=0.5,0.3

Type RM Length L Ch R = 1,86312,24,24,24
BEGIN DESCRIPTION:
Silver Creek Way US
END DESCRIPTION:
XS GIS Cut Line= 3
      1428339.81       968566.66      1428085.41       968385.37
      1427748.70       968188.75
#Sta/Elev= 30
  4689.9 1547.61  4733.8 1542.36  4743.5 1542.70  4755.6 1540.77  4763.9 1541.30
  4778.3 1540.05  4785.2 1540.47  4791.6 1538.71  4823.8 1535.29  4847.9 1533.83
  4905.5 1527.92  4931.7 1526.60  4974.5 1525.91  4992.5 1520.50  4997.0 1517.40
  5003.0 1517.40  5007.5 1520.50  5014.7 1522.10  5016.0 1523.38  5029.4 1524.40
  5063.2 1525.15  5082.0 1526.95  5175.6 1526.58  5235.7 1528.85  5254.9 1531.15
  5285.5 1537.43  5341.8 1538.80  5350.7 1539.58  5365.6 1541.40  5392.2 1549.07
#Mann=5,-1,0
  4689.9    0.15       0  4992.5    0.05       0  5007.5    0.15       0
  5014.7    0.08       0  5175.6    0.13       0
#XS Ineff=2,0
    0.00 4983.00 1524.30 5017.00    0.00 1524.30
Permanent Ineff=
       F       F
Bank Sta=4992.5,5007.5
XS Rating Curve= 0
Exp/Cntr=0.5,0.3

Type RM Length L Ch R =3,86300,,,
BEGIN DESCRIPTION:
Silver Creek Way TOR
Structure ID: LDS_SFMR_10
Approximate Survey Structure
END DESCRIPTION:
Bridge Culvert--1,0,-1,-1,0
Deck Dist Width WeirC Skew NumUp NumDn MinLoCord MaxHiCord MaxSubmerge Is_Ogee
7,10,3,, 60, 60,,,0.95,0,1,1,,,
  4671.9  4689.7  4698.9  4741.1  4771.8  4782.0  4792.9  4803.1  4809.6  4814.5
  4830.6  4835.4  4841.7  4845.3  4858.5  4864.7  4866.2  4883.5  4886.0  4892.6
  4906.1  4925.6  4930.8  4944.1  4954.5  4961.3  4966.0  4973.8  4980.9  4982.1
  4990.0  4990.0  5010.0  5010.0  5053.7  5060.1  5070.7  5078.2  5090.2  5101.7
  5124.4  5138.1  5148.1  5156.7  5167.9  5186.7  5205.8  5224.9  5233.8  5252.9
  5272.7  5289.4  5305.5  5317.5  5339.7  5345.7  5348.5  5354.4  5370.5  5394.5
 1549.16 1547.90 1546.58 1542.92 1539.59 1539.19 1538.30 1537.67 1537.54 1537.05
 1537.13 1536.88 1537.10 1536.76 1536.68 1536.11 1536.18 1532.24 1531.90 1528.14
 1526.55 1525.68 1525.15 1525.09 1524.70 1524.13 1524.17 1524.65 1524.53 1524.30
 1524.30 1524.30 1524.30 1524.30 1524.30 1524.87 1525.24 1525.96 1525.97 1525.51
 1525.47 1525.83 1525.64 1525.07 1525.43 1526.69 1527.34 1527.48 1527.92 1530.74
 1535.61 1537.71 1538.44 1538.53 1539.21 1539.11 1539.36 1540.42 1542.44 1549.31
 1497.40 1497.40 1497.40 1497.40 1497.40 1497.40 1497.40 1497.40 1497.40 1497.40
 1497.40 1497.40 1497.40 1497.40 1497.40 1497.40 1497.40 1497.40 1497.40 1497.40
 1497.40 1497.40 1497.40 1497.40 1497.40 1497.40 1497.40 1497.40 1497.40 1497.40
 1497.40 1523.00 1523.00 1497.40 1497.40 1497.40 1497.40 1497.40 1497.40 1497.40
 1497.40 1497.40 1497.40 1497.40 1497.40 1497.40 1497.40 1497.40 1497.40 1497.40
 1497.40 1497.40 1497.40 1497.40 1497.40 1497.40 1497.40 1497.40 1497.40 1497.40
  4671.9  4689.7  4698.9  4741.1  4771.8  4782.0  4792.9  4803.1  4809.6  4814.5
  4830.6  4835.4  4841.7  4845.3  4858.5  4864.7  4866.2  4883.5  4886.0  4892.6
  4906.1  4925.6  4930.8  4944.1  4954.5  4961.3  4966.0  4973.8  4980.9  4982.1
  4990.0  4990.0  5010.0  5010.0  5053.7  5060.1  5070.7  5078.2  5090.2  5101.7
  5124.4  5138.1  5148.1  5156.7  5167.9  5186.7  5205.8  5224.9  5233.8  5252.9
  5272.7  5289.4  5305.5  5317.5  5339.7  5345.7  5348.5  5354.4  5370.5  5394.5
 1549.16 1547.90 1546.58 1542.92 1539.59 1539.19 1538.30 1537.67 1537.54 1537.05
 1537.13 1536.88 1537.10 1536.76 1536.68 1536.11 1536.18 1532.24 1531.90 1528.14
 1526.55 1525.68 1525.15 1525.09 1524.70 1524.13 1524.17 1524.65 1524.53 1524.30
 1524.30 1524.30 1524.30 1524.30 1524.30 1524.87 1525.24 1525.96 1525.97 1525.51
 1525.47 1525.83 1525.64 1525.07 1525.43 1526.69 1527.34 1527.48 1527.92 1530.74
 1535.61 1537.71 1538.44 1538.53 1539.21 1539.11 1539.36 1540.42 1542.44 1549.31
 1497.40 1497.40 1497.40 1497.40 1497.40 1497.40 1497.40 1497.40 1497.40 1497.40
 1497.40 1497.40 1497.40 1497.40 1497.40 1497.40 1497.40 1497.40 1497.40 1497.40
 1497.40 1497.40 1497.40 1497.40 1497.40 1497.40 1497.40 1497.40 1497.40 1497.40
 1497.40 1523.00 1523.00 1497.40 1497.40 1497.40 1497.40 1497.40 1497.40 1497.40
 1497.40 1497.40 1497.40 1497.40 1497.40 1497.40 1497.40 1497.40 1497.40 1497.40
 1497.40 1497.40 1497.40 1497.40 1497.40 1497.40 1497.40 1497.40 1497.40 1497.40
Abutment Skew #Up #Dn=,2,2
  4990.0  4991.0
 1523.00 1522.88
  4990.0  4991.0
 1523.00 1521.37
Abutment Skew #Up #Dn=,2,2
  5009.0  5010.0
 1522.53 1523.00
  5009.0  5010.0
 1522.41 1523.00
BR Coef=1,1,0,1.25,0,,,0.8,0,2,0,
WSPro=,,,, 1 ,,,, 0 ,,,, 0 ,,,,-1 ,-1 ,-1 , 0 , 0 , 0 , 0 , 0
BC Design=,,0,,0,,,,,,

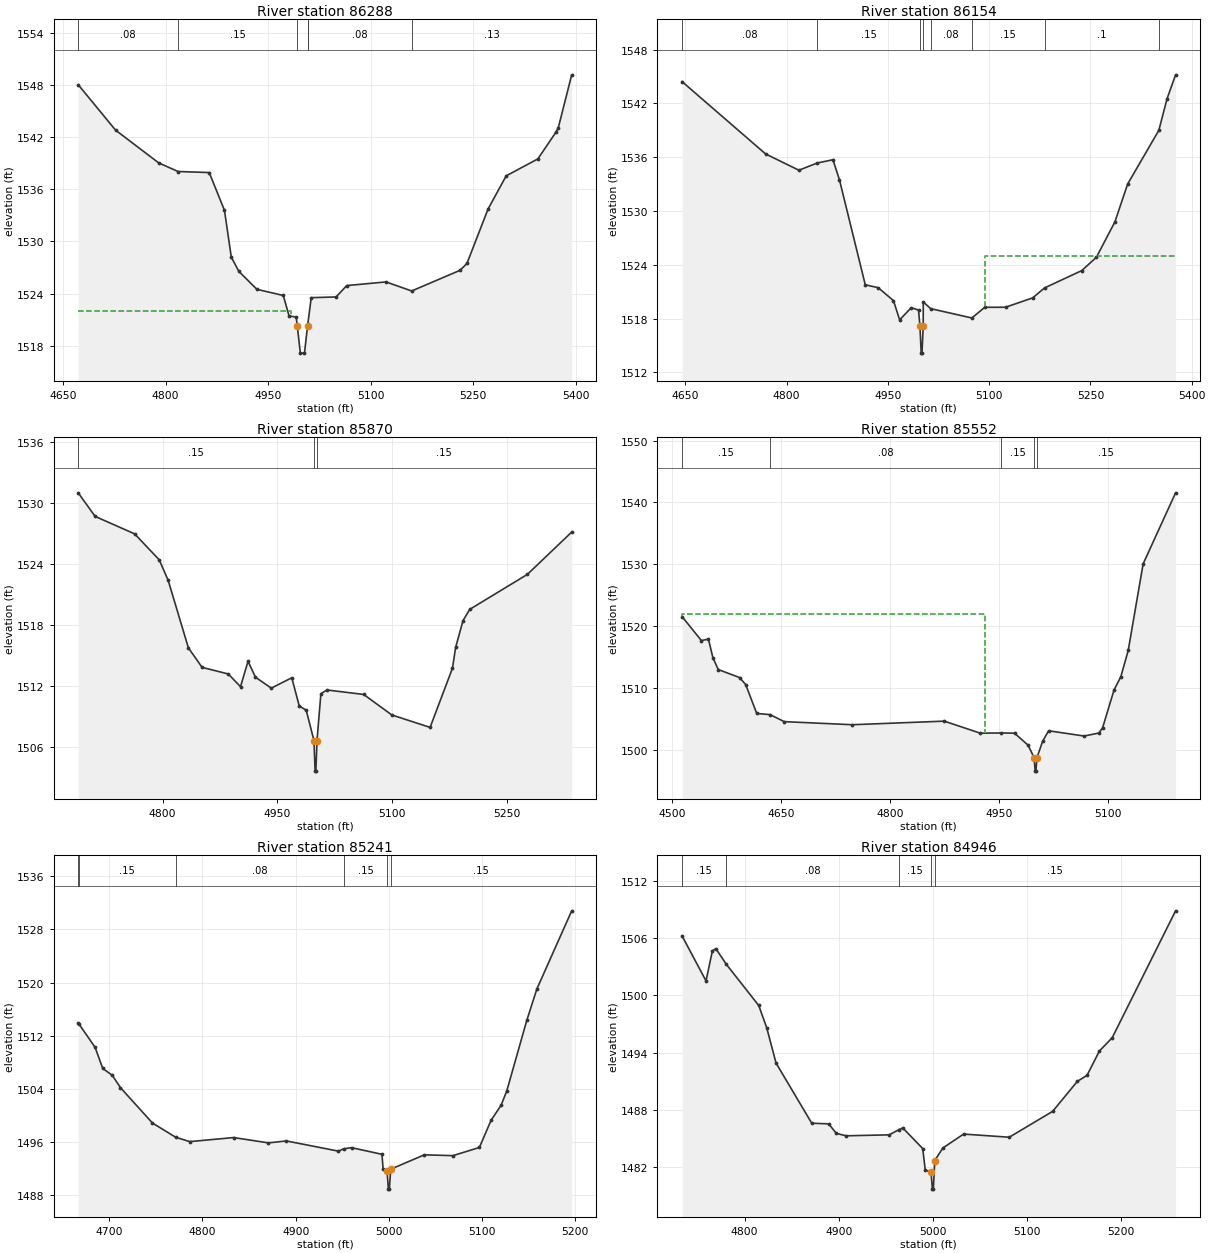
Type RM Length L Ch R = 1,86288,134,134,134
BEGIN DESCRIPTION:
Silver Creek Way DS
END DESCRIPTION:
XS GIS Cut Line= 3
      1428381.50       968539.72      1428088.72       968359.36
      1427769.31       968157.55
#Sta/Elev= 30
  4672.1 1548.02  4726.7 1542.80  4789.8 1539.03  4818.1 1538.04  4863.7 1537.92
  4886.0 1533.57  4896.0 1528.18  4907.1 1526.55  4933.4 1524.49  4972.0 1523.78
  4980.5 1521.42  4990.9 1521.30  4992.5 1520.25  4997.0 1517.15  5003.0 1517.15
  5007.5 1520.25  5007.8 1520.46  5012.9 1523.53  5049.2 1523.61  5064.8 1524.92
  5122.2 1525.34  5159.8 1524.30  5230.4 1526.67  5240.6 1527.46  5271.4 1533.71
  5298.0 1537.54  5344.3 1539.49  5371.1 1542.60  5374.2 1543.07  5393.8 1549.16
#Mann=6,-1,0
  4672.1    0.08       0  4818.1    0.15       0  4992.5    0.05       0
  5007.5    0.15       0  5007.8    0.08       0  5159.8    0.13       0
#XS Ineff=2,0
    0.00 4983.00 1522.00 5017.00    0.00 1522.00
Permanent Ineff=
       F       F
Bank Sta=4992.5,5007.5
XS Rating Curve= 0
Exp/Cntr=0.5,0.3

Type RM Length L Ch R = 1,86154,284,284,284
BEGIN DESCRIPTION:
South Fork 287.0
END DESCRIPTION:
XS GIS Cut Line= 3
      1428462.31       968451.87      1428181.09       968264.39
      1427854.70       968045.63
#Sta/Elev= 30
  4645.3 1544.42  4768.9 1536.36  4818.3 1534.54  4845.3 1535.34  4868.7 1535.71
  4878.4 1533.46  4916.6 1521.76  4935.8 1521.44  4958.4 1519.99  4967.5 1517.85
  4984.7 1519.21  4995.5 1518.94  4997.6 1517.14  4999.4 1514.14  5000.6 1514.14
  5002.4 1517.14  5002.5 1519.85  5013.5 1519.10  5074.5 1518.06  5093.5 1519.25
  5124.4 1519.26  5164.5 1520.30  5182.1 1521.41  5237.3 1523.35  5258.9 1524.83
  5286.4 1528.79  5305.2 1533.00  5351.4 1538.99  5363.5 1542.50  5376.2 1545.18
#Mann=8,-1,0
  4645.3    0.08       0  4845.3    0.15       0  4997.6    0.05       0
  5002.4    0.15       0  5013.5    0.08       0  5074.5    0.15       0
  5182.1     0.1       0  5351.4    0.13       0
#XS Ineff=2,0
       0                 5093.80    0.00 1525.00
Permanent Ineff=
       F       F
Bank Sta=4997.6,5002.4
XS Rating Curve= 0
Exp/Cntr=0.3,0.1

Type RM Length L Ch R = 1,85870,318,318,318
BEGIN DESCRIPTION:
South Fork 286.0
END DESCRIPTION:
XS GIS Cut Line= 3
      1428477.97       968269.61      1428453.66       968146.33
      1428040.48       967830.37
#Sta/Elev= 30
  4689.5 1530.97  4711.6 1528.66  4763.4 1526.94  4795.5 1524.40  4807.2 1522.39
  4833.7 1515.76  4851.6 1513.85  4885.9 1513.20  4901.9 1511.95  4911.7 1514.44
  4921.5 1512.88  4942.2 1511.81  4969.0 1512.83  4978.7 1510.07  4987.9 1509.64
  4998.0 1506.67  4999.5 1503.67  5000.5 1503.67  5002.0 1506.67  5007.1 1511.27
  5015.1 1511.63  5063.1 1511.19  5099.9 1509.18  5150.0 1507.96  5179.3 1513.77
  5183.4 1515.80  5193.1 1518.44  5201.9 1519.54  5277.3 1522.97  5335.3 1527.12
#Mann=3,-1,0
  4689.5    0.15       0  4998.0    0.05       0  5002.0    0.15       0
Bank Sta=4998,5002
XS Rating Curve= 0
Exp/Cntr=0.3,0.1

Type RM Length L Ch R = 1,85552,311,311,311
BEGIN DESCRIPTION:
South Fork 285.0
END DESCRIPTION:
XS GIS Cut Line= 4
      1428632.48       968073.42      1428417.21       967840.78
      1428387.69       967813.00      1428116.83       967641.10
#Sta/Elev= 30
  4514.2 1521.52  4540.7 1517.65  4550.4 1517.88  4556.5 1514.89  4563.9 1512.96
  4593.1 1511.67  4601.6 1510.53  4616.8 1505.85  4635.1 1505.67  4654.5 1504.53
  4748.4 1504.03  4874.5 1504.61  4924.1 1502.66  4952.4 1502.70  4971.1 1502.66
  4989.7 1500.73  4998.0 1498.70  4999.5 1496.52  5000.5 1496.52  5002.0 1498.70
  5009.7 1501.34  5018.0 1503.05  5066.8 1502.20  5087.2 1502.69  5092.3 1503.58
  5107.9 1509.65  5117.3 1511.82  5127.4 1516.05  5147.9 1530.06  5192.5 1541.56
#Mann=5,-1,0
  4514.2    0.15       0  4635.1    0.08       0  4952.4    0.15       0
  4998.0    0.05       0  5002.0    0.15       0
#XS Ineff=2,0
    0.00 4930.00 1522.00               0
Permanent Ineff=
       F       F
Bank Sta=4998,5002
XS Rating Curve= 0
Exp/Cntr=0.3,0.1

Type RM Length L Ch R = 1,85241,295,295,295
BEGIN DESCRIPTION:
South Fork 284.0
END DESCRIPTION:
XS GIS Cut Line= 3
      1428745.33       967896.33      1428641.16       967766.12
      1428425.03       967475.04
#Sta/Elev= 30
  4666.8 1513.88  4667.6 1513.76  4684.9 1510.25  4693.1 1507.07  4703.4 1506.03
  4712.1 1504.18  4746.4 1498.86  4771.4 1496.71  4786.4 1496.06  4833.5 1496.67
  4870.8 1495.87  4890.1 1496.16  4945.9 1494.63  4951.7 1494.98  4960.0 1495.15
  4992.6 1494.15  4993.8 1491.96  4998.0 1491.70  4999.5 1488.91  5000.5 1488.91
  5002.0 1491.91  5038.0 1494.07  5068.7 1493.95  5097.1 1495.18  5109.6 1499.26
  5120.3 1501.51  5126.5 1503.70  5147.9 1514.29  5158.7 1519.01  5196.1 1530.79
#Mann=6,-1,0
  4666.8    0.08       0  4667.6    0.15       0  4771.4    0.08       0
  4951.7    0.15       0  4998.0    0.05       0  5002.0    0.15       0
Bank Sta=4998,5002
XS Rating Curve= 0
Exp/Cntr=0.3,0.1

Type RM Length L Ch R = 1,84946,252,252,252
BEGIN DESCRIPTION:
South Fork 283.0
END DESCRIPTION:
XS GIS Cut Line= 3
      1428981.41       967677.55      1428799.15       967495.29
      1428608.16       967309.51
#Sta/Elev= 30
  4733.6 1506.23  4759.0 1501.53  4765.8 1504.68  4769.5 1504.90  4780.6 1503.26
  4815.0 1498.95  4823.5 1496.61  4833.4 1492.91  4871.3 1486.61  4889.3 1486.54
  4897.5 1485.54  4907.8 1485.29  4953.6 1485.39  4963.8 1485.93  4968.1 1486.11
  4989.2 1483.95  4991.9 1481.70  4998.0 1481.50  4999.5 1479.70  5000.5 1479.70
  5002.0 1482.70  5010.6 1484.01  5032.6 1485.47  5081.1 1485.14  5127.2 1487.85
  5153.4 1490.99  5163.7 1491.62  5176.9 1494.18  5190.5 1495.57  5257.8 1508.87
#Mann=5,-1,0
  4733.6    0.15       0  4780.6    0.08       0  4963.8    0.15       0
  4998.0    0.05       0  5002.0    0.15       0
Bank Sta=4998,5002
XS Rating Curve= 0
Exp/Cntr=0.3,0.1