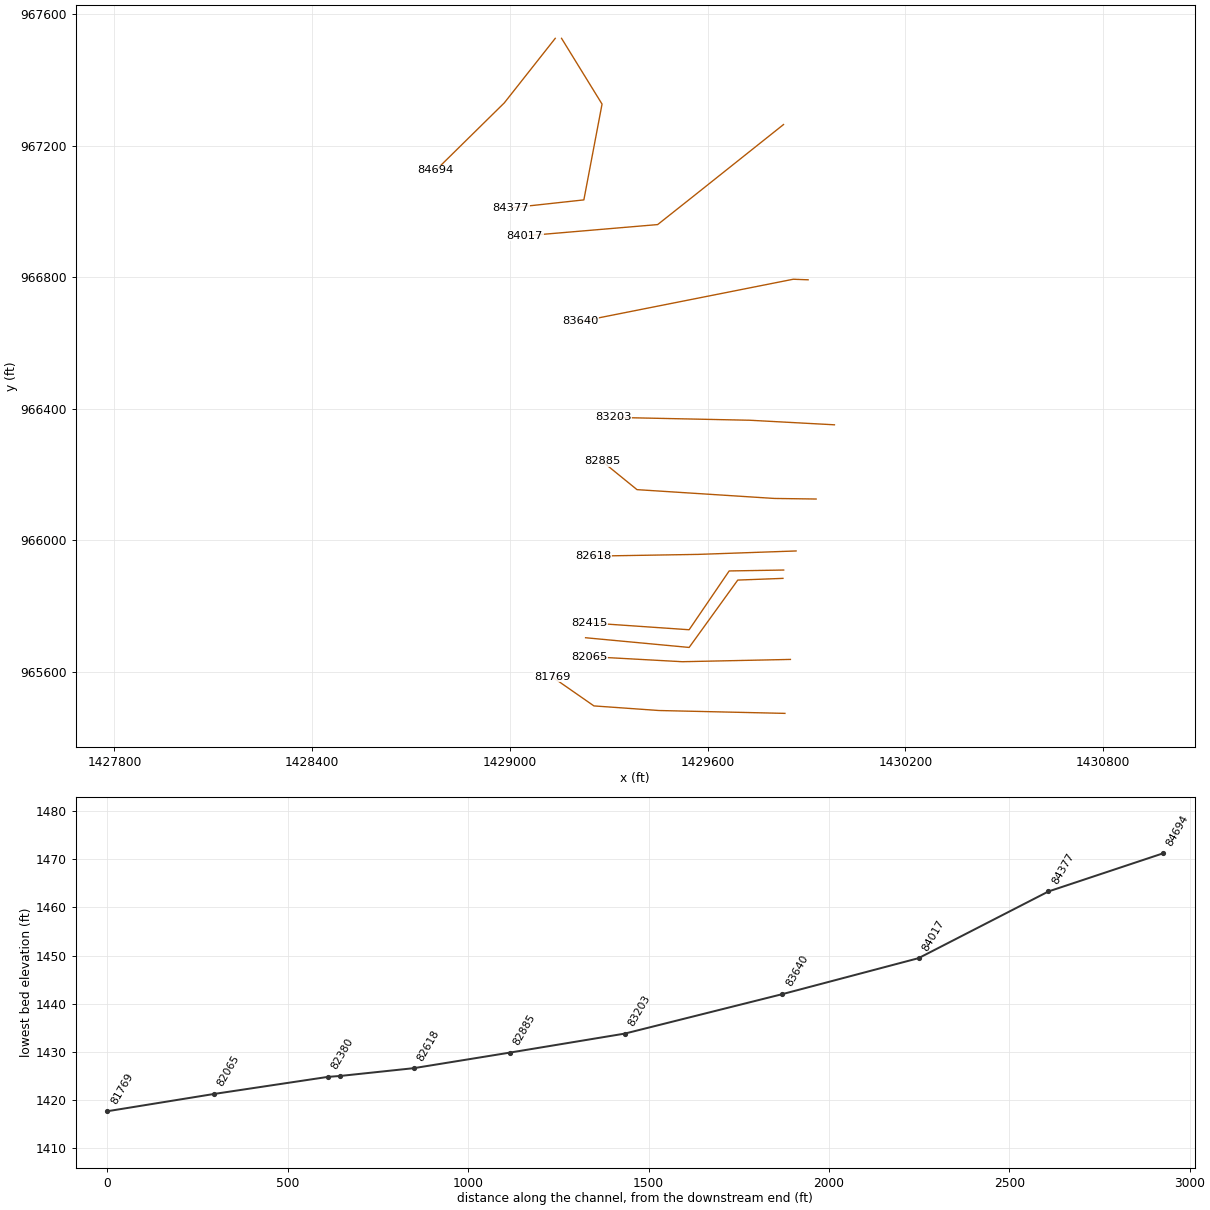
HEC-RAS study South Fork.prj: South Fork Limited Detail Study

--- South Fork.g01 (geometry) --- (continued)

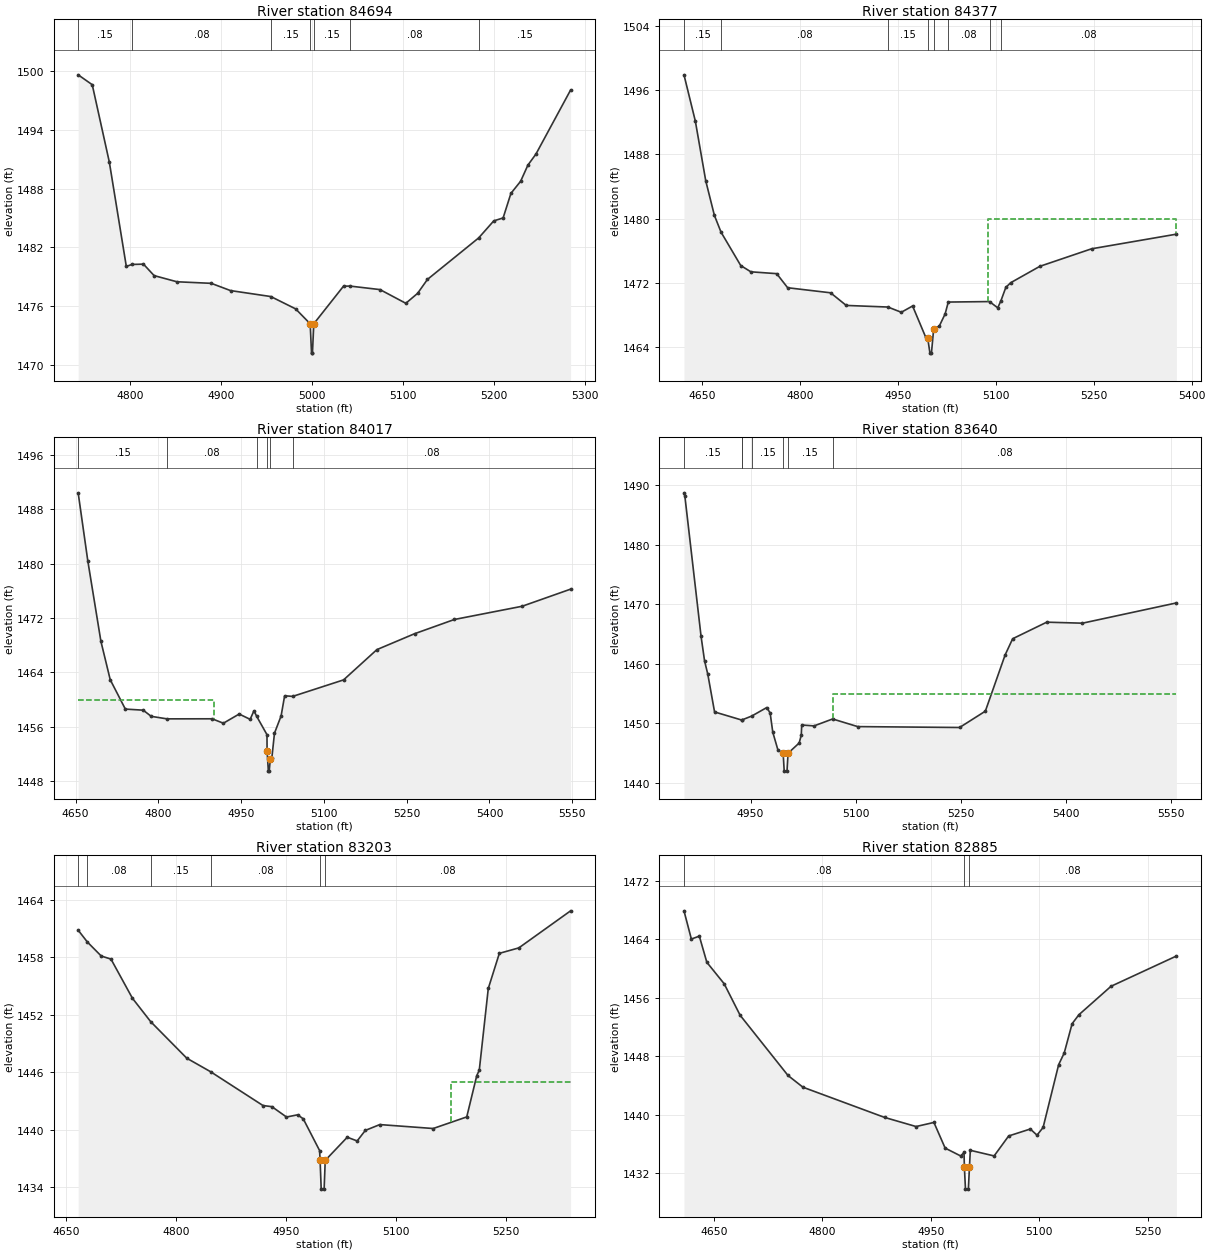
Type RM Length L Ch R = 1,84694,317,317,317
BEGIN DESCRIPTION:
South Fork 282.0
END DESCRIPTION:
XS GIS Cut Line= 4
      1429137.68       967526.53      1429127.13       967513.13
      1428983.18       967330.36      1428775.02       967125.02
#Sta/Elev= 30
  4742.6 1499.63  4758.1 1498.62  4776.9 1490.72  4795.6 1480.06  4801.9 1480.26
  4814.5 1480.29  4826.2 1479.12  4851.3 1478.49  4889.1 1478.33  4910.3 1477.59
  4954.7 1476.98  4982.0 1475.72  4998.0 1474.20  4999.5 1471.20  5000.5 1471.20
  5002.0 1474.20  5034.7 1478.04  5041.8 1478.05  5074.9 1477.69  5103.3 1476.29
  5116.3 1477.31  5127.1 1478.73  5183.5 1482.97  5200.1 1484.71  5210.4 1485.01
  5219.0 1487.52  5229.7 1488.76  5237.7 1490.41  5246.5 1491.53  5284.7 1498.08
#Mann=7,-1,0
  4742.6    0.15       0  4801.9    0.08       0  4954.7    0.15       0
  4998.0    0.05       0  5002.0    0.15       0  5041.8    0.08       0
  5183.5    0.15       0
Bank Sta=4998,5002
XS Rating Curve= 0
Exp/Cntr=0.3,0.1

Type RM Length L Ch R = 1,84377,360,360,360
BEGIN DESCRIPTION:
South Fork 281.0
END DESCRIPTION:
XS GIS Cut Line= 4
      1429156.79       967526.54      1429279.68       967326.54
      1429224.50       967035.22      1429002.26       967010.91
#Sta/Elev= 30
  4621.9 1497.90  4639.3 1492.15  4655.3 1484.71  4668.5 1480.43  4678.7 1478.34
  4708.9 1474.19  4724.4 1473.41  4764.0 1473.18  4780.8 1471.43  4846.6 1470.80
  4870.6 1469.23  4934.5 1469.03  4955.0 1468.38  4972.3 1469.16  4992.3 1465.30
  4995.4 1465.20  4998.9 1463.30  5001.2 1463.30  5004.6 1466.30  5013.1 1466.64
  5022.2 1468.18  5027.0 1469.65  5090.2 1469.71  5102.8 1468.93  5107.8 1469.83
  5115.2 1471.47  5122.6 1472.05  5167.3 1474.09  5246.6 1476.27  5376.7 1478.09
#Mann=8,-1,0
  4621.9    0.15       0  4678.7    0.08       0  4934.5    0.15       0
  4995.4    0.05       0  5004.6    0.15       0  5027.0    0.08       0
  5090.2    0.15       0  5107.8    0.08       0
#XS Ineff=2,0
       0                 5088.10    0.00 1480.00
Permanent Ineff=
       F       F
Bank Sta=4995.4,5004.6
XS Rating Curve= 0
Exp/Cntr=0.5,0.3

Type RM Length L Ch R = 1,84017,377,377,377
BEGIN DESCRIPTION:
South Fork 280.0
END DESCRIPTION:
XS GIS Cut Line= 4
      1429830.37       967264.36      1429556.09       967045.64
      1429448.43       966960.14      1429045.68       966925.85
#Sta/Elev= 30
  4654.6 1490.45  4672.1 1480.41  4695.8 1468.58  4712.7 1462.92  4740.1 1458.59
  4772.5 1458.43  4787.0 1457.52  4815.6 1457.15  4897.3 1457.16  4917.8 1456.51
  4946.4 1457.86  4966.3 1457.08  4973.2 1458.34  4978.3 1457.50  4996.8 1454.82
  4997.0 1452.45  4999.3 1449.45  5000.8 1449.45  5003.0 1451.30  5005.7 1451.45
  5010.4 1455.04  5022.4 1457.58  5028.8 1460.55  5043.4 1460.46  5135.6 1462.89
  5196.0 1467.35  5264.2 1469.69  5336.4 1471.79  5459.3 1473.74  5547.1 1476.26
#Mann=6,-1,0
  4654.6    0.15       0  4815.6    0.08       0  4978.3    0.15       0
  4997.0    0.05       0  5003.0    0.15       0  5043.4    0.08       0
#XS Ineff=2,0
    0.00 4900.00 1460.00               0
Permanent Ineff=
       F       F
Bank Sta=4997,5003
XS Rating Curve= 0
Exp/Cntr=0.3,0.1

Type RM Length L Ch R = 1,83640,437,437,437
BEGIN DESCRIPTION:
South Fork 279.0
END DESCRIPTION:
XS GIS Cut Line= 3
      1429905.02       966792.17      1429859.91       966793.90
      1429214.11       966665.44
#Sta/Elev= 30
  4854.8 1488.68  4856.1 1488.09  4879.2 1464.61  4884.2 1460.49  4888.8 1458.26
  4898.5 1451.92  4937.3 1450.56  4937.8 1450.59  4951.6 1451.23  4973.1 1452.66
  4977.9 1451.74  4981.7 1448.51  4989.1 1445.51  4996.5 1444.99  4998.0 1441.99
  5002.0 1441.99  5003.5 1444.99  5019.4 1446.71  5022.4 1448.04  5023.0 1449.73
  5040.7 1449.58  5067.2 1450.74  5103.0 1449.46  5248.6 1449.31  5285.4 1452.05
  5313.6 1461.47  5324.4 1464.20  5373.1 1466.98  5424.1 1466.81  5558.4 1470.21
#Mann=7,-1,0
  4854.8    0.15       0  4937.3    0.15       0  4937.8    0.08       0
  4951.6    0.15       0  4996.5    0.05       0  5003.5    0.15       0
  5067.2    0.08       0
#XS Ineff=2,0
       0                 5067.20    0.00 1455.00
Permanent Ineff=
       F       F
Bank Sta=4996.5,5003.5
XS Rating Curve= 0
Exp/Cntr=0.3,0.1

Type RM Length L Ch R = 1,83203,318,318,318
BEGIN DESCRIPTION:
South Fork 277.0
END DESCRIPTION:
XS GIS Cut Line= 3
      1429984.87       966351.20      1429727.97       966365.08
      1429313.03       966373.76
#Sta/Elev= 30
  4666.2 1460.83  4678.8 1459.59  4697.7 1458.13  4711.0 1457.81  4740.3 1453.72
  4765.3 1451.27  4814.5 1447.46  4847.0 1446.05  4918.5 1442.52  4930.7 1442.40
  4950.6 1441.32  4965.9 1441.55  4973.5 1441.13  4995.8 1437.82  4996.5 1436.79
  4998.0 1433.79  5002.0 1433.79  5003.5 1436.79  5033.6 1439.21  5047.1 1438.82
  5058.2 1439.92  5078.0 1440.53  5150.9 1440.12  5196.7 1441.33  5210.4 1445.65
  5213.8 1446.20  5226.1 1454.74  5241.2 1458.41  5267.8 1458.98  5338.5 1462.85
#Mann=6,-1,0
  4666.2    0.15       0  4678.8    0.08       0  4765.3    0.15       0
  4847.0    0.08       0  4996.5    0.05       0  5003.5    0.08       0
#XS Ineff=2,0
       0                 5175.00    0.00 1445.00
Permanent Ineff=
       F       F
Bank Sta=4996.5,5003.5
XS Rating Curve= 0
Exp/Cntr=0.3,0.1

Type RM Length L Ch R = 1,82885,267,267,267
BEGIN DESCRIPTION:
South Fork 276.0
END DESCRIPTION:
XS GIS Cut Line= 4
      1429929.32       966125.50      1429802.62       966127.23
      1429385.78       966154.02      1429280.08       966240.06
#Sta/Elev= 30
  4608.9 1467.91  4619.1 1464.05  4630.1 1464.45  4640.5 1460.87  4664.5 1457.93
  4686.5 1453.63  4752.7 1445.39  4773.3 1443.79  4886.1 1439.66  4929.7 1438.41
  4954.4 1438.97  4969.9 1435.46  4991.3 1434.39  4996.0 1434.86  4996.5 1432.85
  4998.0 1429.85  5002.0 1429.85  5003.5 1432.85  5004.7 1435.16  5037.6 1434.39
  5057.7 1437.12  5087.6 1438.07  5096.9 1437.23  5105.3 1438.28  5126.8 1446.87
  5134.5 1448.47  5145.4 1452.47  5154.8 1453.70  5199.2 1457.59  5289.6 1461.73
#Mann=3,-1,0
  4608.9    0.08       0  4996.5    0.05       0  5003.5    0.08       0
Bank Sta=4996.5,5003.5
XS Rating Curve= 0
Exp/Cntr=0.3,0.1

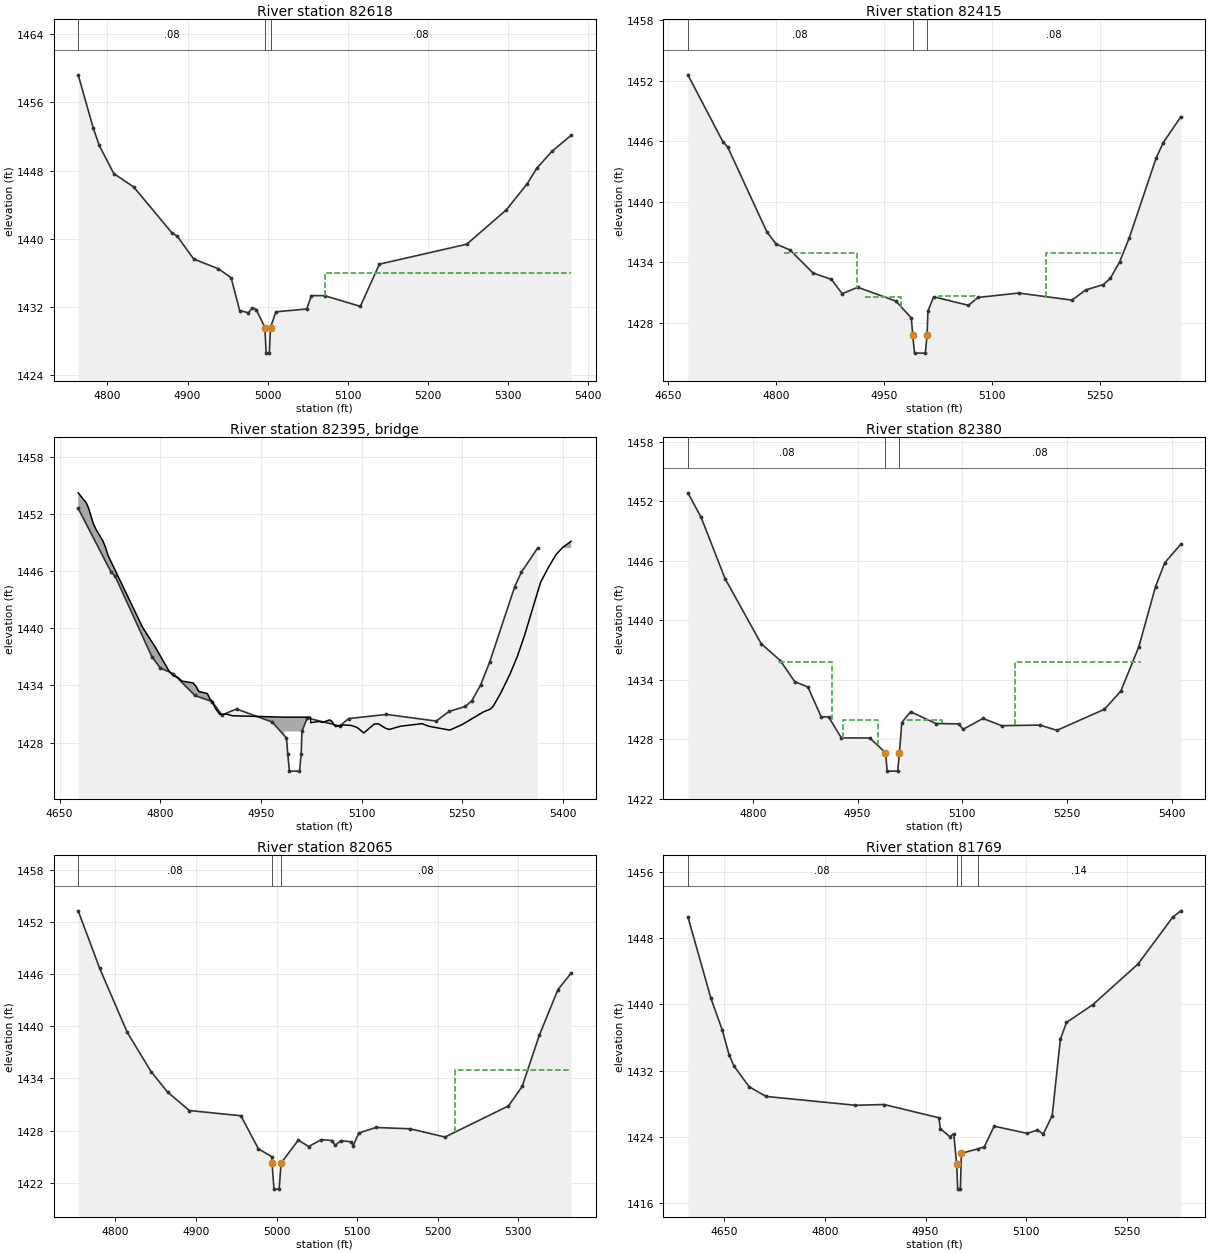
Type RM Length L Ch R = 1,82618,203,203,203
BEGIN DESCRIPTION:
South Fork 275.0
END DESCRIPTION:
XS GIS Cut Line= 3
      1429868.55       965967.51      1429571.72       965957.10
      1429253.98       965951.89
#Sta/Elev= 30
  4763.6 1459.21  4782.5 1452.94  4789.9 1450.94  4808.0 1447.64  4832.8 1446.08
  4880.6 1440.69  4887.0 1440.32  4907.7 1437.63  4938.5 1436.49  4954.4 1435.44
  4965.0 1431.60  4975.8 1431.34  4980.9 1431.92  4985.7 1431.72  4996.5 1429.61
  4998.0 1426.61  5002.0 1426.61  5003.5 1429.61  5010.2 1431.45  5048.7 1431.78
  5054.5 1433.35  5070.9 1433.34  5115.5 1432.09  5139.3 1437.03  5248.3 1439.37
  5297.8 1443.41  5323.7 1446.46  5335.8 1448.29  5354.4 1450.24  5378.4 1452.12
#Mann=3,-1,0
  4763.6    0.08       0  4996.5    0.05       0  5003.5    0.08       0
#XS Ineff=2,0
       0                 5070.90    0.00 1436.00
Permanent Ineff=
       F       F
Bank Sta=4996.5,5003.5
XS Rating Curve= 0
Exp/Cntr=0.5,0.3

Type RM Length L Ch R = 1,82415,35,35,35
BEGIN DESCRIPTION:
Private Bridge US
END DESCRIPTION:
XS GIS Cut Line= 4
      1429830.82       965909.51      1429665.47       965906.75
      1429543.94       965727.93      1429241.84       965748.76
#Sta/Elev= 30
  4677.8 1452.61  4726.5 1445.96  4733.0 1445.46  4787.5 1437.03  4800.3 1435.82
  4819.5 1435.24  4851.6 1432.95  4877.2 1432.31  4892.0 1430.90  4913.7 1431.53
  4966.8 1430.16  4988.1 1428.48  4990.0 1426.80  4992.5 1425.00  5007.5 1425.00
  5010.0 1426.80  5011.1 1429.17  5019.1 1430.59  5067.4 1429.74  5080.6 1430.52
  5137.0 1430.96  5211.2 1430.26  5230.2 1431.27  5254.7 1431.80  5264.3 1432.41
  5277.3 1434.05  5290.8 1436.46  5328.1 1444.38  5337.9 1445.89  5362.2 1448.44
#Mann=3,-1,0
  4677.8    0.08       0  4990.0    0.05       0  5010.0    0.08       0
#XS Ineff=4,-1
 4924.00 4974.00 1430.60 5026.00 5076.00 1430.66 5175.00 5281.00 1434.93
 4811.50 4913.00 1434.93
Permanent Ineff=
       F       F       F       F
Bank Sta=4990,5010
XS Rating Curve= 0
Exp/Cntr=0.5,0.3

Type RM Length L Ch R =3,82395,,,
BEGIN DESCRIPTION:
Private Bridge TOR
Structure ID: LDS_SF_A
Approximate Survey Structure
END DESCRIPTION:
Bridge Culvert--1,0,-1,-1,0
Deck Dist Width WeirC Skew NumUp NumDn MinLoCord MaxHiCord MaxSubmerge Is_Ogee
11,18,3,, 60, 60,,,0.95,0,1,1,,,
  4677.8  4690.2  4693.4  4700.6  4704.8  4714.5  4718.4  4722.4  4773.7  4792.5
  4813.1  4819.3  4827.0  4832.5  4849.0  4853.3  4857.5  4870.1  4874.1  4876.4
  4882.6  4888.8  4898.3  4907.7  4985.0  4985.0  5015.0  5015.0  5023.9  5024.2
  5035.9  5041.7  5052.2  5054.5  5061.0  5073.9  5084.6  5093.6  5103.3  5118.9
  5124.7  5136.2  5141.3  5157.9  5190.1  5199.9  5231.2  5250.0  5281.4  5291.5
  5295.8  5306.9  5321.1  5332.3  5342.3  5366.6  5378.0  5389.8  5399.8  5412.1
 1454.25 1453.16 1452.61 1450.96 1450.35 1449.21 1448.54 1447.65 1440.11 1438.05
 1435.52 1435.04 1434.81 1434.46 1434.27 1433.91 1433.36 1433.16 1432.58 1432.43
 1431.56 1430.95 1431.00 1430.82 1430.67 1430.67 1430.67 1430.67 1430.67 1430.09
 1430.22 1430.12 1430.38 1430.32 1429.69 1429.85 1429.80 1429.58 1429.01 1429.95
 1429.98 1429.49 1429.38 1429.72 1429.99 1429.72 1429.31 1429.90 1431.22 1431.51
 1431.79 1433.15 1435.20 1437.11 1439.16 1444.84 1446.37 1447.77 1448.53 1449.15
 1405.00 1405.00 1405.00 1405.00 1405.00 1405.00 1405.00 1405.00 1405.00 1405.00
 1405.00 1405.00 1405.00 1405.00 1405.00 1405.00 1405.00 1405.00 1405.00 1405.00
 1405.00 1405.00 1405.00 1405.00 1405.00 1429.17 1429.17 1405.00 1405.00 1405.00
 1405.00 1405.00 1405.00 1405.00 1405.00 1405.00 1405.00 1405.00 1405.00 1405.00
 1405.00 1405.00 1405.00 1405.00 1405.00 1405.00 1405.00 1405.00 1405.00 1405.00
 1405.00 1405.00 1405.00 1405.00 1405.00 1405.00 1405.00 1405.00 1405.00 1405.00
  4677.8  4690.2  4693.4  4700.6  4704.8  4714.5  4718.4  4722.4  4773.7  4792.5
  4813.1  4819.3  4827.0  4832.5  4849.0  4853.3  4857.5  4870.1  4874.1  4876.4
  4882.6  4888.8  4898.3  4907.7  4985.0  4985.0  5015.0  5015.0  5023.9  5024.2
  5035.9  5041.7  5052.2  5054.5  5061.0  5073.9  5084.6  5093.6  5103.3  5118.9
  5124.7  5136.2  5141.3  5157.9  5190.1  5199.9  5231.2  5250.0  5281.4  5291.5
  5295.8  5306.9  5321.1  5332.3  5342.3  5366.6  5378.0  5389.8  5399.8  5412.1
 1454.25 1453.16 1452.61 1450.96 1450.35 1449.21 1448.54 1447.65 1440.11 1438.05
 1435.52 1435.04 1434.81 1434.46 1434.27 1433.91 1433.36 1433.16 1432.58 1432.43
 1431.56 1430.95 1431.00 1430.82 1430.67 1430.67 1430.67 1430.67 1430.67 1430.09
 1430.22 1430.12 1430.38 1430.32 1429.69 1429.85 1429.80 1429.58 1429.01 1429.95
 1429.98 1429.49 1429.38 1429.72 1429.99 1429.72 1429.31 1429.90 1431.22 1431.51
 1431.79 1433.15 1435.20 1437.11 1439.16 1444.84 1446.37 1447.77 1448.53 1449.15
 1405.00 1405.00 1405.00 1405.00 1405.00 1405.00 1405.00 1405.00 1405.00 1405.00
 1405.00 1405.00 1405.00 1405.00 1405.00 1405.00 1405.00 1405.00 1405.00 1405.00
 1405.00 1405.00 1405.00 1405.00 1405.00 1429.17 1429.17 1405.00 1405.00 1405.00
 1405.00 1405.00 1405.00 1405.00 1405.00 1405.00 1405.00 1405.00 1405.00 1405.00
 1405.00 1405.00 1405.00 1405.00 1405.00 1405.00 1405.00 1405.00 1405.00 1405.00
 1405.00 1405.00 1405.00 1405.00 1405.00 1405.00 1405.00 1405.00 1405.00 1405.00
BR Coef=1,1,0,1.25,0,,,0.8,0,2,0,
WSPro=,,,, 1 ,,,, 0 ,,,, 0 ,,,,-1 ,-1 ,-1 , 0 , 0 , 0 , 0 , 0
BC Design=,,0,,0,,,,,,

Type RM Length L Ch R = 1,82380,315,315,315
BEGIN DESCRIPTION:
Private Bridge DS
END DESCRIPTION:
XS GIS Cut Line= 4
      1429828.69       965884.18      1429691.51       965878.97
      1429543.94       965674.11      1429229.68       965703.63
#Sta/Elev= 30
  4707.2 1452.85  4726.2 1450.37  4760.5 1444.19  4812.0 1437.66  4839.5 1435.94
  4860.1 1433.82  4878.9 1433.28  4898.0 1430.28  4908.6 1430.26  4926.9 1428.15
  4967.5 1428.14  4990.0 1426.67  4992.5 1424.80  5007.5 1424.80  5010.0 1426.67
  5013.4 1429.70  5025.9 1430.79  5062.0 1429.60  5095.0 1429.56  5101.0 1429.01
  5129.5 1430.11  5156.2 1429.38  5211.4 1429.44  5235.3 1428.91  5303.2 1431.03
  5326.7 1432.85  5352.5 1437.32  5376.5 1443.40  5389.7 1445.81  5412.6 1447.66
#Mann=3,-1,0
  4707.2    0.08       0  4990.0    0.05       0  5010.0    0.08       0
#XS Ineff=4,-1
 4928.70 4978.70 1430.00 5021.00 5071.00 1430.00 5175.00 5355.40 1435.81
 4837.70 4913.00 1435.81
Permanent Ineff=
       F       F       F       F
Bank Sta=4990,5010
XS Rating Curve= 0
Exp/Cntr=0.5,0.3

Type RM Length L Ch R = 1,82065,296,296,296
BEGIN DESCRIPTION:
South Fork 274.0
END DESCRIPTION:
XS GIS Cut Line= 3
      1429851.27       965637.65      1429523.11       965630.71
      1429240.08       965646.33
#Sta/Elev= 30
  4753.8 1453.27  4780.4 1446.67  4814.7 1439.29  4844.3 1434.77  4864.7 1432.43
  4891.7 1430.30  4955.7 1429.70  4977.5 1425.89  4994.3 1424.98  4994.4 1424.26
  4996.8 1421.26  5003.2 1421.26  5005.6 1424.26  5026.9 1426.89  5039.9 1426.16
  5055.6 1426.96  5068.9 1426.85  5072.7 1426.28  5079.6 1426.84  5092.7 1426.70
  5095.1 1426.24  5102.0 1427.72  5123.4 1428.35  5165.8 1428.20  5209.0 1427.25
  5287.8 1430.83  5304.8 1433.07  5326.0 1438.94  5349.2 1444.21  5365.5 1446.10
#Mann=3,-1,0
  4753.8    0.08       0  4994.4    0.05       0  5005.6    0.08       0
#XS Ineff=2,0
       0                 5221.90    0.00 1435.00
Permanent Ineff=
       F       F
Bank Sta=4994.4,5005.6
XS Rating Curve= 0
Exp/Cntr=0.3,0.1

Type RM Length L Ch R = 1,81769,235,235,235
BEGIN DESCRIPTION:
South Fork 273.0
END DESCRIPTION:
XS GIS Cut Line= 4
      1429834.71       965473.59      1429452.80       965482.27
      1429255.01       965496.29      1429128.17       965584.68
#Sta/Elev= 30
  4595.7 1450.61  4630.1 1440.73  4646.9 1436.93  4657.1 1433.93  4664.5 1432.55
  4687.1 1430.05  4712.1 1428.88  4845.6 1427.81  4888.3 1427.90  4969.9 1426.30
  4972.2 1424.99  4986.3 1424.00  4992.1 1424.37  4996.5 1420.67  4998.0 1417.67
  5002.0 1417.67  5003.5 1422.00  5027.7 1422.53  5037.5 1422.77  5052.4 1425.28
  5101.8 1424.41  5116.6 1424.81  5125.7 1424.35  5138.9 1426.56  5151.1 1435.80
  5160.2 1437.82  5199.6 1439.98  5267.1 1444.91  5318.6 1450.55  5330.6 1451.32
#Mann=4,-1,0
  4595.7    0.08       0  4996.5    0.05       0  5003.5    0.08       0
  5027.7    0.14       0
Bank Sta=4996.5,5003.5
XS Rating Curve= 0
Exp/Cntr=0.3,0.1