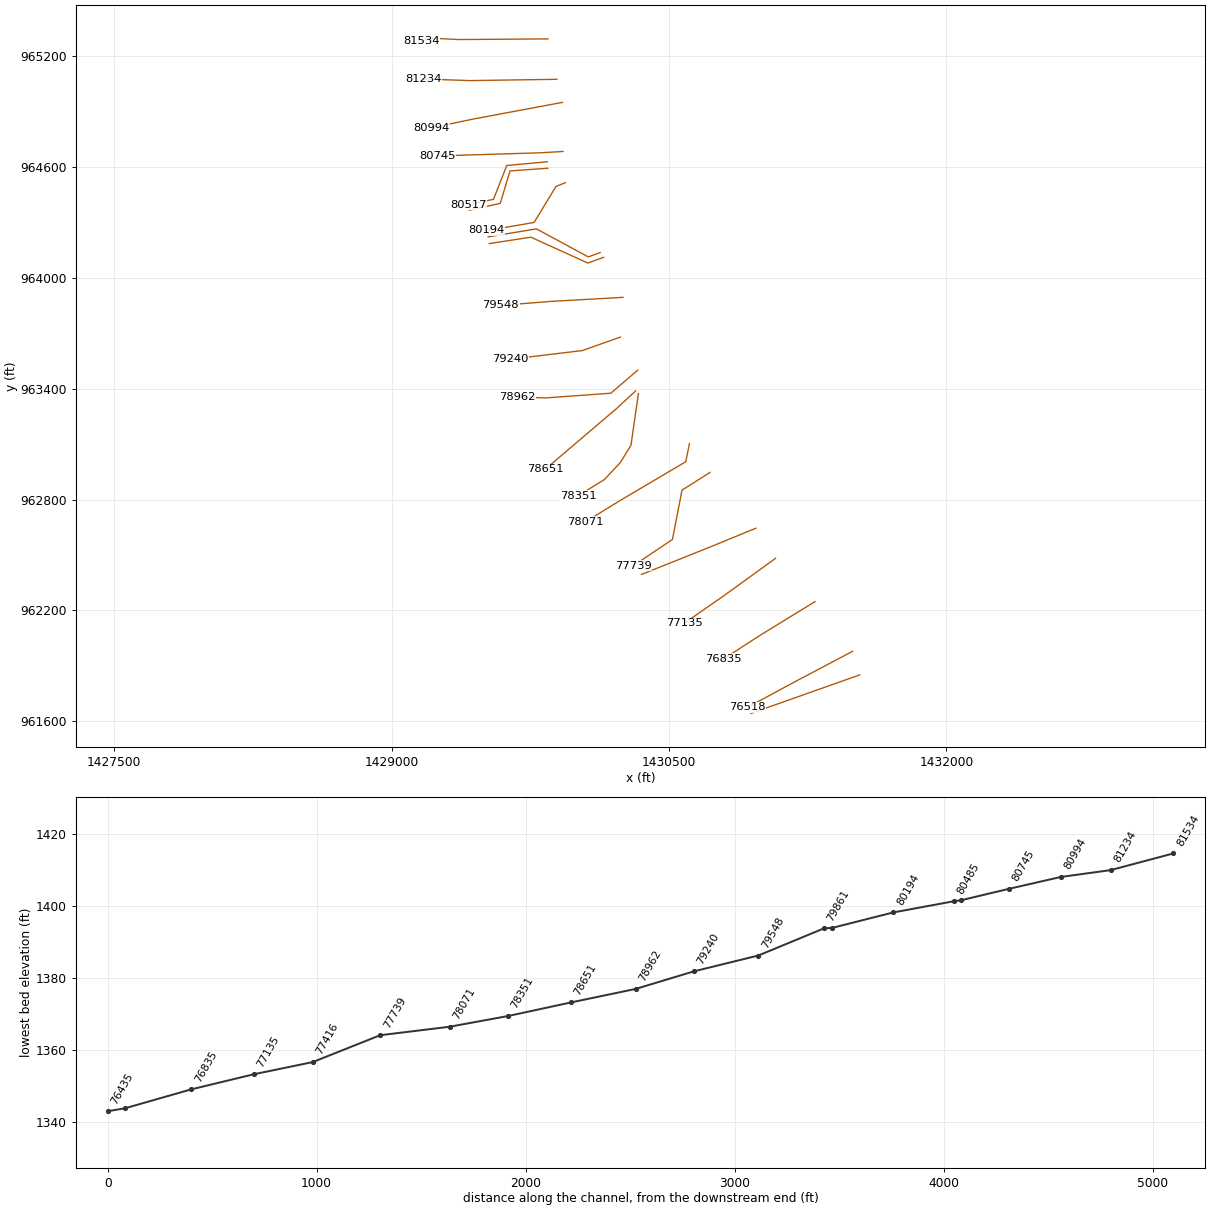
HEC-RAS study South Fork.prj: South Fork Limited Detail Study

--- South Fork.g01 (geometry) --- (continued)

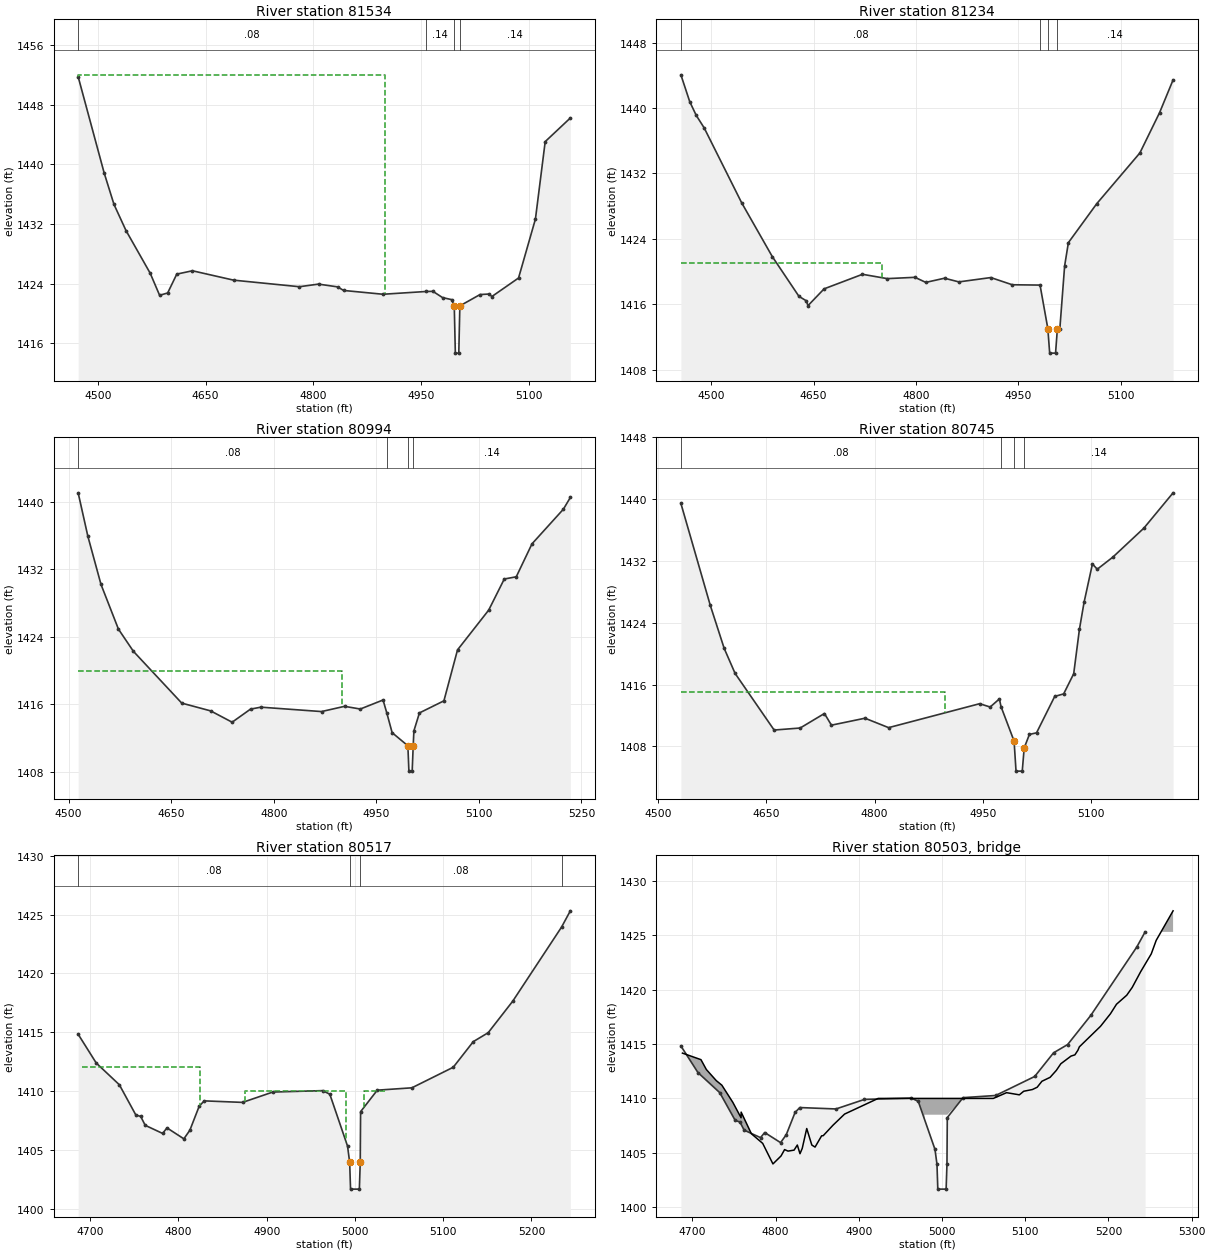
Type RM Length L Ch R = 1,81534,300,300,300
BEGIN DESCRIPTION:
South Fork 272.0
END DESCRIPTION:
XS GIS Cut Line= 4
      1429845.18       965294.77      1429362.52       965291.30
      1429232.29       965297.86      1429161.12       965286.09
#Sta/Elev= 30
  4472.5 1451.75  4508.7 1438.84  4522.4 1434.61  4539.1 1431.11  4572.8 1425.38
  4585.9 1422.42  4597.1 1422.73  4609.8 1425.26  4631.6 1425.71  4689.0 1424.45
  4780.5 1423.57  4807.1 1423.92  4833.7 1423.55  4842.0 1423.07  4896.9 1422.56
  4957.0 1422.93  4966.4 1422.95  4979.8 1422.11  4992.4 1421.84  4996.1 1421.00
  4997.6 1414.66  5002.4 1414.66  5003.9 1421.00  5032.0 1422.52  5044.9 1422.59
  5048.4 1422.25  5085.6 1424.74  5109.1 1432.65  5122.7 1443.04  5157.7 1446.21
#Mann=4,-1,0
  4472.5    0.08       0  4957.0    0.14       0  4996.1    0.05       0
  5003.9    0.14       0
#XS Ineff=2,0
    0.00 4900.00 1452.00               0
Permanent Ineff=
       F       F
Bank Sta=4996.1,5003.9
XS Rating Curve= 0
Exp/Cntr=0.3,0.1

Type RM Length L Ch R = 1,81234,240,240,240
BEGIN DESCRIPTION:
South Fork 271.0
END DESCRIPTION:
XS GIS Cut Line= 3
      1429893.81       965076.02      1429421.55       965069.08
      1429173.31       965077.75
#Sta/Elev= 30
  4455.7 1444.06  4468.6 1440.79  4478.1 1439.11  4489.8 1437.57  4544.7 1428.41
  4589.5 1421.84  4628.6 1416.97  4639.5 1416.42  4641.7 1415.83  4665.4 1417.89
  4721.6 1419.67  4757.9 1419.14  4798.4 1419.30  4814.3 1418.68  4841.7 1419.19
  4862.7 1418.74  4909.5 1419.27  4940.9 1418.39  4981.6 1418.35  4993.0 1413.03
  4995.7 1410.03  5004.3 1410.03  5007.0 1413.03  5010.6 1413.03  5017.6 1420.70
  5023.1 1423.54  5064.6 1428.30  5127.8 1434.51  5156.6 1439.43  5176.4 1443.44
#Mann=4,-1,0
  4455.7    0.08       0  4981.6    0.14       0  4993.0    0.05       0
  5007.0    0.14       0
#XS Ineff=2,0
    0.00 4750.00 1421.00               0
Permanent Ineff=
       F       F
Bank Sta=4993,5007
XS Rating Curve= 0
Exp/Cntr=0.3,0.1

Type RM Length L Ch R = 1,80994,249,249,249
BEGIN DESCRIPTION:
South Fork 270.0
END DESCRIPTION:
XS GIS Cut Line= 3
      1429923.29       964951.02      1429440.64       964860.74
      1429216.72       964813.87
#Sta/Elev= 30
  4513.9 1441.05  4528.1 1435.91  4547.3 1430.21  4572.8 1424.92  4594.7 1422.29
  4665.4 1416.16  4707.7 1415.24  4739.1 1413.90  4766.0 1415.45  4781.2 1415.68
  4869.8 1415.16  4903.5 1415.78  4926.5 1415.46  4959.8 1416.53  4965.2 1415.02
  4973.1 1412.66  4996.1 1411.11  4997.6 1408.11  5002.4 1408.11  5003.9 1411.11
  5004.9 1412.87  5013.0 1415.00  5048.8 1416.43  5068.7 1422.46  5114.3 1427.17
  5137.1 1430.85  5154.6 1431.11  5177.6 1435.01  5223.5 1439.11  5233.7 1440.50
#Mann=4,-1,0
  4513.9    0.08       0  4965.2    0.14       0  4996.1    0.05       0
  5003.9    0.14       0
#XS Ineff=2,0
    0.00 4900.00 1420.00               0
Permanent Ineff=
       F       F
Bank Sta=4996.1,5003.9
XS Rating Curve= 0
Exp/Cntr=0.3,0.1

Type RM Length L Ch R = 1,80745,228,228,228
BEGIN DESCRIPTION:
South Fork 269.0
END DESCRIPTION:
XS GIS Cut Line= 3
      1429926.75       964685.39      1429812.17       964678.45
      1429246.23       964661.09
#Sta/Elev= 30
  4532.0 1439.46  4572.7 1426.25  4591.9 1420.69  4607.0 1417.45  4661.0 1410.12
  4697.0 1410.38  4730.6 1412.26  4740.3 1410.75  4786.7 1411.65  4819.4 1410.43
  4945.4 1413.53  4959.9 1413.10  4972.7 1414.15  4974.9 1413.16  4993.0 1408.69
  4995.7 1404.80  5004.3 1404.80  5007.0 1407.80  5014.2 1409.55  5024.1 1409.76
  5049.2 1414.47  5061.6 1414.80  5075.5 1417.41  5083.4 1423.15  5089.8 1426.64
  5101.4 1431.62  5108.1 1430.94  5129.7 1432.51  5172.6 1436.26  5213.0 1440.83
#Mann=4,-1,0
  4532.0    0.08       0  4974.9    0.14       0  4993.0    0.05       0
  5007.0    0.14       0
#XS Ineff=2,0
    0.00 4897.00 1415.00               0
Permanent Ineff=
       F       F
Bank Sta=4993,5007
XS Rating Curve= 0
Exp/Cntr=0.5,0.3

Type RM Length L Ch R = 1,80517,32,32,32
BEGIN DESCRIPTION:
Private Bridge 2 US
END DESCRIPTION:
XS GIS Cut Line= 4
      1429842.22       964629.70      1429622.62       964609.20
      1429550.90       964426.23      1429413.26       964396.94
#Sta/Elev= 30
  4686.3 1414.83  4706.8 1412.38  4733.0 1410.53  4751.6 1407.97  4757.2 1407.83
  4762.3 1407.08  4782.0 1406.39  4787.0 1406.86  4806.1 1405.93  4812.9 1406.66
  4823.5 1408.71  4829.2 1409.16  4872.6 1409.03  4906.9 1409.91  4963.3 1410.03
  4971.5 1409.73  4991.6 1405.31  4994.0 1403.94  4995.0 1401.65  5005.0 1401.65
  5006.0 1403.94  5006.4 1408.24  5025.3 1410.07  5064.5 1410.27  5111.4 1412.02
  5134.1 1414.20  5151.0 1414.96  5178.8 1417.64  5234.1 1423.94  5244.1 1425.33
#Mann=4,-1,0
  4686.3    0.08       0  4994.0    0.05       0  5006.0    0.08       0
  5234.1    0.14       0
#XS Ineff=3,-1
 4691.20 4824.00 1412.02 4875.30 4990.00 1410.00 5010.00 5035.90 1410.00
Permanent Ineff=
       F       F       F
Bank Sta=4994,5006
XS Rating Curve= 0
Exp/Cntr=0.5,0.3

Type RM Length L Ch R =3,80503,,,
BEGIN DESCRIPTION:
Private Bridge 2 TOR
Structure ID: LDS_SF_B
Approximate Survey Structure
END DESCRIPTION:
Bridge Culvert--1,0,-1,-1,0
Deck Dist Width WeirC Skew NumUp NumDn MinLoCord MaxHiCord MaxSubmerge Is_Ogee
3,22,3,, 53, 53,,,0.95,0,1,1,,,
  4688.2  4710.4  4716.9  4728.8  4735.5  4748.7  4758.6  4758.7  4771.0  4784.6
  4796.9  4806.6  4810.9  4815.0  4822.3  4826.2  4829.4  4832.1  4837.5  4843.6
  4847.5  4855.4  4857.3  4869.0  4883.0  4923.3  4979.0  4979.0  5021.0  5021.0
  5061.7  5077.6  5093.0  5098.2  5108.7  5114.4  5120.1  5129.9  5137.4  5142.8
  5155.1  5159.7  5163.3  5165.1  5190.5  5202.4  5209.7  5222.0  5228.6  5238.7
  5251.5  5257.4  5277.7
 1414.17 1413.57 1412.66 1411.64 1411.22 1409.64 1408.22 1408.74 1406.75 1405.86
 1403.97 1404.70 1405.29 1405.15 1405.24 1405.71 1404.91 1405.40 1407.23 1405.71
 1405.52 1406.56 1406.57 1407.53 1408.56 1410.00 1410.00 1410.00 1410.00 1410.00
 1410.00 1410.53 1410.33 1410.66 1410.82 1411.03 1411.58 1411.94 1412.58 1413.19
 1413.90 1414.01 1414.43 1414.75 1416.64 1417.79 1418.67 1419.50 1420.22 1421.66
 1423.31 1424.55 1427.27
 1381.65 1381.65 1381.65 1381.65 1381.65 1381.65 1381.65 1381.65 1381.65 1381.65
 1381.65 1381.65 1381.65 1381.65 1381.65 1381.65 1381.65 1381.65 1381.65 1381.65
 1381.65 1381.65 1381.65 1381.65 1381.65 1381.65 1381.65 1408.50 1408.50 1381.65
 1381.65 1381.65 1381.65 1381.65 1381.65 1381.65 1381.65 1381.65 1381.65 1381.65
 1381.65 1381.65 1381.65 1381.65 1381.65 1381.65 1381.65 1381.65 1381.65 1381.65
 1381.65 1381.65 1381.65
  4688.2  4710.4  4716.9  4728.8  4735.5  4748.7  4758.6  4758.7  4771.0  4784.6
  4796.9  4806.6  4810.9  4815.0  4822.3  4826.2  4829.4  4832.1  4837.5  4843.6
  4847.5  4855.4  4857.3  4869.0  4883.0  4923.3  4979.0  4979.0  5021.0  5021.0
  5061.7  5077.6  5093.0  5098.2  5108.7  5114.4  5120.1  5129.9  5137.4  5142.8
  5155.1  5159.7  5163.3  5165.1  5190.5  5202.4  5209.7  5222.0  5228.6  5238.7
  5251.5  5257.4  5277.7
 1414.17 1413.57 1412.66 1411.64 1411.22 1409.64 1408.22 1408.74 1406.75 1405.86
 1403.97 1404.70 1405.29 1405.15 1405.24 1405.71 1404.91 1405.40 1407.23 1405.71
 1405.52 1406.56 1406.57 1407.53 1408.56 1410.00 1410.00 1410.00 1410.00 1410.00
 1410.00 1410.53 1410.33 1410.66 1410.82 1411.03 1411.58 1411.94 1412.58 1413.19
 1413.90 1414.01 1414.43 1414.75 1416.64 1417.79 1418.67 1419.50 1420.22 1421.66
 1423.31 1424.55 1427.27
 1381.65 1381.65 1381.65 1381.65 1381.65 1381.65 1381.65 1381.65 1381.65 1381.65
 1381.65 1381.65 1381.65 1381.65 1381.65 1381.65 1381.65 1381.65 1381.65 1381.65
 1381.65 1381.65 1381.65 1381.65 1381.65 1381.65 1381.65 1408.50 1408.50 1381.65
 1381.65 1381.65 1381.65 1381.65 1381.65 1381.65 1381.65 1381.65 1381.65 1381.65
 1381.65 1381.65 1381.65 1381.65 1381.65 1381.65 1381.65 1381.65 1381.65 1381.65
 1381.65 1381.65 1381.65
BR Coef=1,1,0,1.25,0,,,0.8,0,2,0,
WSPro=,,,, 1 ,,,, 0 ,,,, 0 ,,,,-1 ,-1 ,-1 , 0 , 0 , 0 , 0 , 0
BC Design=,,0,,0,,,,,,

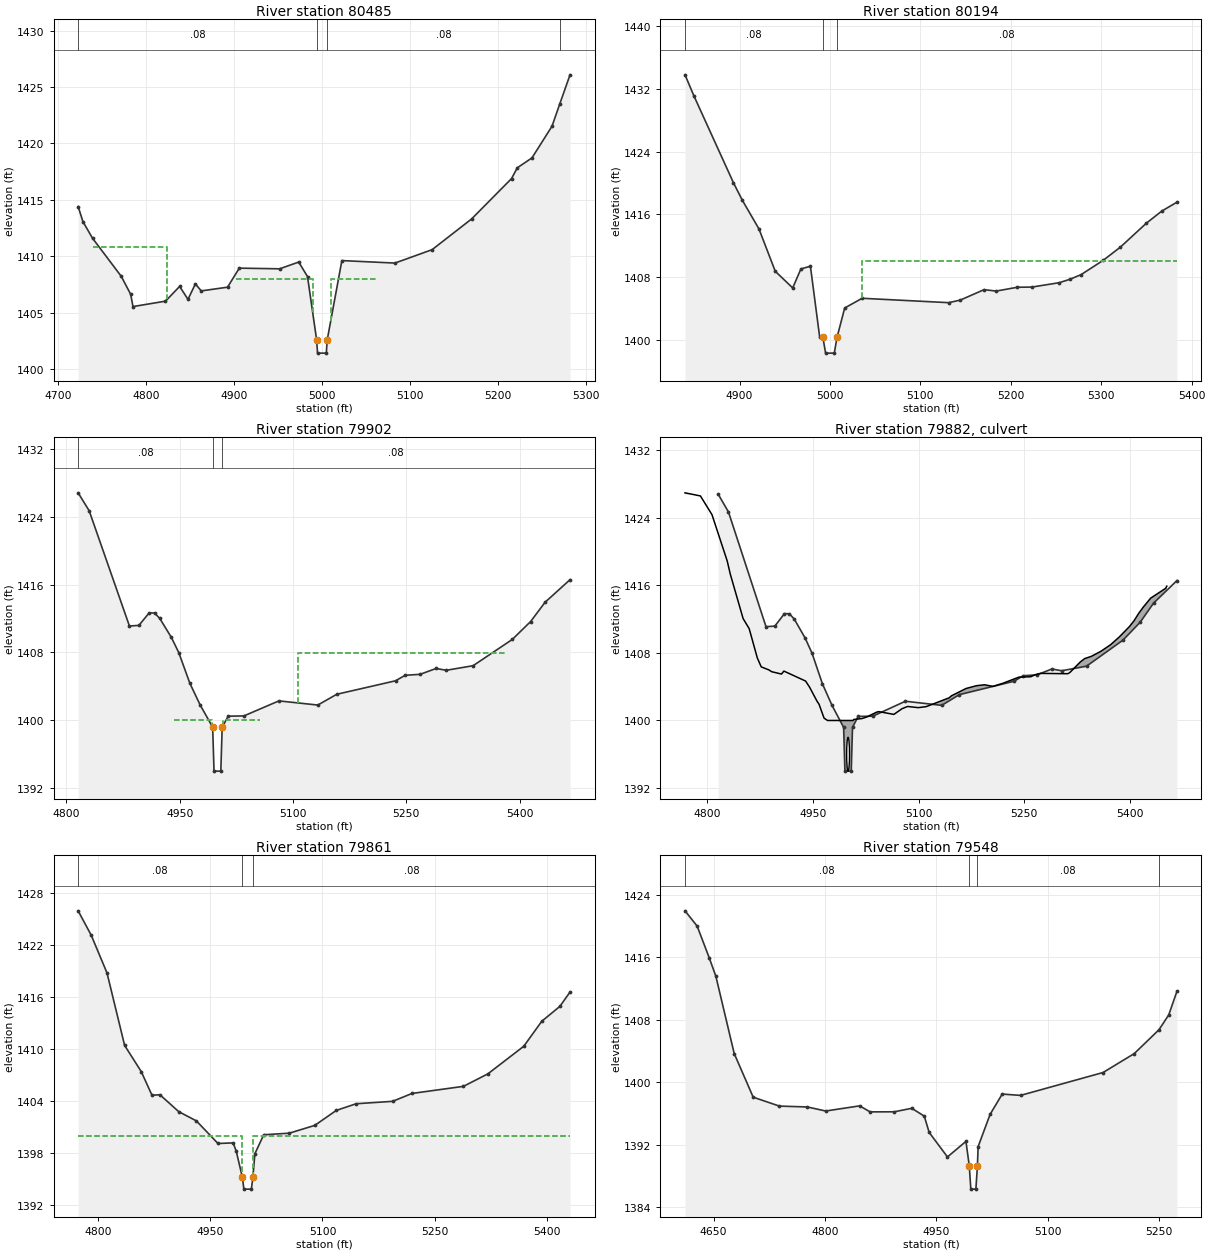
Type RM Length L Ch R = 1,80485,291,291,291
BEGIN DESCRIPTION:
Private Bridge 2 DS
END DESCRIPTION:
XS GIS Cut Line= 4
      1429845.14       964594.56      1429640.19       964579.92
      1429587.49       964404.27      1429420.62       964367.68
#Sta/Elev= 30
  4722.6 1414.40  4728.1 1413.06  4739.0 1411.59  4771.6 1408.22  4782.4 1406.62
  4785.0 1405.53  4822.0 1406.01  4838.1 1407.32  4847.6 1406.17  4856.0 1407.54
  4862.7 1406.92  4892.6 1407.25  4906.0 1408.94  4951.9 1408.88  4973.6 1409.48
  4983.6 1408.19  4994.0 1402.56  4995.0 1401.40  5005.0 1401.40  5006.0 1402.56
  5022.7 1409.61  5083.1 1409.39  5125.4 1410.58  5170.4 1413.31  5215.8 1416.89
  5222.3 1417.84  5239.0 1418.72  5261.8 1421.53  5270.7 1423.52  5282.3 1426.09
#Mann=4,-1,0
  4722.6    0.08       0  4994.0    0.05       0  5006.0    0.08       0
  5270.7    0.14       0
#XS Ineff=3,-1
 4739.50 4824.00 1410.78 4902.30 4989.60 1408.00 5010.00 5062.00 1408.00
Permanent Ineff=
       F       F       F
Bank Sta=4994,5006
XS Rating Curve= 0
Exp/Cntr=0.5,0.3

Type RM Length L Ch R = 1,80194,292,292,292
BEGIN DESCRIPTION:
South Fork 268.0
END DESCRIPTION:
XS GIS Cut Line= 5
      1429938.98       964516.31      1429888.62       964495.47
      1429770.57       964301.02      1429629.94       964276.72
      1429511.89       964259.36
#Sta/Elev= 30
  4839.7 1433.80  4849.6 1431.10  4893.3 1420.02  4902.9 1417.83  4921.5 1414.13
  4939.5 1408.73  4958.8 1406.60  4967.9 1409.03  4978.4 1409.37  4988.6 1400.36
  4992.2 1400.28  4995.2 1398.28  5004.8 1398.28  5007.8 1400.28  5016.3 1404.04
  5035.6 1405.28  5131.3 1404.72  5144.2 1405.05  5170.4 1406.38  5183.9 1406.20
  5207.4 1406.69  5223.3 1406.71  5253.6 1407.27  5265.5 1407.71  5277.6 1408.29
  5302.3 1410.13  5321.3 1411.82  5350.0 1414.87  5367.0 1416.41  5383.7 1417.54
#Mann=3,-1,0
  4839.7    0.08       0  4992.2    0.05       0  5007.8    0.08       0
#XS Ineff=2,0
       0                 5035.60    0.00 1410.00
Permanent Ineff=
       F       F
Bank Sta=4992.2,5007.8
XS Rating Curve= 0
Exp/Cntr=0.5,0.3

Type RM Length L Ch R = 1,79902,41,41,41
BEGIN DESCRIPTION:
Private Culvert 3
END DESCRIPTION:
XS GIS Cut Line= 4
      1430127.29       964137.93      1430063.55       964114.45
      1429782.72       964266.30      1429522.29       964222.90
#Sta/Elev= 30
  4815.6 1426.81  4830.2 1424.70  4883.5 1411.11  4896.0 1411.18  4909.7 1412.66
  4916.8 1412.64  4923.7 1412.00  4939.0 1409.77  4948.8 1407.98  4963.6 1404.34
  4977.2 1401.79  4993.7 1399.18  4995.5 1394.00  5004.5 1394.00  5006.3 1399.18
  5014.3 1400.48  5035.1 1400.51  5081.4 1402.28  5132.9 1401.79  5158.0 1403.06
  5235.8 1404.65  5248.6 1405.30  5268.3 1405.41  5289.4 1406.10  5303.1 1405.89
  5338.5 1406.43  5390.3 1409.52  5414.7 1411.64  5433.8 1413.91  5466.8 1416.57
#Mann=3,-1,0
  4815.6    0.08       0  4993.7    0.05       0  5006.3    0.08       0
#XS Ineff=3,-1
 4943.00 4993.00 1400.00 5007.00 5057.00 1400.00 5106.20 5383.20 1407.87
Permanent Ineff=
       F       F       F
Bank Sta=4993.7,5006.3
XS Rating Curve= 0
Exp/Cntr=0.5,0.3

Type RM Length L Ch R =2,79882,,,
BEGIN DESCRIPTION:
Private Culvert 3 TOR
Structure ID: LDS_SF_C
Approximate Survey Structure
END DESCRIPTION:
Bridge Culvert--1,0,-1,-1,0
Deck Dist Width WeirC Skew NumUp NumDn MinLoCord MaxHiCord MaxSubmerge Is_Ogee
2.5,35,3,, 56, 56,,,0.95,0,1,1,,,
  4768.5  4790.4  4806.8  4828.4  4832.8  4851.0  4859.6  4871.1  4876.7  4887.6
  4891.5  4905.4  4908.9  4939.7  4945.4  4955.8  4958.8  4965.9  4970.8  5007.0
  5008.2  5019.9  5026.3  5040.9  5043.7  5065.0  5076.7  5084.5  5099.7  5110.9
  5143.4  5146.7  5167.5  5182.3  5193.8  5205.7  5219.5  5242.7  5259.3  5265.9
  5273.3  5312.0  5314.8  5329.6  5336.1  5345.4  5359.0  5372.9  5385.1  5399.6
  5406.0  5412.5  5418.9  5429.5  5450.7  5452.5
 1426.97 1426.60 1424.38 1418.90 1417.33 1412.07 1410.88 1407.42 1406.35 1405.99
 1405.78 1405.50 1405.85 1404.67 1403.94 1402.30 1401.92 1400.28 1400.00 1400.00
 1400.12 1400.23 1400.41 1401.00 1401.05 1400.72 1401.40 1401.66 1401.52 1401.64
 1402.68 1402.92 1403.79 1404.12 1404.23 1404.04 1404.40 1405.14 1405.18 1405.43
 1405.58 1405.54 1405.68 1406.93 1407.34 1407.60 1408.20 1408.99 1409.90 1411.14
 1411.82 1412.68 1413.41 1414.49 1415.65 1415.91
 1374.00 1374.00 1374.00 1374.00 1374.00 1374.00 1374.00 1374.00 1374.00 1374.00
 1374.00 1374.00 1374.00 1374.00 1374.00 1374.00 1374.00 1374.00 1374.00 1374.00
 1374.00 1374.00 1374.00 1374.00 1374.00 1374.00 1374.00 1374.00 1374.00 1374.00
 1374.00 1374.00 1374.00 1374.00 1374.00 1374.00 1374.00 1374.00 1374.00 1374.00
 1374.00 1374.00 1374.00 1374.00 1374.00 1374.00 1374.00 1374.00 1374.00 1374.00
 1374.00 1374.00 1374.00 1374.00 1374.00 1374.00
  4768.5  4790.4  4806.8  4828.4  4832.8  4851.0  4859.6  4871.1  4876.7  4887.6
  4891.5  4905.4  4908.9  4939.7  4945.4  4955.8  4958.8  4965.9  4970.8  5007.0
  5008.2  5019.9  5026.3  5040.9  5043.7  5065.0  5076.7  5084.5  5099.7  5110.9
  5143.4  5146.7  5167.5  5182.3  5193.8  5205.7  5219.5  5242.7  5259.3  5265.9
  5273.3  5312.0  5314.8  5329.6  5336.1  5345.4  5359.0  5372.9  5385.1  5399.6
  5406.0  5412.5  5418.9  5429.5  5450.7  5452.5
 1426.97 1426.60 1424.38 1418.90 1417.33 1412.07 1410.88 1407.42 1406.35 1405.99
 1405.78 1405.50 1405.85 1404.67 1403.94 1402.30 1401.92 1400.28 1400.00 1400.00
 1400.12 1400.23 1400.41 1401.00 1401.05 1400.72 1401.40 1401.66 1401.52 1401.64
 1402.68 1402.92 1403.79 1404.12 1404.23 1404.04 1404.40 1405.14 1405.18 1405.43
 1405.58 1405.54 1405.68 1406.93 1407.34 1407.60 1408.20 1408.99 1409.90 1411.14
 1411.82 1412.68 1413.41 1414.49 1415.65 1415.91
 1373.83 1373.83 1373.83 1373.83 1373.83 1373.83 1373.83 1373.83 1373.83 1373.83
 1373.83 1373.83 1373.83 1373.83 1373.83 1373.83 1373.83 1373.83 1373.83 1373.83
 1373.83 1373.83 1373.83 1373.83 1373.83 1373.83 1373.83 1373.83 1373.83 1373.83
 1373.83 1373.83 1373.83 1373.83 1373.83 1373.83 1373.83 1373.83 1373.83 1373.83
 1373.83 1373.83 1373.83 1373.83 1373.83 1373.83 1373.83 1373.83 1373.83 1373.83
 1373.83 1373.83 1373.83 1373.83 1373.83 1373.83
Culvert=1,4,,35,0.024,0.9,1,2,3,1394,5000,1393.83,5000,Culvert #1,0,2.5
Culvert Bottom n=0.024
Culvert Bottom Depth=0
Culvert Depth Blocked=0
BC Design=,,0,,0,,,,,,

Type RM Length L Ch R = 1,79861,313,313,313
BEGIN DESCRIPTION:
Private Culvert 3 DS
END DESCRIPTION:
XS GIS Cut Line= 4
      1430146.32       964112.20      1430061.16       964081.16
      1429753.20       964221.16      1429527.49       964186.44
#Sta/Elev= 30
  4773.5 1425.97  4791.0 1423.15  4812.1 1418.79  4835.6 1410.43  4857.8 1407.41
  4872.2 1404.67  4882.8 1404.73  4907.9 1402.78  4931.5 1401.71  4960.4 1399.10
  4980.6 1399.17  4984.7 1398.24  4993.0 1395.18  4995.0 1393.83  5005.0 1393.83
  5007.0 1395.18  5009.7 1397.92  5021.5 1400.11  5055.6 1400.29  5089.7 1401.19
  5118.5 1402.92  5145.0 1403.69  5193.8 1403.97  5219.7 1404.88  5288.4 1405.70
  5321.0 1407.14  5369.0 1410.33  5393.1 1413.22  5417.2 1414.93  5430.8 1416.59
#Mann=3,-1,0
  4773.5    0.08       0  4993.0    0.05       0  5007.0    0.08       0
#XS Ineff=2,0
    0.00 4993.00 1400.00 5007.00    0.00 1400.00
Permanent Ineff=
       F       F
Bank Sta=4993,5007
XS Rating Curve= 0
Exp/Cntr=0.5,0.3

Type RM Length L Ch R = 1,79548,308,308,308
BEGIN DESCRIPTION:
South Fork 265.0
END DESCRIPTION:
XS GIS Cut Line= 3
      1430251.38       963895.46      1429863.39       963873.63
      1429589.94       963852.06
#Sta/Elev= 30
  4611.4 1421.95  4627.8 1419.99  4644.2 1415.89  4653.0 1413.57  4677.7 1403.68
  4703.3 1398.09  4738.6 1396.95  4776.3 1396.84  4801.0 1396.32  4846.7 1396.98
  4860.9 1396.21  4893.4 1396.22  4917.0 1396.67  4933.9 1395.66  4940.4 1393.59
  4965.1 1390.44  4990.0 1392.43  4994.5 1389.32  4996.6 1386.32  5003.4 1386.32
  5005.5 1389.32  5006.4 1391.75  5022.6 1395.90  5038.9 1398.49  5063.6 1398.32
  5174.8 1401.25  5216.8 1403.67  5250.2 1406.73  5263.3 1408.62  5274.3 1411.63
#Mann=4,-1,0
  4611.4    0.08       0  4994.5    0.05       0  5005.5    0.08       0
  5250.2    0.14       0
Bank Sta=4994.5,5005.5
XS Rating Curve= 0
Exp/Cntr=0.3,0.1

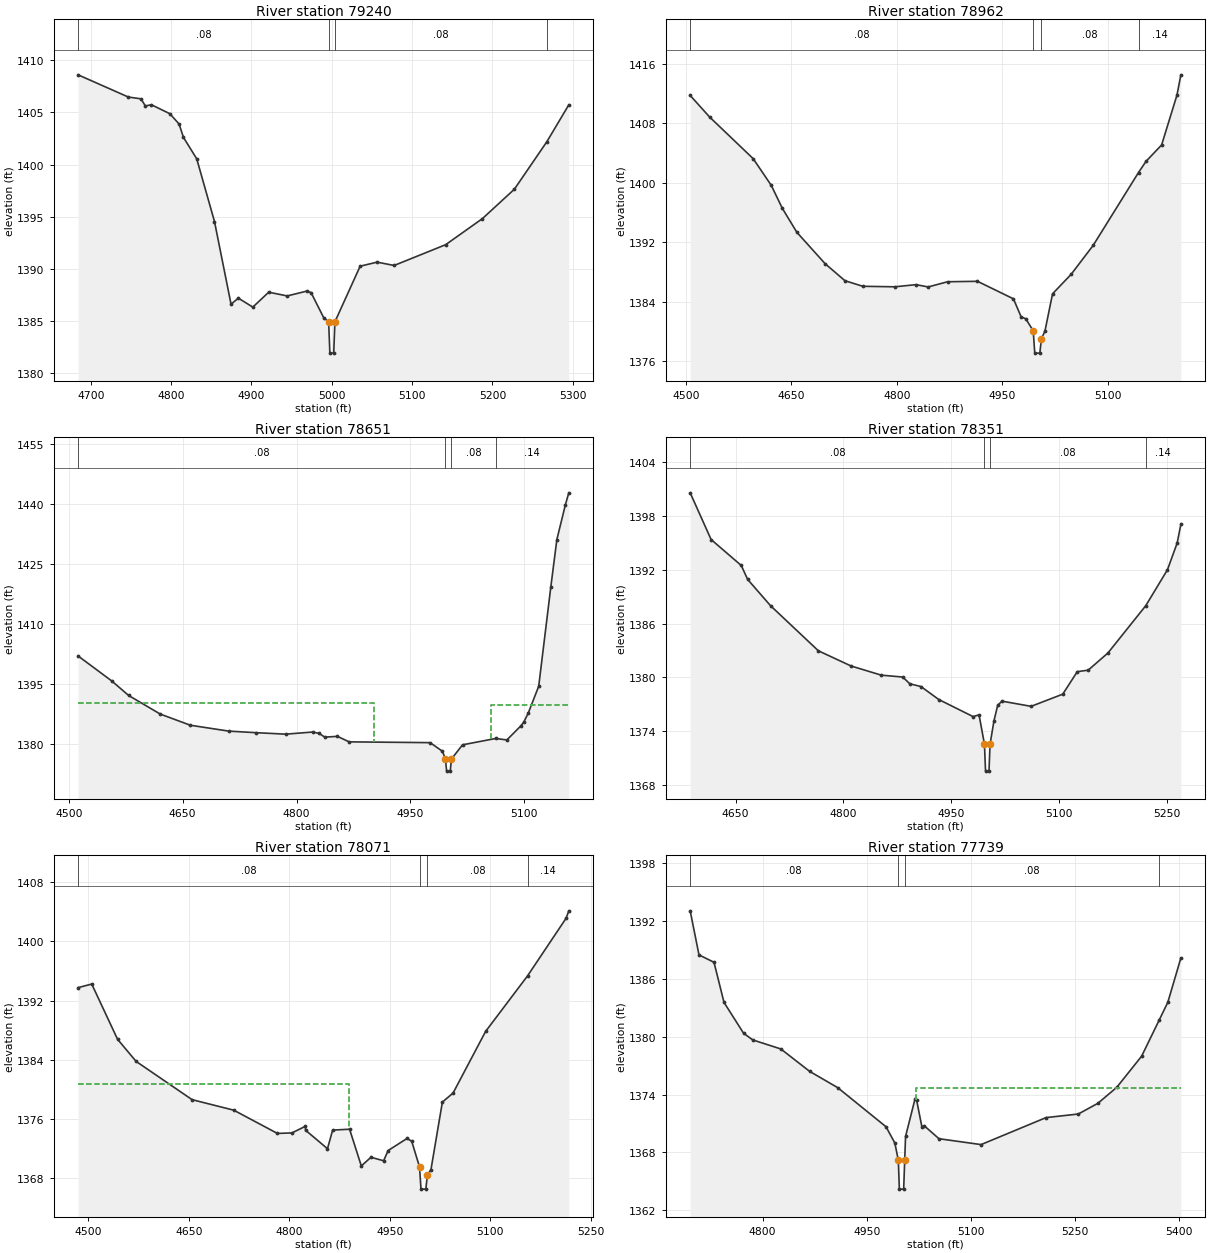
Type RM Length L Ch R = 1,79240,278,278,278
BEGIN DESCRIPTION:
South Fork 264.0
END DESCRIPTION:
XS GIS Cut Line= 3
      1430237.53       963680.19      1430030.92       963607.27
      1429642.04       963560.40
#Sta/Elev= 30
  4684.2 1408.60  4746.8 1406.47  4762.5 1406.30  4767.9 1405.62  4775.5 1405.73
  4798.3 1404.88  4809.9 1403.89  4815.4 1402.60  4831.9 1400.55  4854.0 1394.54
  4874.6 1386.62  4883.7 1387.20  4901.7 1386.34  4921.5 1387.77  4944.5 1387.41
  4969.2 1387.88  4974.2 1387.73  4989.9 1385.33  4996.1 1384.93  4997.6 1381.93
  5002.4 1381.93  5003.9 1384.93  5035.3 1390.26  5056.4 1390.65  5077.6 1390.33
  5141.7 1392.32  5187.5 1394.82  5227.3 1397.64  5267.7 1402.19  5295.0 1405.72
#Mann=4,-1,0
  4684.2    0.08       0  4996.1    0.05       0  5003.9    0.08       0
  5267.7    0.14       0
Bank Sta=4996.1,5003.9
XS Rating Curve= 0
Exp/Cntr=0.3,0.1

Type RM Length L Ch R = 1,78962,311,311,311
BEGIN DESCRIPTION:
South Fork 263.0
END DESCRIPTION:
XS GIS Cut Line= 4
      1430331.24       963501.35      1430185.43       963376.37
      1429834.94       963350.99      1429680.26       963355.53
#Sta/Elev= 30
  4506.1 1411.72  4533.8 1408.81  4595.8 1403.21  4621.5 1399.62  4637.3 1396.52
  4657.9 1393.31  4698.1 1389.09  4726.3 1386.80  4751.7 1386.05  4797.2 1385.98
  4827.7 1386.27  4844.7 1385.96  4872.4 1386.66  4914.9 1386.72  4966.1 1384.36
  4977.0 1381.94  4983.6 1381.68  4994.2 1380.06  4996.4 1377.06  5003.6 1377.06
  5005.9 1379.00  5010.9 1380.03  5021.7 1385.04  5048.0 1387.64  5079.5 1391.55
  5144.0 1401.35  5154.7 1402.85  5176.9 1405.06  5198.7 1411.75  5204.3 1414.49
#Mann=4,-1,0
  4506.1    0.08       0  4994.2    0.05       0  5005.9    0.08       0
  5144.0    0.14       0
Bank Sta=4994.2,5005.9
XS Rating Curve= 0
Exp/Cntr=0.3,0.1

Type RM Length L Ch R = 1,78651,300,300,300
BEGIN DESCRIPTION:
South Fork 262.0
END DESCRIPTION:
XS GIS Cut Line= 3
      1430319.08       963388.49      1430220.16       963296.51
      1429831.23       962964.88
#Sta/Elev= 30
  4512.3 1402.05  4556.4 1395.84  4578.9 1392.18  4620.5 1387.54  4660.1 1384.75
  4710.7 1383.28  4746.5 1382.89  4785.7 1382.52  4821.2 1383.05  4829.6 1382.72
  4837.2 1381.78  4853.9 1381.97  4869.2 1380.60  4975.9 1380.40  4992.1 1378.25
  4996.1 1376.29  4997.6 1373.29  5002.4 1373.29  5003.9 1376.29  5018.6 1379.86
  5062.2 1381.44  5077.0 1381.08  5095.2 1384.55  5099.3 1385.55  5105.1 1387.77
  5118.9 1394.48  5134.8 1419.22  5142.8 1431.11  5154.0 1439.78  5158.5 1442.78
#Mann=4,-1,0
  4512.3    0.08       0  4996.1    0.05       0  5003.9    0.08       0
  5062.2    0.14       0
#XS Ineff=2,0
    0.00 4901.40 1390.18 5056.60    0.00 1389.90
Permanent Ineff=
       F       F
Bank Sta=4996.1,5003.9
XS Rating Curve= 0
Exp/Cntr=0.3,0.1

Type RM Length L Ch R = 1,78351,280,280,280
BEGIN DESCRIPTION:
South Fork 261.0
END DESCRIPTION:
XS GIS Cut Line= 5
      1430334.74       963374.64      1430294.48       963094.66
      1430235.78       962999.63      1430150.85       962909.12
      1430011.79       962822.52
#Sta/Elev= 30
  4586.8 1400.59  4615.9 1395.38  4657.9 1392.48  4666.7 1390.93  4698.6 1387.99
  4765.1 1382.96  4810.7 1381.26  4852.7 1380.24  4882.5 1380.03  4892.2 1379.28
  4907.8 1378.97  4932.6 1377.52  4980.2 1375.62  4988.6 1375.81  4996.1 1372.53
  4997.6 1369.53  5002.4 1369.53  5003.9 1372.53  5009.3 1375.13  5014.5 1376.88
  5020.5 1377.34  5061.0 1376.76  5105.0 1378.12  5125.2 1380.63  5140.4 1380.80
  5167.8 1382.71  5220.5 1388.00  5250.6 1392.00  5264.1 1394.98  5269.3 1397.08
#Mann=4,-1,0
  4586.8    0.08       0  4996.1    0.05       0  5003.9    0.08       0
  5220.5    0.14       0
Bank Sta=4996.1,5003.9
XS Rating Curve= 0
Exp/Cntr=0.3,0.1

Type RM Length L Ch R = 1,78071,332,332,332
BEGIN DESCRIPTION:
South Fork 260.0
END DESCRIPTION:
XS GIS Cut Line= 4
      1430610.68       963103.43      1430590.70       963005.35
      1430246.20       962801.71      1430048.30       962680.20
#Sta/Elev= 30
  4484.5 1393.76  4504.9 1394.24  4543.4 1386.79  4571.1 1383.80  4654.7 1378.63
  4716.9 1377.21  4782.1 1374.07  4803.8 1374.14  4823.9 1375.04  4824.0 1374.51
  4856.8 1372.01  4864.5 1374.52  4889.8 1374.64  4907.3 1369.68  4921.7 1370.85
  4940.6 1370.38  4947.3 1371.76  4975.5 1373.39  4982.5 1373.02  4994.2 1369.55
  4996.4 1366.55  5003.6 1366.55  5005.9 1368.40  5011.3 1369.20  5028.3 1378.30
  5044.3 1379.53  5092.8 1387.84  5155.4 1395.34  5213.0 1403.13  5217.0 1404.13
#Mann=4,-1,0
  4484.5    0.08       0  4994.2    0.05       0  5005.9    0.08       0
  5155.4    0.14       0
#XS Ineff=2,0
    0.00 4889.10 1380.81               0
Permanent Ineff=
       F       F
Bank Sta=4994.2,5005.9
XS Rating Curve= 0
Exp/Cntr=0.3,0.1

Type RM Length L Ch R = 1,77739,323,323,323
BEGIN DESCRIPTION:
South Fork 259.0
END DESCRIPTION:
XS GIS Cut Line= 4
      1430721.90       962947.55      1430570.44       962851.47
      1430518.77       962584.70      1430306.95       962442.33
#Sta/Elev= 30
  4695.8 1393.07  4708.5 1388.50  4730.1 1387.73  4744.5 1383.57  4772.6 1380.38
  4785.8 1379.68  4826.3 1378.74  4867.7 1376.42  4908.3 1374.72  4977.7 1370.67
  4990.4 1368.98  4995.4 1367.20  4996.9 1364.20  5003.1 1364.20  5004.6 1367.20
  5005.8 1369.66  5019.6 1373.60  5021.8 1373.41  5029.3 1370.67  5032.6 1370.78
  5053.9 1369.43  5114.5 1368.82  5208.0 1371.62  5254.4 1371.99  5282.6 1373.10
  5309.8 1374.76  5345.6 1377.99  5371.1 1381.77  5383.3 1383.58  5402.1 1388.18
#Mann=4,-1,0
  4695.8    0.08       0  4995.4    0.05       0  5004.6    0.08       0
  5371.1    0.14       0
#XS Ineff=2,0
       0                 5021.30    0.00 1374.68
Permanent Ineff=
       F       F
Bank Sta=4995.4,5004.6
XS Rating Curve= 0
Exp/Cntr=0.3,0.1

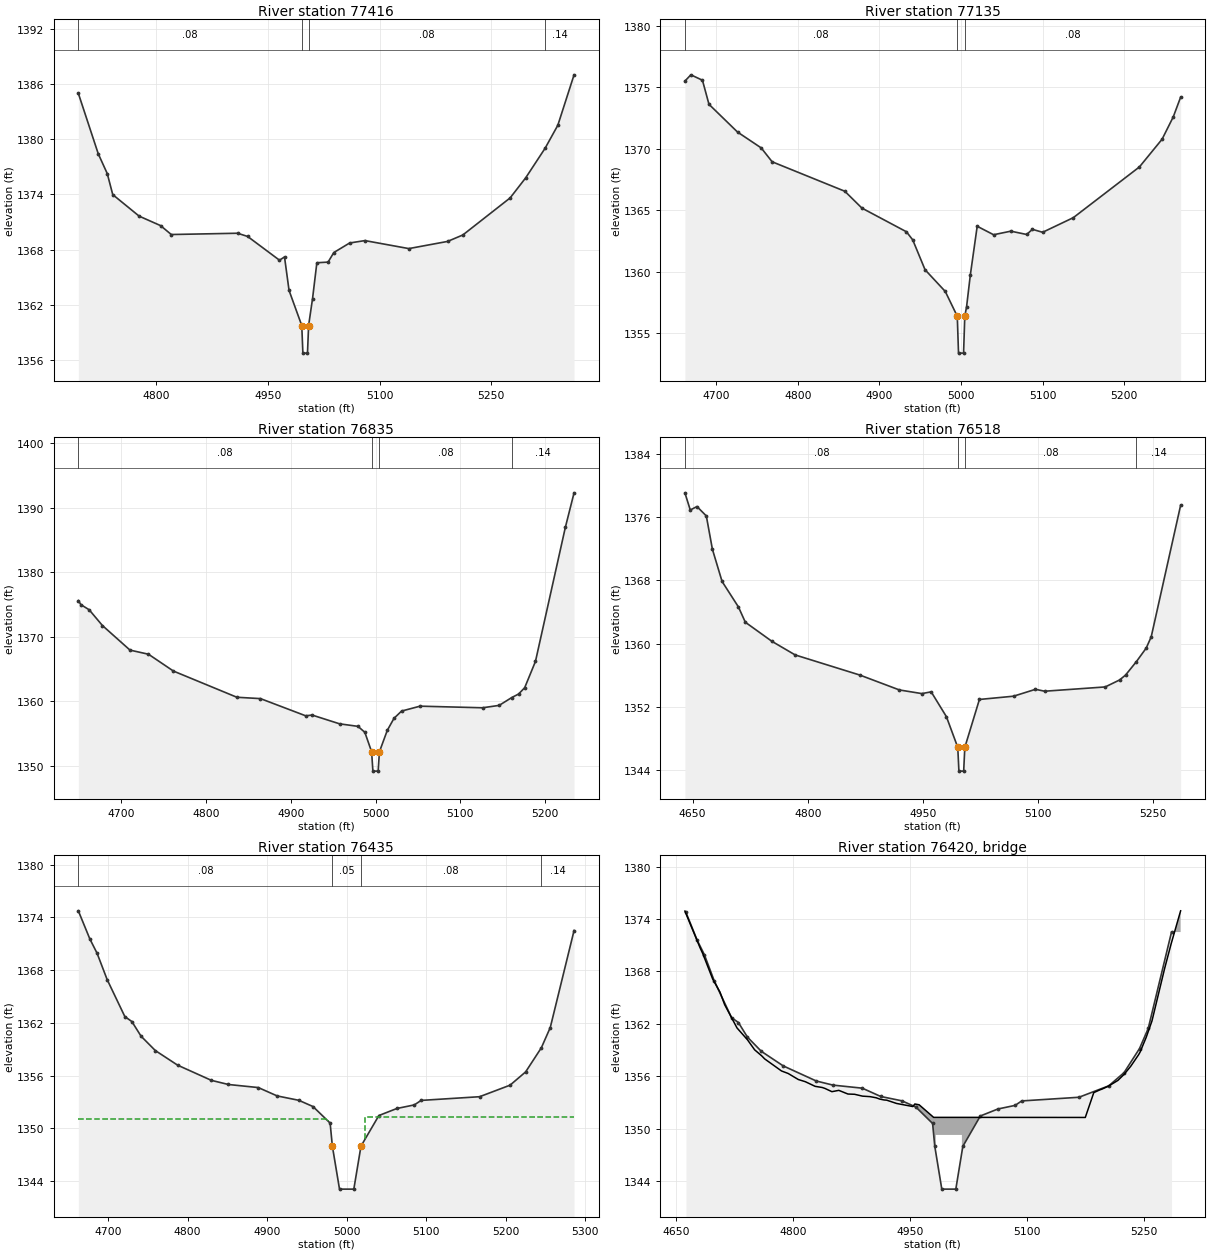
Type RM Length L Ch R = 1,77416,281,281,281
BEGIN DESCRIPTION:
South Fork 258.0
END DESCRIPTION:
XS GIS Cut Line= 3
      1430970.15       962645.46      1430708.00       962537.83
      1430352.10       962395.46
#Sta/Elev= 30
  4694.9 1385.00  4721.7 1378.42  4733.8 1376.27  4741.2 1373.98  4776.7 1371.64
  4805.5 1370.61  4819.9 1369.64  4909.1 1369.78  4922.6 1369.43  4965.4 1366.85
  4972.2 1367.20  4978.3 1363.56  4995.4 1359.74  4996.9 1356.74  5003.1 1356.74
  5004.6 1359.74  5009.9 1362.67  5015.7 1366.57  5030.8 1366.64  5038.5 1367.68
  5059.8 1368.72  5080.3 1368.98  5139.4 1368.11  5191.5 1368.89  5212.0 1369.59
  5275.6 1373.62  5296.5 1375.80  5322.7 1379.03  5339.8 1381.53  5361.6 1387.01
#Mann=4,-1,0
  4694.9    0.08       0  4995.4    0.05       0  5004.6    0.08       0
  5322.7    0.14       0
Bank Sta=4995.4,5004.6
XS Rating Curve= 0
Exp/Cntr=0.3,0.1

Type RM Length L Ch R = 1,77135,300,300,300
BEGIN DESCRIPTION:
South Fork 257.0
END DESCRIPTION:
XS GIS Cut Line= 3
      1431076.03       962482.25      1430802.09       962283.58
      1430581.24       962129.82
#Sta/Elev= 30
  4661.6 1375.52  4668.9 1376.03  4683.1 1375.59  4691.1 1373.63  4726.1 1371.37
  4755.1 1370.08  4768.5 1368.95  4857.6 1366.55  4878.5 1365.18  4933.1 1363.25
  4940.8 1362.59  4955.9 1360.16  4980.7 1358.39  4995.4 1356.37  4996.9 1353.37
  5003.1 1353.37  5004.6 1356.37  5006.8 1357.15  5011.4 1359.74  5019.8 1363.70
  5039.9 1363.01  5061.0 1363.30  5080.5 1363.03  5087.4 1363.45  5100.0 1363.21
  5137.6 1364.40  5218.6 1368.53  5246.4 1370.79  5260.1 1372.61  5269.1 1374.21
#Mann=3,-1,0
  4661.6    0.08       0  4995.4    0.05       0  5004.6    0.08       0
Bank Sta=4995.4,5004.6
XS Rating Curve= 0
Exp/Cntr=0.3,0.1

Type RM Length L Ch R = 1,76835,317,317,317
BEGIN DESCRIPTION:
South Fork 256.0
END DESCRIPTION:
XS GIS Cut Line= 3
      1431289.62       962247.90      1430991.12       962064.58
      1430794.85       961937.16
#Sta/Elev= 30
  4649.7 1375.60  4652.8 1374.97  4662.5 1374.18  4678.1 1371.74  4710.6 1367.93
  4732.4 1367.29  4761.8 1364.68  4836.6 1360.62  4864.4 1360.41  4917.6 1357.75
  4925.3 1357.86  4957.7 1356.50  4979.3 1356.11  4987.4 1355.19  4995.4 1352.17
  4996.9 1349.17  5003.1 1349.17  5004.6 1352.17  5013.9 1355.50  5021.8 1357.36
  5030.7 1358.48  5052.5 1359.24  5126.1 1358.99  5145.7 1359.36  5160.5 1360.57
  5168.6 1361.12  5175.8 1362.10  5188.5 1366.17  5223.8 1386.99  5234.0 1392.31
#Mann=4,-1,0
  4649.7    0.08       0  4995.4    0.05       0  5004.6    0.08       0
  5160.5    0.14       0
Bank Sta=4995.4,5004.6
XS Rating Curve= 0
Exp/Cntr=0.3,0.1

Type RM Length L Ch R = 1,76518,83,83,83
BEGIN DESCRIPTION:
South Fork 255.0
END DESCRIPTION:
XS GIS Cut Line= 3
      1431492.77       961978.82      1431187.17       961817.34
      1430923.26       961674.97
#Sta/Elev= 30
  4640.1 1379.06  4647.1 1376.89  4655.8 1377.33  4668.0 1376.14  4675.9 1371.94
  4688.5 1367.87  4709.8 1364.65  4718.8 1362.72  4753.4 1360.31  4783.7 1358.59
  4867.9 1356.05  4919.4 1354.17  4948.6 1353.71  4960.8 1353.93  4980.6 1350.80
  4995.4 1346.92  4996.9 1343.92  5003.1 1343.92  5004.6 1346.92  5023.6 1352.97
  5068.0 1353.38  5096.6 1354.25  5108.6 1354.01  5187.4 1354.55  5206.1 1355.43
  5213.9 1356.05  5228.1 1357.76  5240.8 1359.46  5247.3 1360.88  5285.6 1377.49
#Mann=4,-1,0
  4640.1    0.08       0  4995.4    0.05       0  5004.6    0.08       0
  5228.1    0.14       0
Bank Sta=4995.4,5004.6
XS Rating Curve= 0
Exp/Cntr=0.5,0.3

Type RM Length L Ch R = 1,76435,27,27,27
BEGIN DESCRIPTION:
LDS_SFMR_08 US
END DESCRIPTION:
XS GIS Cut Line= 2
      1431531.26       961851.16      1430943.78       961642.89
#Sta/Elev= 30
  4662.6 1374.75  4677.0 1371.57  4686.2 1369.92  4698.8 1366.94  4721.1 1362.72
  4729.9 1362.16  4741.5 1360.49  4759.4 1358.86  4787.4 1357.20  4829.9 1355.47
  4851.3 1355.00  4888.9 1354.65  4912.6 1353.70  4939.9 1353.20  4957.7 1352.49
  4979.2 1350.61  4982.0 1347.99  4991.0 1343.10  5009.0 1343.10  5018.0 1347.99
  5040.5 1351.47  5063.1 1352.27  5085.1 1352.68  5093.6 1353.19  5167.1 1353.61
  5205.4 1354.92  5225.0 1356.43  5244.8 1359.18  5256.0 1361.48  5285.9 1372.51
#Mann=4,-1,0
  4662.6    0.08       0  4982.0    0.05       0  5018.0    0.08       0
  5244.8    0.14       0
#XS Ineff=2,0
    0.00 4976.80 1351.03 5023.10    0.00 1351.31
Permanent Ineff=
       F       F
Bank Sta=4982,5018
XS Rating Curve= 0
Exp/Cntr=0.5,0.3

Type RM Length L Ch R =3,76420,,,
BEGIN DESCRIPTION:
LDS_SFMR_08 TOR
Structure ID: LDS_SFMR_08
Approximate Survey Structure
END DESCRIPTION:
Bridge Culvert--1,0,-1,-1,0
Deck Dist Width WeirC Skew NumUp NumDn MinLoCord MaxHiCord MaxSubmerge Is_Ogee
6.5,17,3,,52,52,,,0.95,0,1,1,,,
  4661.2  4680.7  4684.2  4696.8  4706.2  4712.2  4728.1  4741.5  4750.7  4759.9
  4763.6  4785.2  4793.8  4806.8  4815.8  4828.4  4837.4  4841.0  4849.9  4858.8
  4870.5  4879.1  4889.1  4899.0  4906.8  4911.4  4917.0  4920.2  4933.0  4953.8
  4956.4  4961.9  4980.5  4983.3  4983.3  5016.8  5016.8  5175.2  5186.1  5193.7
  5196.3  5205.3  5217.1  5225.0  5233.5  5243.6  5245.5  5253.5  5260.8  5277.1
  5285.3  5297.6
 1374.91 1370.71 1370.03 1367.15 1365.65 1364.21 1361.54 1360.19 1359.04 1358.34
 1358.00 1356.62 1356.33 1355.64 1355.39 1354.86 1354.73 1354.62 1354.25 1354.40
 1353.98 1353.95 1353.74 1353.68 1353.55 1353.40 1353.30 1353.28 1352.90 1352.55
 1352.84 1352.75 1351.31 1351.31 1351.31 1351.31 1351.31 1351.30 1354.14 1354.45
 1354.53 1354.90 1355.54 1356.23 1357.15 1358.47 1358.77 1360.49 1362.34 1368.36
 1371.13 1374.94
 1323.10 1323.10 1323.10 1323.10 1323.10 1323.10 1323.10 1323.10 1323.10 1323.10
 1323.10 1323.10 1323.10 1323.10 1323.10 1323.10 1323.10 1323.10 1323.10 1323.10
 1323.10 1323.10 1323.10 1323.10 1323.10 1323.10 1323.10 1323.10 1323.10 1323.10
 1323.10 1323.10 1323.10 1323.10 1349.30 1349.30 1323.10 1323.10 1323.10 1323.10
 1323.10 1323.10 1323.10 1323.10 1323.10 1323.10 1323.10 1323.10 1323.10 1323.10
 1323.10 1323.10
  4661.2  4680.7  4684.2  4696.8  4706.2  4712.2  4728.1  4741.5  4750.7  4759.9
  4763.6  4785.2  4793.8  4806.8  4815.8  4828.4  4837.4  4841.0  4849.9  4858.8
  4870.5  4879.1  4889.1  4899.0  4906.8  4911.4  4917.0  4920.2  4933.0  4953.8
  4956.4  4961.9  4980.5  4983.3  4983.3  5016.8  5016.8  5175.2  5186.1  5193.7
  5196.3  5205.3  5217.1  5225.0  5233.5  5243.6  5245.5  5253.5  5260.8  5277.1
  5285.3  5297.6
 1374.91 1370.71 1370.03 1367.15 1365.65 1364.21 1361.54 1360.19 1359.04 1358.34
 1358.00 1356.62 1356.33 1355.64 1355.39 1354.86 1354.73 1354.62 1354.25 1354.40
 1353.98 1353.95 1353.74 1353.68 1353.55 1353.40 1353.30 1353.28 1352.90 1352.55
 1352.84 1352.75 1351.31 1351.31 1351.31 1351.31 1351.31 1351.30 1354.14 1354.45
 1354.53 1354.90 1355.54 1356.23 1357.15 1358.47 1358.77 1360.49 1362.34 1368.36
 1371.13 1374.94
 1323.10 1323.10 1323.10 1323.10 1323.10 1323.10 1323.10 1323.10 1323.10 1323.10
 1323.10 1323.10 1323.10 1323.10 1323.10 1323.10 1323.10 1323.10 1323.10 1323.10
 1323.10 1323.10 1323.10 1323.10 1323.10 1323.10 1323.10 1323.10 1323.10 1323.10
 1323.10 1323.10 1323.10 1323.10 1349.30 1349.30 1323.10 1323.10 1323.10 1323.10
 1323.10 1323.10 1323.10 1323.10 1323.10 1323.10 1323.10 1323.10 1323.10 1323.10
 1323.10 1323.10
Abutment Skew #Up #Dn=,2,2
  4983.3  4984.3
 1349.30 1347.53
  4983.3  4984.3
 1349.30 1347.08
Abutment Skew #Up #Dn=,2,2
  5015.8  5016.8
 1347.42 1349.30
  5015.8  5016.8
 1347.17 1349.30
BR Coef=1,1,0,1.25,0,,,0.8,0,2,0,
WSPro=,,,, 1 ,,,, 0 ,,,, 0 ,,,,-1 ,-1 ,-1 , 0 , 0 , 0 , 0 , 0
BC Design=,,0,,0,,,,,,