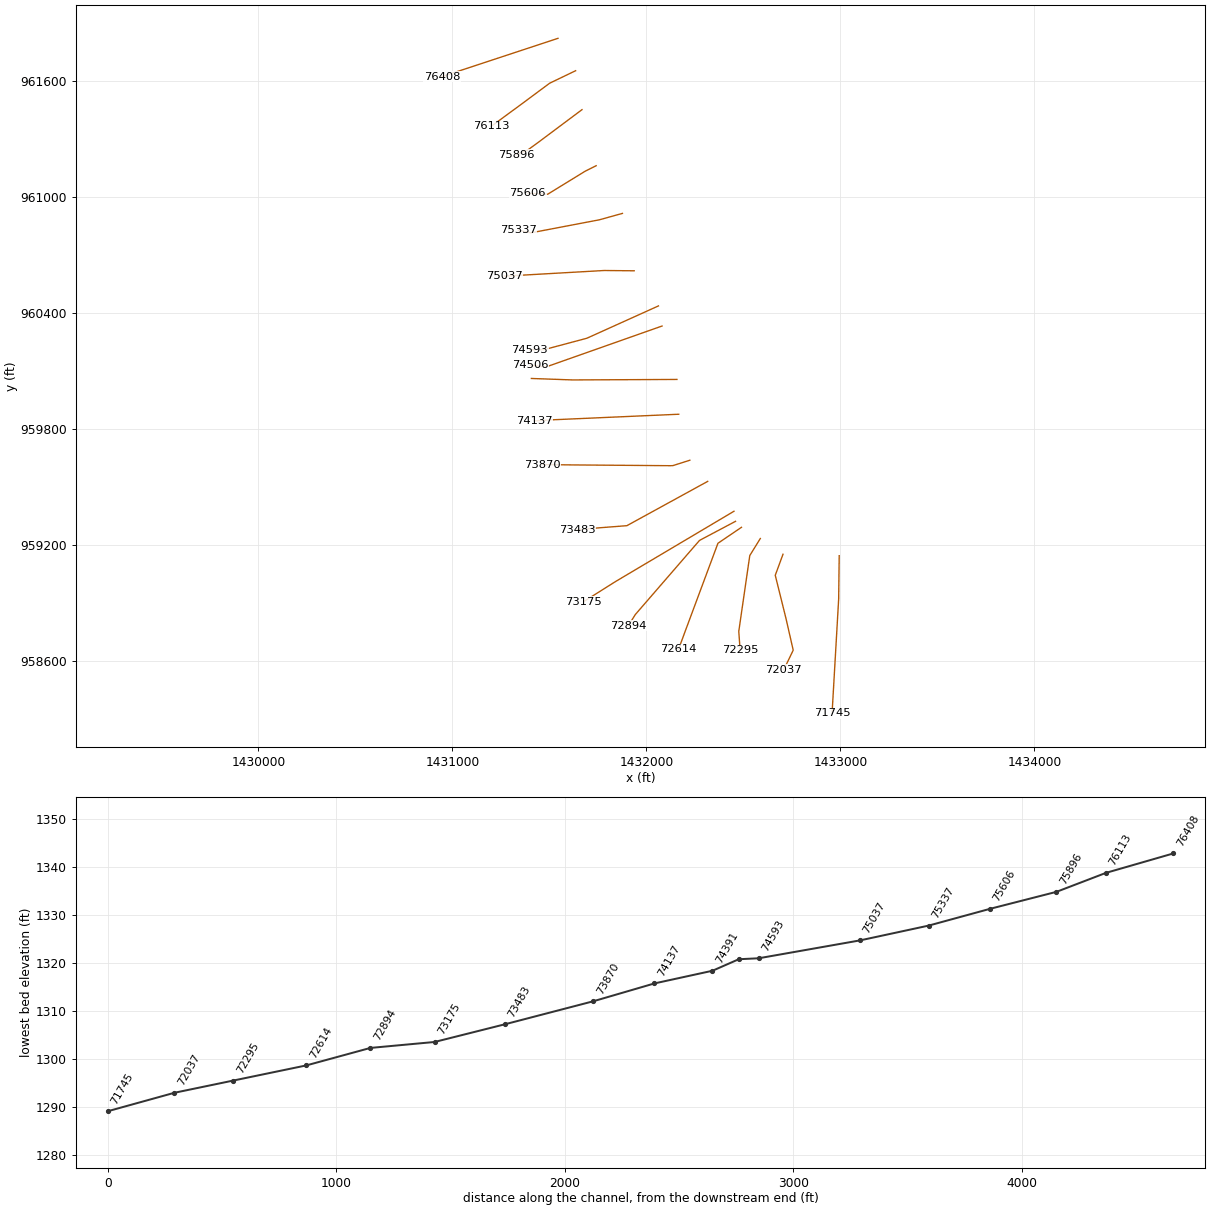
HEC-RAS study South Fork.prj: South Fork Limited Detail Study

--- South Fork.g01 (geometry) --- (continued)

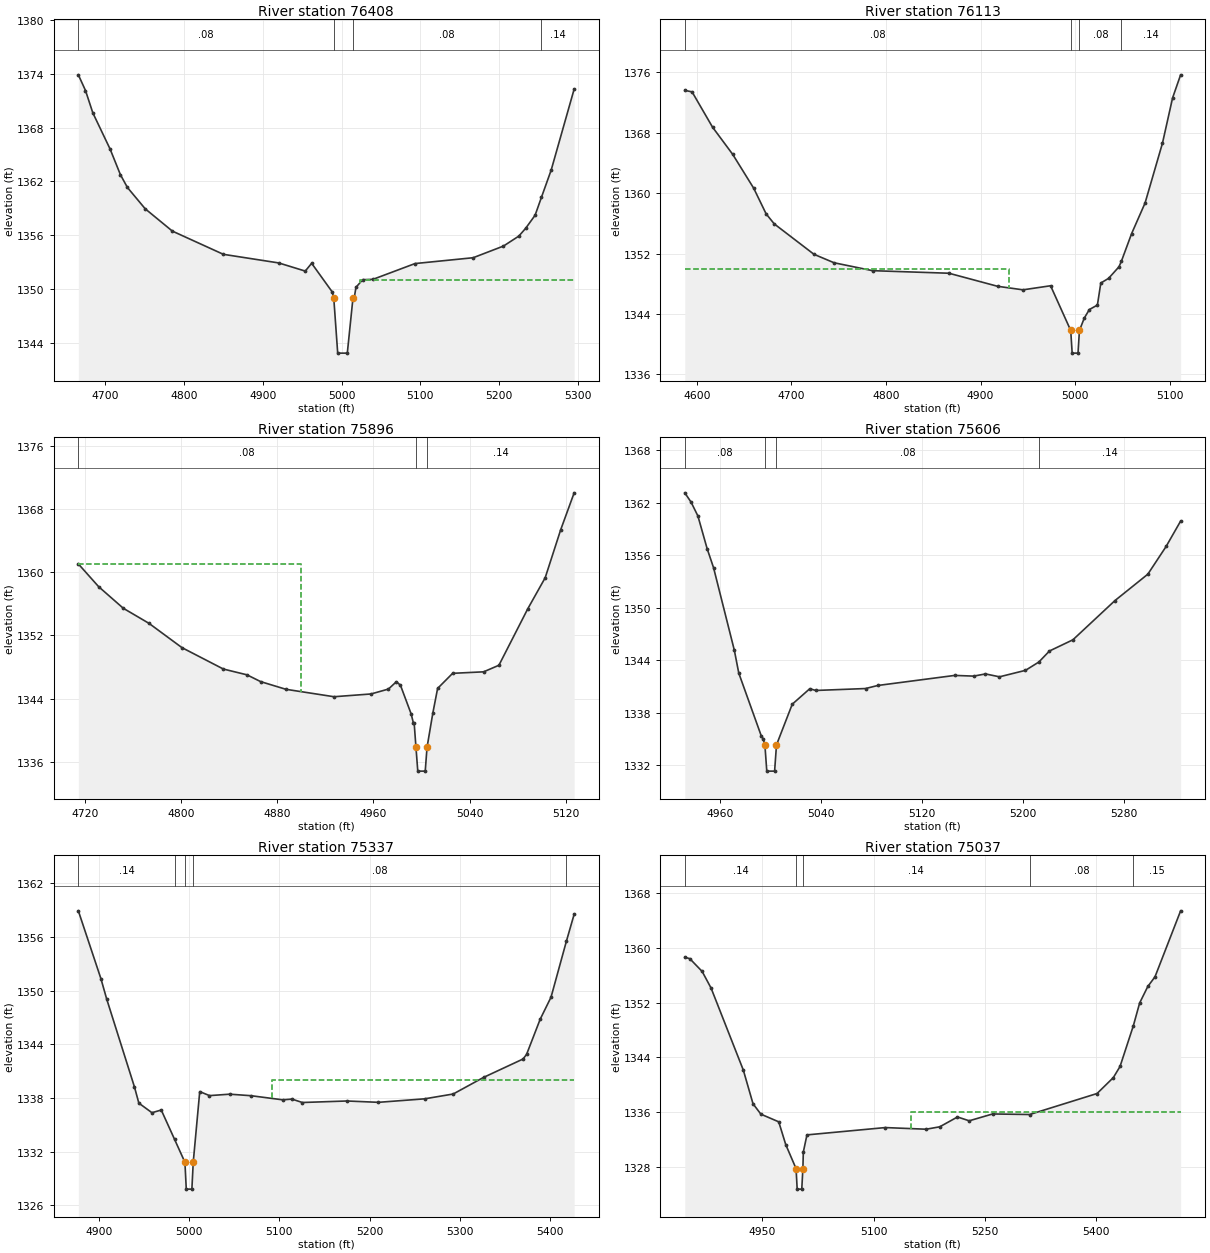
Type RM Length L Ch R = 1,76408,295,295,295
BEGIN DESCRIPTION:
LDS_SFMR_08 DS
END DESCRIPTION:
XS GIS Cut Line= 2
      1431544.26       961819.92      1430946.44       961622.09
#Sta/Elev= 30
  4665.6 1373.89  4674.7 1372.14  4684.0 1369.65  4706.0 1365.60  4719.0 1362.76
  4727.9 1361.33  4750.5 1358.95  4785.0 1356.46  4849.8 1353.87  4920.1 1352.91
  4953.8 1352.00  4961.9 1352.87  4988.1 1349.67  4990.0 1349.00  4995.0 1342.85
  5007.2 1342.85  5014.4 1349.00  5016.2 1349.13  5018.2 1350.19  5026.7 1351.04
  5039.8 1351.08  5093.2 1352.84  5167.0 1353.49  5205.5 1354.79  5225.0 1355.90
  5233.7 1356.77  5245.7 1358.23  5253.8 1360.24  5266.1 1363.26  5295.3 1372.30
#Mann=4,-1,0
  4665.6    0.08       0  4990.0    0.05       0  5014.4    0.08       0
  5253.8    0.14       0
#XS Ineff=2,0
    0.00 4976.80 1351.00 5023.10    0.00 1351.00
Permanent Ineff=
       F       F
Bank Sta=4990,5014.4
XS Rating Curve= 0
Exp/Cntr=0.5,0.3

Type RM Length L Ch R = 1,76113,217,217,217
BEGIN DESCRIPTION:
South Fork 254.0
END DESCRIPTION:
XS GIS Cut Line= 4
      1431635.12       961652.42      1431501.28       961587.75
      1431357.31       961480.53      1431199.36       961364.24
#Sta/Elev= 30
  4587.3 1373.63  4595.0 1373.43  4616.6 1368.76  4638.0 1365.14  4660.2 1360.65
  4673.3 1357.26  4681.9 1355.93  4723.9 1351.90  4745.1 1350.78  4785.8 1349.73
  4866.6 1349.39  4918.0 1347.66  4944.9 1347.19  4974.1 1347.73  4995.4 1341.80
  4996.9 1338.80  5003.1 1338.80  5004.6 1341.80  5009.7 1343.44  5015.1 1344.58
  5023.6 1345.17  5027.2 1348.09  5035.4 1348.71  5046.4 1350.24  5049.0 1350.99
  5059.8 1354.65  5074.0 1358.70  5092.4 1366.63  5103.1 1372.63  5111.6 1375.69
#Mann=4,-1,0
  4587.3    0.08       0  4995.4    0.05       0  5004.6    0.08       0
  5049.0    0.14       0
#XS Ineff=2,0
    0.00 4930.00 1350.00               0
Permanent Ineff=
       F       F
Bank Sta=4995.4,5004.6
XS Rating Curve= 0
Exp/Cntr=0.3,0.1

Type RM Length L Ch R = 1,75896,290,290,290
BEGIN DESCRIPTION:
South Fork 253.0
END DESCRIPTION:
XS GIS Cut Line= 4
      1431668.05       961451.00      1431445.85       961284.35
      1431386.68       961241.15      1431329.56       961218.39
#Sta/Elev= 30
  4714.5 1361.05  4731.4 1358.17  4751.9 1355.44  4773.3 1353.53  4800.7 1350.46
  4835.2 1347.75  4854.8 1347.02  4866.2 1346.16  4887.2 1345.19  4927.2 1344.25
  4958.0 1344.60  4972.5 1345.22  4979.1 1346.15  4982.5 1345.70  4991.4 1342.07
  4993.2 1340.96  4993.9 1340.89  4995.4 1337.84  4996.9 1334.84  5003.1 1334.84
  5004.6 1337.84  5009.4 1342.16  5013.4 1345.30  5025.9 1347.21  5051.7 1347.40
  5064.4 1348.23  5088.4 1355.37  5102.9 1359.30  5115.8 1365.37  5127.0 1370.04
#Mann=3,-1,0
  4714.5    0.08       0  4995.4    0.05       0  5004.6    0.14       0
#XS Ineff=2,0
    0.00 4900.00 1361.00               0
Permanent Ineff=
       F       F
Bank Sta=4995.4,5004.6
XS Rating Curve= 0
Exp/Cntr=0.3,0.1

Type RM Length L Ch R = 1,75606,269,269,269
BEGIN DESCRIPTION:
South Fork 252.0
END DESCRIPTION:
XS GIS Cut Line= 4
      1431740.98       961161.09      1431685.43       961133.31
      1431490.99       961013.52      1431388.51       961018.73
#Sta/Elev= 30
  4931.9 1363.12  4936.9 1362.05  4942.3 1360.47  4949.6 1356.74  4954.7 1354.56
  4971.2 1345.11  4974.7 1342.51  4992.7 1335.27  4994.0 1335.02  4995.4 1334.31
  4996.9 1331.31  5003.1 1331.31  5004.6 1334.31  5017.1 1338.96  5031.0 1340.73
  5035.7 1340.53  5075.2 1340.75  5084.9 1341.10  5145.9 1342.25  5160.9 1342.17
  5170.3 1342.42  5181.4 1342.09  5202.0 1342.83  5212.6 1343.78  5221.0 1345.04
  5239.6 1346.32  5272.9 1350.80  5299.0 1353.82  5313.5 1356.99  5325.0 1359.89
#Mann=4,-1,0
  4931.9    0.08       0  4995.4    0.05       0  5004.6    0.08       0
  5212.6    0.14       0
Bank Sta=4995.4,5004.6
XS Rating Curve= 0
Exp/Cntr=0.3,0.1

Type RM Length L Ch R = 1,75337,300,300,300
BEGIN DESCRIPTION:
South Fork 251.0
END DESCRIPTION:
XS GIS Cut Line= 4
      1431876.45       960914.57      1431758.38       960881.56
      1431404.18       960813.87      1431339.97       960827.75
#Sta/Elev= 30
  4877.4 1358.91  4902.4 1351.33  4908.8 1349.05  4939.5 1339.24  4944.4 1337.42
  4958.9 1336.35  4969.2 1336.65  4983.9 1333.38  4995.4 1330.81  4996.9 1327.81
  5003.1 1327.81  5004.6 1330.81  5011.8 1338.71  5022.6 1338.26  5045.0 1338.42
  5068.6 1338.25  5103.6 1337.79  5113.9 1337.87  5125.4 1337.49  5174.8 1337.66
  5209.6 1337.51  5260.7 1337.90  5292.4 1338.44  5326.1 1340.30  5369.7 1342.35
  5373.6 1342.86  5388.7 1346.80  5400.7 1349.26  5417.7 1355.51  5426.3 1358.53
#Mann=5,-1,0
  4877.4    0.14       0  4983.9    0.08       0  4995.4    0.05       0
  5004.6    0.08       0  5417.7    0.15       0
#XS Ineff=2,0
       0                 5092.00    0.00 1340.00
Permanent Ineff=
       F       F
Bank Sta=4995.4,5004.6
XS Rating Curve= 0
Exp/Cntr=0.3,0.1

Type RM Length L Ch R = 1,75037,444,444,444
BEGIN DESCRIPTION:
South Fork 250.0
END DESCRIPTION:
XS GIS Cut Line= 3
      1431937.19       960617.69      1431782.40       960619.21
      1431268.73       960589.91
#Sta/Elev= 30
  4845.2 1358.63  4851.9 1358.43  4868.6 1356.56  4880.7 1354.12  4924.2 1342.13
  4937.3 1337.21  4947.9 1335.69  4972.0 1334.57  4981.5 1331.23  4995.4 1327.73
  4996.9 1324.73  5003.1 1324.73  5004.6 1327.73  5005.2 1330.16  5010.1 1332.66
  5115.8 1333.73  5171.0 1333.49  5189.3 1333.84  5213.3 1335.28  5229.1 1334.72
  5260.7 1335.72  5310.8 1335.64  5401.7 1338.71  5423.7 1341.04  5432.7 1342.66
  5450.7 1348.62  5459.2 1351.95  5470.2 1354.36  5479.9 1355.77  5514.5 1365.42
#Mann=5,-1,0
  4845.2    0.14       0  4995.4    0.05       0  5004.6    0.14       0
  5310.8    0.08       0  5450.7    0.15       0
#XS Ineff=2,0
       0                 5150.00    0.00 1336.00
Permanent Ineff=
       F       F
Bank Sta=4995.4,5004.6
XS Rating Curve= 0
Exp/Cntr=0.5,0.3

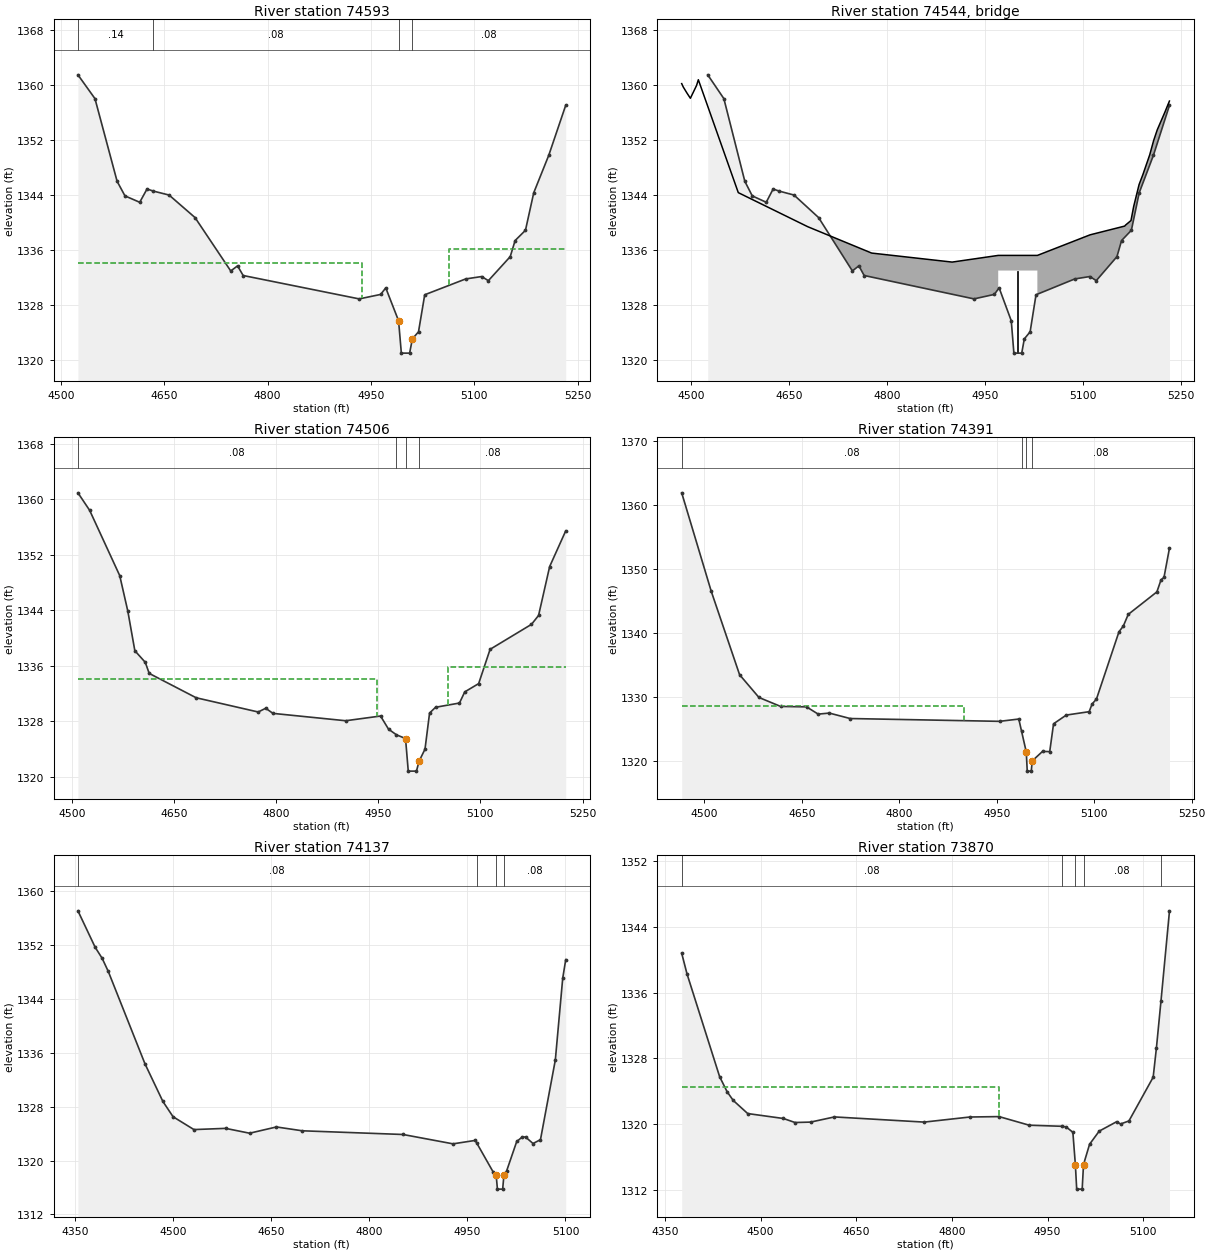
Type RM Length L Ch R = 1,74593,87,87,87
BEGIN DESCRIPTION:
Haystack Rd US
END DESCRIPTION:
XS GIS Cut Line= 4
      1432062.17       960436.07      1431693.36       960268.92
      1431473.77       960210.13      1431398.62       960209.11
#Sta/Elev= 30
  4525.0 1361.44  4549.7 1357.98  4581.8 1345.97  4593.2 1343.85  4614.6 1342.92
  4625.2 1344.85  4634.2 1344.55  4657.2 1343.97  4694.8 1340.70  4746.6 1332.94
  4756.5 1333.68  4764.6 1332.28  4932.9 1328.88  4964.0 1329.53  4971.4 1330.48
  4990.0 1325.70  4994.0 1321.00  5006.0 1321.00  5010.0 1323.07  5018.9 1324.10
  5027.9 1329.48  5087.3 1331.78  5110.5 1332.13  5120.2 1331.53  5151.9 1335.02
  5159.0 1337.36  5174.0 1338.85  5186.0 1344.30  5207.8 1349.75  5232.4 1357.02
#Mann=4,-1,0
  4525.0    0.14       0  4634.2    0.08       0  4990.0    0.05       0
  5010.0    0.08       0
#XS Ineff=2,0
    0.00 4936.50 1334.10 5063.50    0.00 1336.16
Permanent Ineff=
       F       F
Bank Sta=4990,5010
XS Rating Curve= 0
Exp/Cntr=0.5,0.3

Type RM Length L Ch R =3,74544,,,
BEGIN DESCRIPTION:
Haystack Rd TOR
Structure ID: LDS_SFMR_07
Approximate Survey Structure
END DESCRIPTION:
Bridge Culvert--1,0,-1,-1,0
Deck Dist Width WeirC Skew NumUp NumDn MinLoCord MaxHiCord MaxSubmerge Is_Ogee
33.5,31,3,,26,26,,,0.95,0,1,1,,,
  4485.1  4487.5  4493.1  4498.4  4507.9  4510.6  4571.8  4678.2  4776.1  4899.4
  4970.0  4970.0  5030.0  5030.0  5110.7  5163.7  5165.0  5173.4  5177.5  5185.8
  5191.8  5202.1  5208.1  5213.6  5225.3  5232.3
 1360.16 1359.67 1358.80 1358.03 1359.90 1360.73 1344.32 1339.37 1335.54 1334.23
 1335.20 1335.20 1335.20 1335.20 1338.19 1339.46 1339.60 1340.27 1342.31 1345.50
 1346.99 1349.82 1351.89 1353.44 1356.01 1357.63
 1301.00 1301.00 1301.00 1301.00 1301.00 1301.00 1301.00 1301.00 1301.00 1301.00
 1301.00 1333.00 1333.00 1301.00 1301.00 1301.00 1301.00 1301.00 1301.00 1301.00
 1301.00 1301.00 1301.00 1301.00 1301.00 1301.00
  4485.1  4487.5  4493.1  4498.4  4507.9  4510.6  4571.8  4678.2  4776.1  4899.4
  4970.0  4970.0  5030.0  5030.0  5110.7  5163.7  5165.0  5173.4  5177.5  5185.8
  5191.8  5202.1  5208.1  5213.6  5225.3  5232.3
 1360.16 1359.67 1358.80 1358.03 1359.90 1360.73 1344.32 1339.37 1335.54 1334.23
 1335.20 1335.20 1335.20 1335.20 1338.19 1339.46 1339.60 1340.27 1342.31 1345.50
 1346.99 1349.82 1351.89 1353.44 1356.01 1357.63
 1301.00 1301.00 1301.00 1301.00 1301.00 1301.00 1301.00 1301.00 1301.00 1301.00
 1301.00 1333.00 1333.00 1301.00 1301.00 1301.00 1301.00 1301.00 1301.00 1301.00
 1301.00 1301.00 1301.00 1301.00 1301.00 1301.00
Pier Skew, UpSta & Num, DnSta & Num=,5000,2,5000,2,0,0,0,0,0
       1       1
 1320.00 1333.00
       1       1
 1320.00 1333.00
Abutment Skew #Up #Dn=,2,2
  4970.0  4971.0
 1333.00 1330.43
  4970.0  4971.0
 1333.00 1326.22
Abutment Skew #Up #Dn=,2,2
  5029.0  5030.0
 1329.54 1333.00
  5029.0  5030.0
 1329.52 1333.00
BR Coef=1,1,0,1.25,0,,,0.8,0,2,0,
WSPro=,,,, 1 ,,,, 0 ,,,, 0 ,,,,-1 ,-1 ,-1 , 0 , 0 , 0 , 0 , 0
BC Design=,,0,,0,,,,,,

Type RM Length L Ch R = 1,74506,115,115,115
BEGIN DESCRIPTION:
Haystack Rd DS
END DESCRIPTION:
XS GIS Cut Line= 3
      1432080.50       960331.96      1431482.88       960120.48
      1431400.77       960129.12
#Sta/Elev= 30
  4508.8 1360.90  4526.0 1358.38  4570.2 1348.97  4582.1 1343.84  4592.4 1338.15
  4607.7 1336.48  4613.5 1334.88  4682.5 1331.37  4773.6 1329.32  4784.6 1329.86
  4795.3 1329.12  4902.1 1328.06  4953.3 1328.74  4965.0 1326.85  4976.7 1326.03
  4990.0 1325.50  4994.0 1320.80  5006.0 1320.80  5010.0 1322.25  5018.6 1323.97
  5025.3 1329.17  5034.1 1330.00  5069.2 1330.61  5077.0 1332.22  5097.4 1333.41
  5114.2 1338.35  5175.0 1341.95  5185.4 1343.23  5201.7 1350.28  5225.3 1355.42
#Mann=4,-1,0
  4508.8    0.08       0  4976.7    0.08       0  4990.0    0.05       0
  5010.0    0.08       0
#XS Ineff=2,0
    0.00 4947.50 1334.11 5052.50    0.00 1335.82
Permanent Ineff=
       F       F
Bank Sta=4990,5010
XS Rating Curve= 0
Exp/Cntr=0.5,0.3

Type RM Length L Ch R = 1,74391,254,254,254
BEGIN DESCRIPTION:
South Fork 248.0
END DESCRIPTION:
XS GIS Cut Line= 3
      1432157.49       960055.78      1431618.94       960053.25
      1431407.03       960060.82
#Sta/Elev= 30
  4465.2 1361.89  4510.6 1346.52  4554.3 1333.46  4584.1 1329.91  4617.4 1328.51
  4657.3 1328.44  4675.2 1327.31  4692.4 1327.47  4724.4 1326.62  4954.4 1326.18
  4983.9 1326.54  4988.1 1324.66  4995.4 1321.40  4996.9 1318.40  5003.1 1318.40
  5004.6 1320.00  5020.4 1321.48  5031.5 1321.45  5037.4 1325.80  5057.0 1327.16
  5092.2 1327.69  5096.7 1328.89  5103.4 1329.66  5138.1 1340.19  5144.7 1341.06
  5152.3 1342.89  5196.4 1346.41  5202.8 1348.30  5207.3 1348.66  5215.8 1353.27
#Mann=4,-1,0
  4465.2    0.08       0  4988.1    0.08       0  4995.4    0.05       0
  5004.6    0.08       0
#XS Ineff=2,0
    0.00 4900.00 1328.50               0
Permanent Ineff=
       F       F
Bank Sta=4995.4,5004.6
XS Rating Curve= 0
Exp/Cntr=0.3,0.1

Type RM Length L Ch R = 1,74137,267,267,267
BEGIN DESCRIPTION:
South Fork 247.0
END DESCRIPTION:
XS GIS Cut Line= 3
      1432166.69       959875.79      1431522.12       959847.33
      1431421.92       959841.07
#Sta/Elev= 30
  4354.8 1357.12  4381.1 1351.71  4391.9 1350.05  4401.2 1348.11  4457.3 1334.38
  4484.6 1328.80  4500.2 1326.52  4532.1 1324.61  4580.5 1324.79  4617.2 1324.07
  4658.2 1325.00  4697.7 1324.43  4851.7 1323.88  4928.1 1322.49  4962.1 1323.00
  4964.1 1322.66  4989.4 1318.32  4994.0 1317.90  4996.0 1315.76  5004.0 1315.76
  5006.0 1317.90  5009.9 1318.42  5025.5 1322.84  5034.1 1323.52  5039.0 1323.50
  5050.4 1322.54  5061.8 1323.11  5084.5 1334.95  5095.8 1347.11  5100.4 1349.86
#Mann=4,-1,0
  4354.8    0.08       0  4964.1    0.08       0  4994.0    0.05       0
  5006.0    0.08       0
Bank Sta=4994,5006
XS Rating Curve= 0
Exp/Cntr=0.3,0.1

Type RM Length L Ch R = 1,73870,387,387,387
BEGIN DESCRIPTION:
South Fork 246.0
END DESCRIPTION:
XS GIS Cut Line= 5
      1432223.98       959637.94      1432137.17       959610.28
      1432126.49       959609.69      1431623.28       959613.64
      1431463.53       959615.37
#Sta/Elev= 30
  4376.4 1340.80  4384.7 1338.29  4435.9 1325.75  4447.6 1323.92  4457.2 1322.86
  4479.9 1321.26  4535.8 1320.66  4554.1 1320.17  4578.5 1320.22  4615.9 1320.85
  4756.6 1320.22  4828.2 1320.84  4874.0 1320.89  4921.3 1319.84  4971.9 1319.71
  4979.0 1319.64  4989.7 1318.98  4993.6 1315.05  4995.7 1312.05  5004.3 1312.05
  5006.4 1315.05  5015.9 1317.52  5031.0 1319.12  5058.4 1320.27  5064.4 1319.99
  5077.6 1320.36  5115.6 1325.69  5120.7 1329.26  5127.8 1334.94  5141.2 1345.97
#Mann=5,-1,0
  4376.4    0.08       0  4971.9    0.08       0  4993.6    0.05       0
  5006.4    0.08       0  5127.8     0.1       0
#XS Ineff=2,0
    0.00 4874.00 1324.49               0
Permanent Ineff=
       F       F
Bank Sta=4993.6,5006.4
XS Rating Curve= 0
Exp/Cntr=0.3,0.1

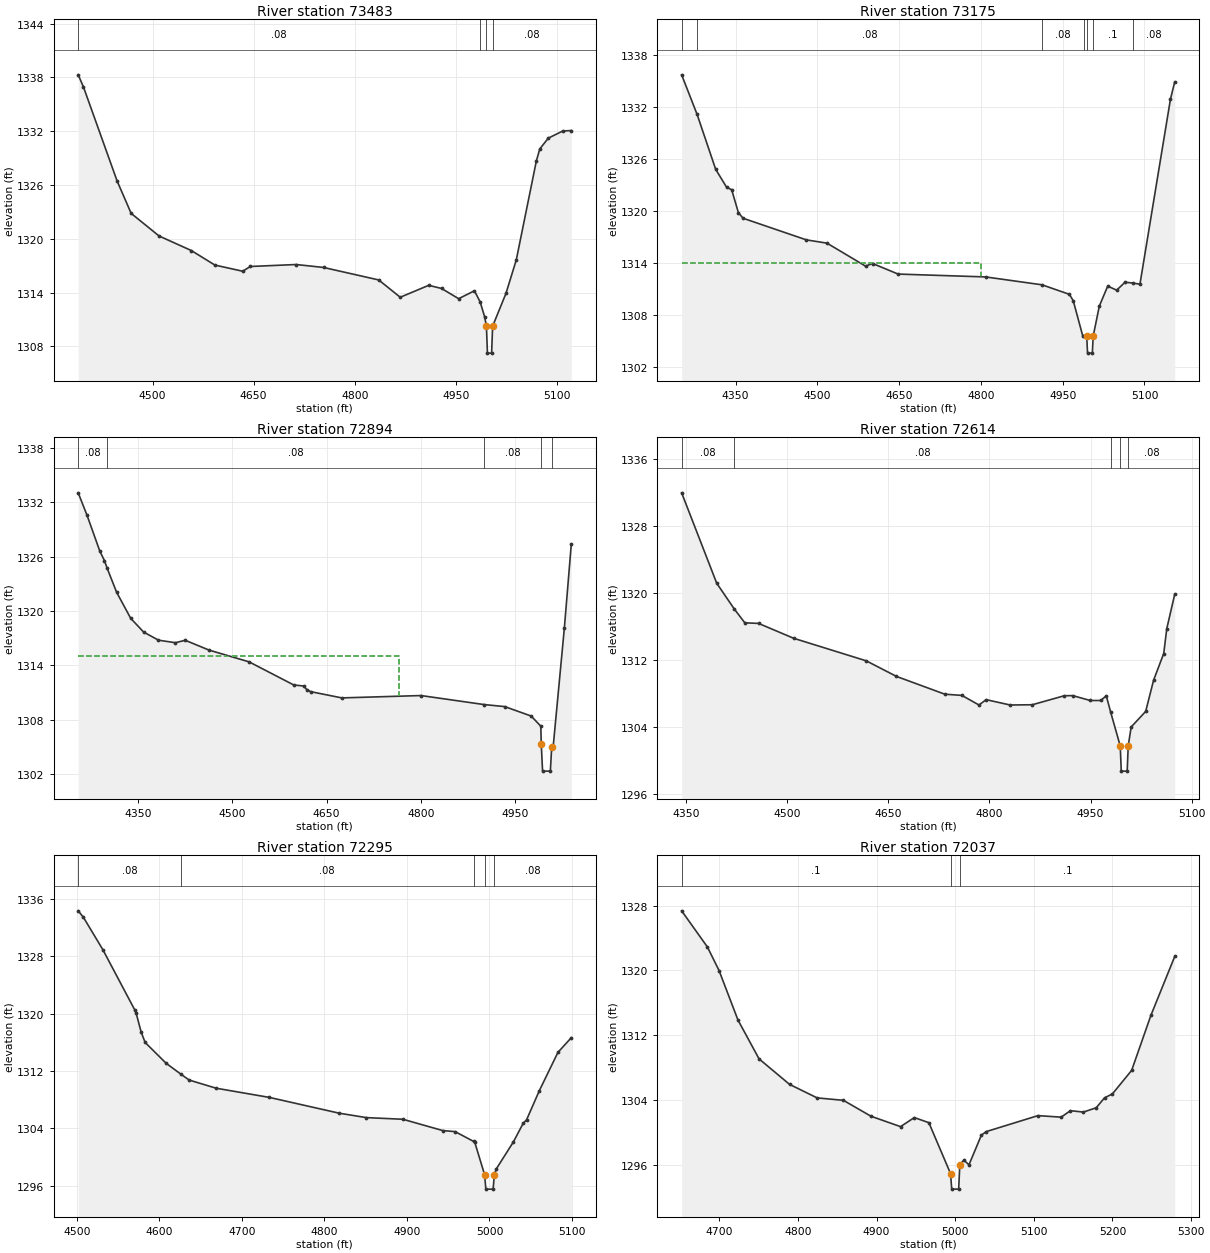
Type RM Length L Ch R = 1,73483,308,308,308
BEGIN DESCRIPTION:
South Fork 245.0
END DESCRIPTION:
XS GIS Cut Line= 4
      1432315.99       959528.57      1431899.32       959299.40
      1431763.91       959288.98      1431644.11       959278.57
#Sta/Elev= 30
  4389.7 1338.28  4397.4 1336.95  4447.4 1326.45  4468.3 1322.83  4509.7 1320.31
  4557.5 1318.69  4592.5 1317.07  4633.8 1316.38  4645.1 1316.91  4713.2 1317.13
  4753.8 1316.80  4835.6 1315.41  4867.5 1313.48  4909.8 1314.81  4928.8 1314.46
  4954.2 1313.32  4977.6 1314.20  4986.1 1312.96  4992.7 1311.31  4995.4 1310.25
  4996.9 1307.25  5003.1 1307.25  5004.6 1310.25  5024.4 1313.91  5039.7 1317.64
  5069.5 1328.68  5074.6 1330.02  5087.2 1331.22  5108.5 1332.01  5121.3 1332.07
#Mann=4,-1,0
  4389.7    0.08       0  4986.1    0.08       0  4995.4    0.05       0
  5004.6    0.08       0
Bank Sta=4995.4,5004.6
XS Rating Curve= 0
Exp/Cntr=0.3,0.1

Type RM Length L Ch R = 1,73175,281,281,281
BEGIN DESCRIPTION:
South Fork 244.0
END DESCRIPTION:
XS GIS Cut Line= 3
      1432451.45       959374.08      1431842.03       959011.21
      1431677.14       958907.06
#Sta/Elev= 30
  4251.2 1335.70  4279.6 1331.12  4313.6 1324.79  4333.9 1322.69  4342.9 1322.44
  4355.2 1319.80  4363.7 1319.14  4479.9 1316.64  4517.8 1316.26  4588.4 1313.61
  4601.4 1313.91  4648.2 1312.69  4808.7 1312.36  4912.1 1311.45  4962.3 1310.35
  4969.4 1309.61  4986.6 1305.59  4990.0 1305.55  4994.1 1305.50  4995.6 1303.56
  5004.4 1303.56  5005.9 1305.50  5017.2 1308.99  5032.6 1311.30  5049.0 1310.83
  5064.4 1311.75  5079.2 1311.65  5091.7 1311.52  5147.7 1332.90  5155.5 1334.89
#Mann=7,-1,0
  4251.2    0.08       0  4279.6    0.08       0  4912.1    0.08       0
  4990.0     0.1       0  4994.1    0.05       0  5005.9     0.1       0
  5079.2    0.08       0
#XS Ineff=2,0
    0.00 4800.00 1314.00               0
Permanent Ineff=
       F       F
Bank Sta=4994.1,5005.9
XS Rating Curve= 0
Exp/Cntr=0.3,0.1

Type RM Length L Ch R = 1,72894,280,280,280
BEGIN DESCRIPTION:
South Fork 243.0
END DESCRIPTION:
XS GIS Cut Line= 4
      1432459.40       959321.96      1432273.75       959223.24
      1431942.91       958839.89      1431906.68       958781.92
#Sta/Elev= 30
  4254.5 1333.03  4268.7 1330.53  4288.9 1326.60  4296.3 1325.55  4300.7 1324.69
  4315.6 1322.07  4338.1 1319.18  4358.6 1317.67  4382.3 1316.77  4409.3 1316.49
  4424.9 1316.76  4463.0 1315.67  4526.5 1314.38  4597.6 1311.83  4613.6 1311.71
  4618.8 1311.28  4625.3 1311.08  4674.2 1310.40  4800.3 1310.66  4900.2 1309.67
  4933.6 1309.44  4975.6 1308.40  4991.0 1307.28  4991.7 1305.32  4993.8 1302.32
  5006.2 1302.32  5008.3 1304.96  5010.6 1304.96  5028.5 1318.12  5039.5 1327.34
#Mann=5,-1,0
  4254.5    0.08       0  4300.7    0.08       0  4900.2    0.08       0
  4991.7    0.05       0  5008.3    0.08       0
#XS Ineff=2,0
    0.00 4766.00 1315.00               0
Permanent Ineff=
       F       F
Bank Sta=4991.7,5008.3
XS Rating Curve= 0
Exp/Cntr=0.3,0.1

Type RM Length L Ch R = 1,72614,319,319,319
BEGIN DESCRIPTION:
South Fork 242.0
END DESCRIPTION:
XS GIS Cut Line= 4
      1432490.22       959291.15      1432368.77       959208.48
      1432198.45       958749.27      1432165.83       958660.47
#Sta/Elev= 30
  4343.6 1331.97  4395.6 1321.16  4421.6 1318.08  4437.3 1316.42  4457.7 1316.35
  4509.8 1314.57  4617.5 1311.87  4662.2 1310.01  4734.0 1307.88  4759.2 1307.74
  4784.6 1306.59  4795.2 1307.23  4830.8 1306.59  4863.6 1306.62  4911.2 1307.70
  4923.8 1307.71  4949.5 1307.13  4965.1 1307.13  4973.4 1307.69  4979.7 1305.79
  4994.1 1301.68  4995.6 1298.68  5004.4 1298.68  5005.9 1301.68  5010.3 1303.96
  5031.8 1305.82  5043.6 1309.57  5058.6 1312.75  5063.1 1315.72  5074.9 1319.84
#Mann=5,-1,0
  4343.6    0.08       0  4421.6    0.08       0  4979.7    0.08       0
  4994.1    0.05       0  5005.9    0.08       0
Bank Sta=4994.1,5005.9
XS Rating Curve= 0
Exp/Cntr=0.3,0.1

Type RM Length L Ch R = 1,72295,258,258,258
BEGIN DESCRIPTION:
South Fork 241.0
END DESCRIPTION:
XS GIS Cut Line= 4
      1432587.22       959233.20      1432532.83       959144.81
      1432476.19       958752.89      1432482.99       958655.50
#Sta/Elev= 30
  4501.7 1334.33  4508.0 1333.43  4531.6 1328.91  4570.3 1320.50  4571.7 1320.15
  4578.0 1317.42  4582.8 1315.98  4608.2 1313.08  4626.2 1311.55  4636.1 1310.74
  4668.8 1309.60  4733.2 1308.32  4818.2 1306.11  4850.9 1305.50  4895.1 1305.27
  4943.5 1303.69  4958.3 1303.55  4980.8 1302.18  4982.2 1302.05  4994.1 1297.53
  4995.6 1295.53  5004.4 1295.53  5005.9 1297.53  5008.2 1298.34  5029.0 1302.12
  5040.8 1304.70  5045.0 1305.21  5060.5 1309.28  5082.9 1314.59  5099.1 1316.64
#Mann=5,-1,0
  4501.7    0.08       0  4626.2    0.08       0  4980.8    0.08       0
  4994.1    0.05       0  5005.9    0.08       0
Bank Sta=4994.1,5005.9
XS Rating Curve= 0
Exp/Cntr=0.3,0.1

Type RM Length L Ch R = 1,72037,292,292,292
BEGIN DESCRIPTION:
South Fork 240.0
END DESCRIPTION:
XS GIS Cut Line= 5
      1432704.10       959151.63      1432664.22       959042.87
      1432719.97       958817.50      1432756.74       958655.46
      1432707.70       958553.50
#Sta/Elev= 30
  4652.0 1327.36  4684.8 1322.89  4699.6 1319.98  4723.7 1313.86  4750.5 1309.07
  4789.3 1305.92  4824.4 1304.25  4857.8 1303.95  4893.0 1301.98  4930.5 1300.70
  4948.0 1301.82  4966.5 1301.19  4994.1 1294.90  4995.6 1292.98  5004.4 1292.98
  5005.9 1295.98  5011.0 1296.57  5017.5 1295.98  5033.4 1299.66  5039.6 1300.09
  5105.3 1302.06  5134.8 1301.87  5146.6 1302.67  5163.1 1302.50  5179.4 1303.03
  5190.0 1304.26  5200.0 1304.74  5224.5 1307.65  5249.0 1314.45  5279.3 1321.72
#Mann=3,-1,0
  4652.0     0.1       0  4994.1    0.05       0  5005.9     0.1       0
Bank Sta=4994.1,5005.9
XS Rating Curve= 0
Exp/Cntr=0.3,0.1

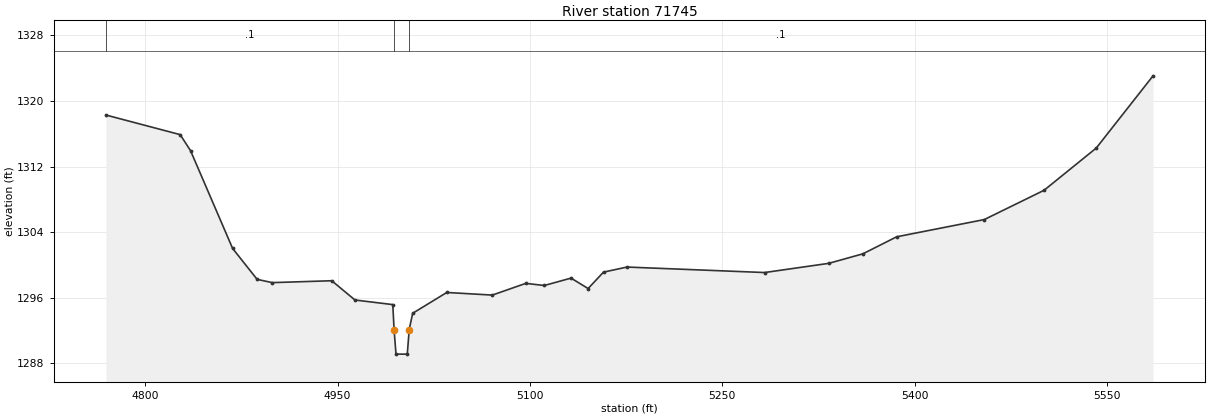
Type RM Length L Ch R = 1,71745,347,347,347
BEGIN DESCRIPTION:
South Fork 239.0
END DESCRIPTION:
XS GIS Cut Line= 3
      1432993.84       959144.23      1432991.01       958920.54
      1432957.03       958328.72
#Sta/Elev= 30
  4769.4 1318.29  4827.3 1315.90  4835.4 1313.94  4868.2 1302.02  4887.3 1298.25
  4899.1 1297.85  4945.5 1298.08  4963.6 1295.73  4993.1 1295.17  4994.1 1292.13
  4995.6 1289.13  5004.4 1289.13  5005.9 1292.13  5008.6 1294.11  5035.2 1296.65
  5070.7 1296.33  5096.8 1297.76  5111.2 1297.50  5132.1 1298.40  5145.4 1297.13
  5157.4 1299.13  5175.7 1299.75  5283.0 1299.08  5333.0 1300.20  5359.6 1301.36
  5386.0 1303.44  5454.3 1305.54  5500.9 1309.11  5541.6 1314.26  5585.9 1323.07
#Mann=3,-1,0
  4769.4     0.1       0  4994.1    0.05       0  5005.9     0.1       0
Bank Sta=4994.1,5005.9
XS Rating Curve= 0
Exp/Cntr=0.3,0.1