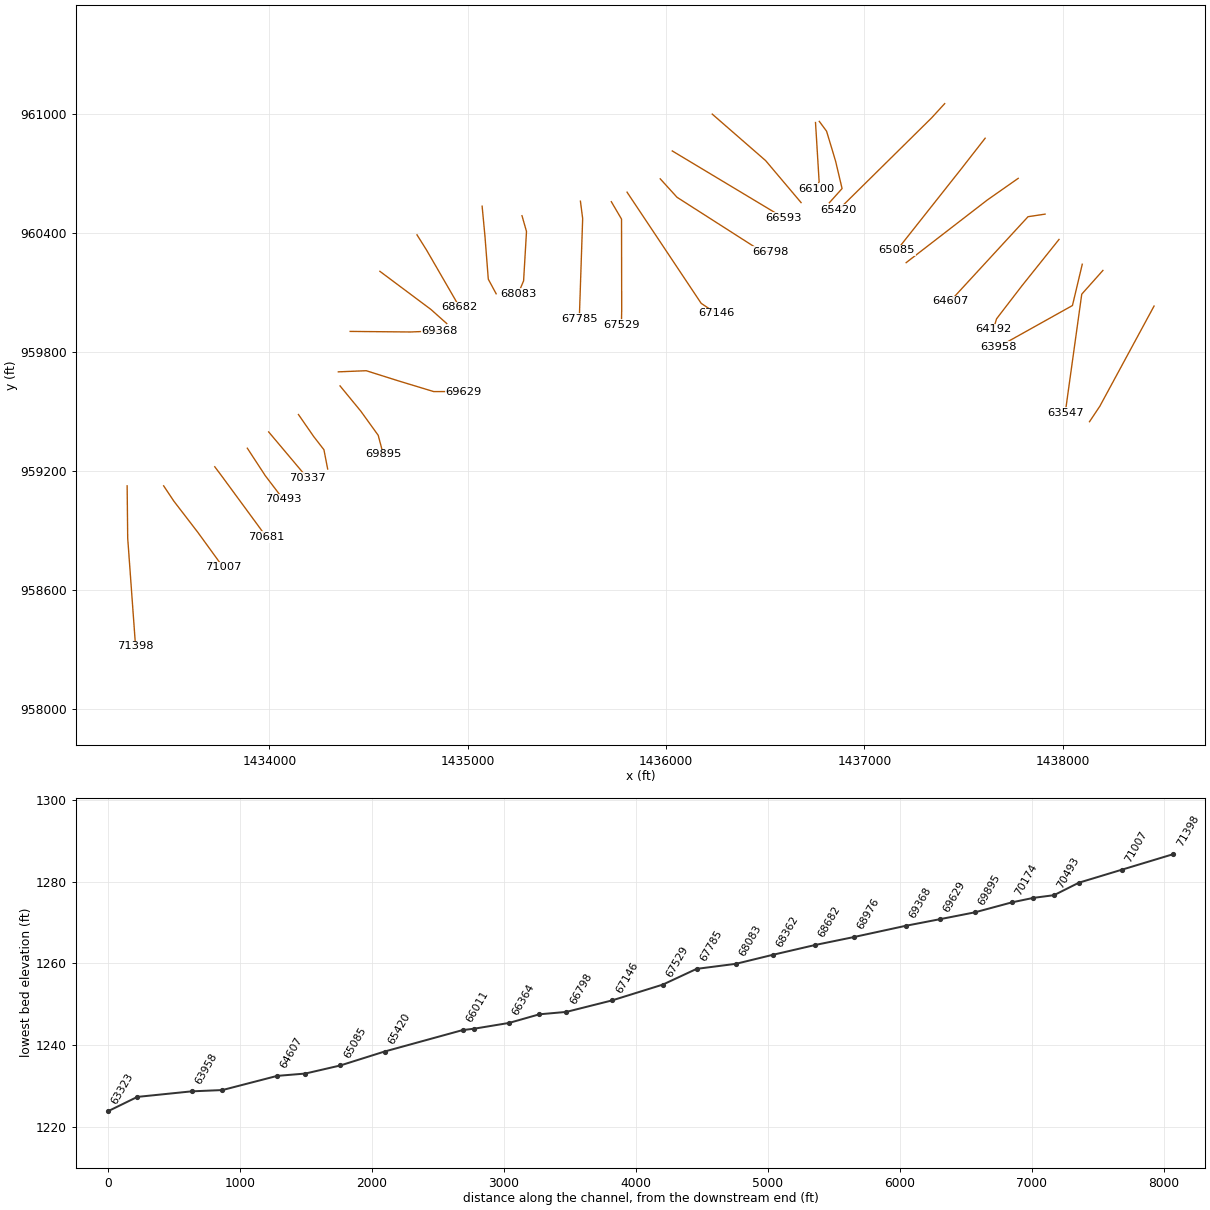
HEC-RAS study South Fork.prj: South Fork Limited Detail Study

--- South Fork.g01 (geometry) --- (continued)

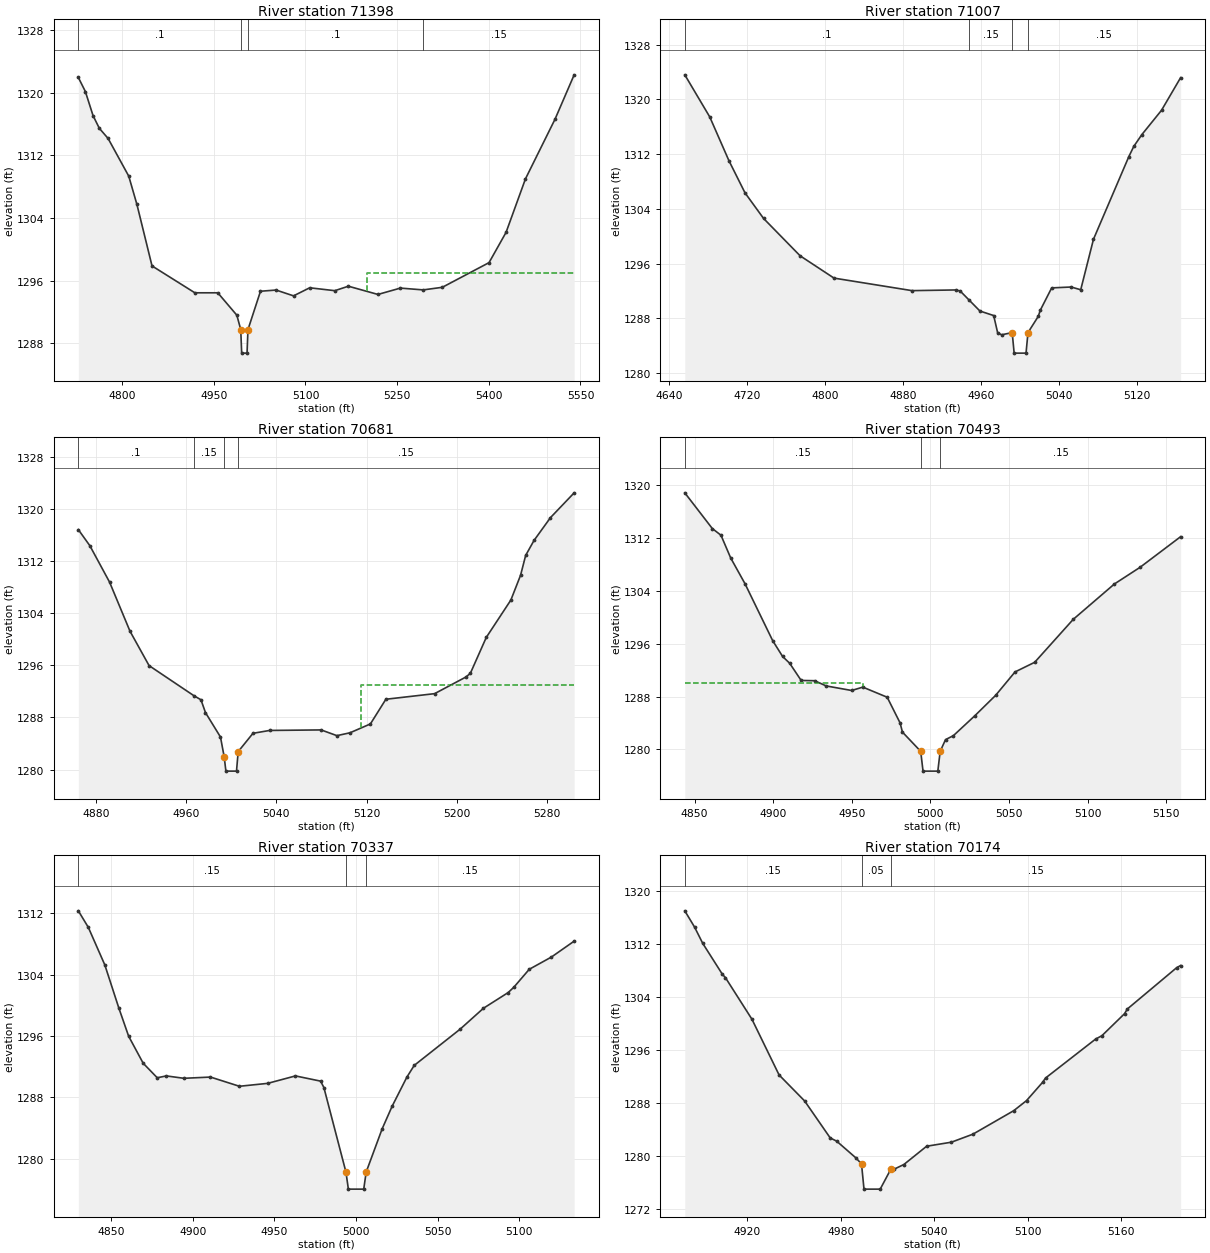
Type RM Length L Ch R = 1,71398,391,391,391
BEGIN DESCRIPTION:
South Fork 238.0
END DESCRIPTION:
XS GIS Cut Line= 3
      1433282.68       959124.43      1433285.52       958861.07
      1433325.16       958314.49
#Sta/Elev= 30
  4728.3 1321.94  4739.8 1320.15  4752.4 1317.07  4762.7 1315.45  4777.0 1314.16
  4810.8 1309.35  4824.2 1305.73  4848.9 1297.89  4919.0 1294.46  4956.5 1294.46
  4987.7 1291.60  4994.1 1289.76  4995.6 1286.76  5004.4 1286.76  5005.9 1289.76
  5026.4 1294.66  5051.9 1294.81  5080.5 1294.07  5106.9 1295.10  5148.0 1294.73
  5170.2 1295.30  5218.6 1294.25  5255.3 1295.06  5292.7 1294.83  5323.9 1295.16
  5400.4 1298.31  5428.3 1302.18  5460.0 1309.00  5508.4 1316.62  5539.7 1322.28
#Mann=4,-1,0
  4728.3     0.1       0  4994.1    0.05       0  5005.9     0.1       0
  5292.7    0.15       0
#XS Ineff=2,0
       0                 5200.00    0.00 1297.00
Permanent Ineff=
       F       F
Bank Sta=4994.1,5005.9
XS Rating Curve= 0
Exp/Cntr=0.3,0.1

Type RM Length L Ch R = 1,71007,326,326,326
BEGIN DESCRIPTION:
South Fork 237.0
END DESCRIPTION:
XS GIS Cut Line= 4
      1433466.76       959124.41      1433517.72       959047.97
      1433639.49       958889.39      1433766.89       958713.86
#Sta/Elev= 30
  4656.0 1323.60  4681.6 1317.45  4701.3 1311.05  4717.8 1306.35  4736.8 1302.62
  4774.3 1297.16  4809.1 1293.90  4889.1 1292.07  4934.0 1292.17  4938.5 1292.02
  4948.0 1290.65  4958.8 1289.09  4972.9 1288.43  4977.0 1285.90  4981.1 1285.62
  4991.9 1285.94  4993.9 1282.94  5006.1 1282.94  5008.1 1285.94  5018.6 1288.30
  5020.8 1289.23  5032.4 1292.47  5052.4 1292.60  5062.2 1292.20  5075.3 1299.58
  5111.6 1311.66  5116.7 1313.16  5125.0 1314.88  5145.1 1318.42  5164.7 1323.19
#Mann=4,-1,0
  4656.0     0.1       0  4948.0    0.15       0  4991.9    0.05       0
  5008.1    0.15       0
Bank Sta=4991.9,5008.1
XS Rating Curve= 0
Exp/Cntr=0.3,0.1

Type RM Length L Ch R = 1,70681,188,188,188
BEGIN DESCRIPTION:
South Fork 236.0
END DESCRIPTION:
XS GIS Cut Line= 3
      1433724.46       959220.69      1433758.42       959175.40
      1433984.97       958866.72
#Sta/Elev= 30
  4864.5 1316.85  4874.7 1314.38  4892.2 1308.78  4910.3 1301.24  4927.2 1295.96
  4967.0 1291.33  4973.2 1290.71  4977.2 1288.74  4990.5 1284.99  4993.8 1281.93
  4995.3 1279.75  5004.7 1279.75  5006.2 1282.75  5019.3 1285.56  5034.1 1286.00
  5079.7 1286.08  5093.7 1285.20  5105.3 1285.64  5123.4 1287.00  5137.1 1290.79
  5180.3 1291.65  5208.1 1294.21  5212.0 1294.78  5226.1 1300.29  5247.9 1306.03
  5256.5 1309.84  5261.0 1312.88  5268.4 1315.18  5283.0 1318.69  5304.0 1322.50
#Mann=4,-1,0
  4864.5     0.1       0  4967.0    0.15       0  4993.8    0.05       0
  5006.2    0.15       0
#XS Ineff=2,0
       0                 5115.00    0.00 1293.00
Permanent Ineff=
       F       F
Bank Sta=4993.8,5006.2
XS Rating Curve= 0
Exp/Cntr=0.3,0.1

Type RM Length L Ch R = 1,70493,156,156,156
BEGIN DESCRIPTION:
South Fork 235.0
END DESCRIPTION:
XS GIS Cut Line= 3
      1433888.67       959314.18      1433979.30       959175.40
      1434069.94       959056.44
#Sta/Elev= 30
  4843.8 1318.84  4861.3 1313.43  4866.8 1312.42  4873.0 1308.97  4882.1 1305.07
  4899.7 1296.45  4906.0 1294.06  4910.5 1293.03  4917.8 1290.43  4926.4 1290.39
  4933.7 1289.60  4949.9 1288.91  4957.0 1289.42  4972.5 1287.89  4980.7 1284.00
  4982.2 1282.61  4993.8 1279.70  4995.3 1276.70  5004.7 1276.70  5006.2 1279.70
  5009.6 1281.47  5014.6 1282.07  5028.3 1285.10  5041.4 1288.16  5053.8 1291.72
  5066.3 1293.18  5090.8 1299.68  5117.0 1305.04  5133.3 1307.56  5159.1 1312.20
#Mann=3,-1,0
  4843.8    0.15       0  4993.8    0.05       0  5006.2    0.15       0
#XS Ineff=2,0
    0.00 4957.00 1290.00               0
Permanent Ineff=
       F       F
Bank Sta=4993.8,5006.2
XS Rating Curve= 0
Exp/Cntr=0.3,0.1

Type RM Length L Ch R = 1,70337,163,163,163
BEGIN DESCRIPTION:
South Fork 234.5
END DESCRIPTION:
XS GIS Cut Line= 2
      1433996.27       959396.31      1434191.67       959164.08
#Sta/Elev= 30
  4830.0 1312.30  4836.1 1310.15  4846.2 1305.26  4854.8 1299.63  4860.8 1295.96
  4869.7 1292.44  4878.3 1290.55  4883.9 1290.79  4894.6 1290.48  4910.9 1290.64
  4928.6 1289.44  4945.9 1289.82  4962.9 1290.79  4978.3 1290.11  4980.3 1289.28
  4993.8 1278.27  4995.3 1276.04  5004.7 1276.04  5006.2 1278.27  5016.0 1283.91
  5022.1 1286.85  5031.1 1290.63  5035.6 1292.16  5063.7 1296.88  5078.0 1299.61
  5093.1 1301.65  5096.6 1302.35  5106.0 1304.68  5119.6 1306.28  5133.5 1308.35
#Mann=3,-1,0
  4830.0    0.15       0  4993.8    0.05       0  5006.2    0.15       0
Bank Sta=4993.8,5006.2
XS Rating Curve= 0
Exp/Cntr=0.3,0.1

Type RM Length L Ch R = 1,70174,279,279,279
BEGIN DESCRIPTION:
South Fork 234.0
END DESCRIPTION:
XS GIS Cut Line= 4
      1434146.37       959484.07      1434222.84       959373.62
      1434274.87       959306.48      1434293.64       959209.35
#Sta/Elev= 30
  4879.8 1316.98  4886.1 1314.51  4891.3 1312.07  4903.9 1307.40  4905.9 1306.88
  4922.9 1300.60  4940.3 1292.19  4956.7 1288.26  4973.1 1282.68  4977.3 1282.18
  4989.4 1279.70  4993.2 1278.76  4994.8 1274.94  5005.2 1274.94  5012.0 1277.94
  5014.1 1277.95  5020.4 1278.66  5035.0 1281.42  5050.9 1282.03  5064.7 1283.24
  5090.9 1286.79  5099.1 1288.31  5109.4 1291.07  5111.3 1291.72  5143.4 1297.60
  5147.5 1298.12  5162.0 1301.44  5163.8 1302.15  5195.5 1308.40  5198.0 1308.72
#Mann=3,-1,0
  4879.8    0.15       0  4993.2    0.05       0  5012.0    0.15       0
Bank Sta=4993.2,5012
XS Rating Curve= 0
Exp/Cntr=0.3,0.1

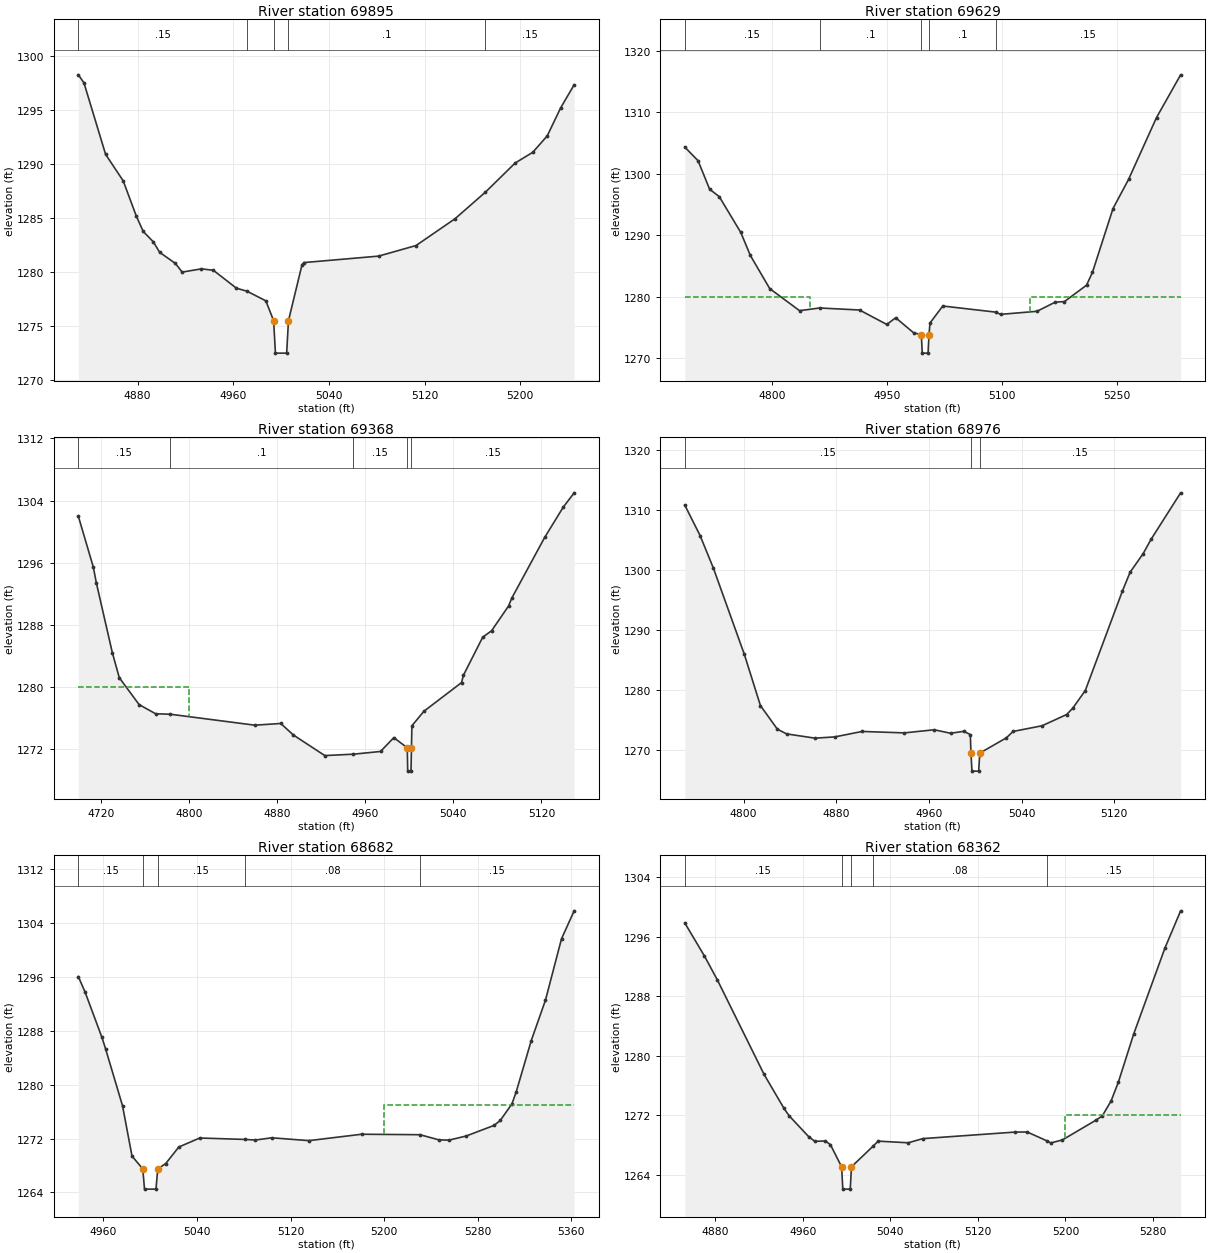
Type RM Length L Ch R = 1,69895,266,266,266
BEGIN DESCRIPTION:
South Fork 233.0
END DESCRIPTION:
XS GIS Cut Line= 4
      1434355.95       959628.45      1434460.71       959501.05
      1434548.49       959379.29      1434573.97       959283.05
#Sta/Elev= 30
  4830.5 1298.27  4835.2 1297.53  4853.3 1290.91  4868.0 1288.46  4879.1 1285.16
  4884.8 1283.77  4893.3 1282.80  4898.5 1281.84  4911.7 1280.81  4917.3 1280.01
  4933.4 1280.31  4943.4 1280.18  4962.7 1278.52  4971.6 1278.24  4987.3 1277.35
  4993.8 1275.51  4995.3 1272.51  5004.7 1272.51  5006.2 1275.51  5017.5 1280.67
  5019.0 1280.89  5081.6 1281.49  5112.9 1282.47  5145.5 1284.95  5170.9 1287.41
  5195.8 1290.11  5210.5 1291.10  5222.6 1292.62  5233.8 1295.21  5245.1 1297.35
#Mann=5,-1,0
  4830.5    0.15       0  4971.6     0.1       0  4993.8    0.05       0
  5006.2     0.1       0  5170.9    0.15       0
Bank Sta=4993.8,5006.2
XS Rating Curve= 0
Exp/Cntr=0.3,0.1

Type RM Length L Ch R = 1,69629,261,261,261
BEGIN DESCRIPTION:
South Fork 232.0
END DESCRIPTION:
XS GIS Cut Line= 5
      1434347.41       959699.28      1434488.14       959704.97
      1434653.18       959652.90      1434828.69       959599.68
      1434978.89       959600.16
#Sta/Elev= 30
  4686.1 1304.31  4703.4 1302.10  4718.5 1297.47  4731.1 1296.26  4759.2 1290.44
  4771.7 1286.70  4797.0 1281.31  4836.0 1277.72  4862.2 1278.16  4914.3 1277.83
  4949.9 1275.48  4961.5 1276.57  4984.9 1274.13  4995.0 1273.82  4996.2 1270.82
  5003.8 1270.82  5005.0 1273.82  5006.3 1275.72  5023.0 1278.48  5092.5 1277.48
  5098.4 1277.12  5146.0 1277.62  5169.9 1279.11  5181.9 1279.20  5210.7 1281.86
  5218.4 1283.93  5245.3 1294.32  5265.6 1299.06  5302.1 1309.11  5333.6 1316.06
#Mann=5,-1,0
  4686.1    0.15       0  4862.2     0.1       0  4995.0    0.05       0
  5005.0     0.1       0  5092.5    0.15       0
#XS Ineff=2,0
    0.00 4850.00 1280.00 5137.00    0.00 1280.00
Permanent Ineff=
       F       F
Bank Sta=4995,5005
XS Rating Curve= 0
Exp/Cntr=0.3,0.1

Type RM Length L Ch R = 1,69368,392,392,392
BEGIN DESCRIPTION:
South Fork 231.0
END DESCRIPTION:
XS GIS Cut Line= 3
      1434406.92       959903.17      1434709.90       959900.33
      1434857.20       959906.00
#Sta/Elev= 30
  4699.3 1301.98  4712.9 1295.44  4715.7 1293.38  4730.2 1284.42  4736.5 1281.21
  4754.5 1277.75  4769.5 1276.57  4782.8 1276.51  4859.6 1275.10  4883.2 1275.32
  4894.6 1273.84  4923.2 1271.19  4949.2 1271.37  4973.8 1271.72  4985.9 1273.50
  4998.1 1272.19  4998.5 1269.19  5001.5 1269.19  5001.9 1272.19  5002.3 1275.02
  5013.2 1276.89  5047.4 1280.58  5049.1 1281.52  5066.6 1286.41  5074.7 1287.25
  5090.1 1290.43  5093.1 1291.46  5122.9 1299.25  5139.8 1303.15  5149.7 1304.99
#Mann=5,-1,0
  4699.3    0.15       0  4782.8     0.1       0  4949.2    0.15       0
  4998.1    0.05       0  5001.9    0.15       0
#XS Ineff=2,0
    0.00 4800.00 1280.00               0
Permanent Ineff=
       F       F
Bank Sta=4998.1,5001.9
XS Rating Curve= 0
Exp/Cntr=0.3,0.1

Type RM Length L Ch R = 1,68976,294,294,294
BEGIN DESCRIPTION:
South Fork 230.0
END DESCRIPTION:
XS GIS Cut Line= 3
      1434556.97       960206.18      1434814.68       960013.61
      1434893.96       959942.82
#Sta/Elev= 30
  4749.2 1310.82  4762.4 1305.74  4773.9 1300.30  4800.6 1285.92  4814.5 1277.37
  4829.1 1273.44  4837.1 1272.65  4861.6 1271.94  4878.7 1272.15  4902.3 1273.06
  4938.7 1272.82  4964.5 1273.34  4978.6 1272.76  4990.0 1273.08  4995.7 1272.54
  4996.2 1269.44  4997.1 1266.44  5002.9 1266.44  5003.8 1269.44  5026.8 1272.00
  5032.6 1273.06  5057.6 1274.01  5078.8 1275.88  5084.0 1276.92  5094.9 1279.88
  5126.9 1296.46  5133.6 1299.63  5144.8 1302.71  5151.6 1305.09  5177.2 1312.87
#Mann=3,-1,0
  4749.2    0.15       0  4996.2    0.05       0  5003.8    0.15       0
Bank Sta=4996.2,5003.8
XS Rating Curve= 0
Exp/Cntr=0.3,0.1

Type RM Length L Ch R = 1,68682,320,320,320
BEGIN DESCRIPTION:
South Fork 229.0
END DESCRIPTION:
XS GIS Cut Line= 3
      1434743.90       960390.21      1434792.03       960313.77
      1434959.10       960024.94
#Sta/Elev= 30
  4938.5 1296.04  4944.2 1293.78  4958.7 1287.01  4961.9 1285.26  4976.3 1276.86
  4984.4 1269.40  4993.6 1267.49  4995.1 1264.49  5004.9 1264.49  5006.4 1267.49
  5013.2 1268.28  5024.4 1270.74  5042.3 1272.08  5080.7 1271.87  5089.9 1271.78
  5104.0 1272.11  5135.7 1271.69  5180.8 1272.64  5230.7 1272.57  5246.7 1271.81
  5255.4 1271.76  5270.2 1272.38  5294.0 1273.95  5299.3 1274.68  5309.3 1277.15
  5313.0 1278.96  5325.8 1286.54  5337.9 1292.51  5351.7 1301.67  5362.5 1305.81
#Mann=5,-1,0
  4938.5    0.15       0  4993.6    0.05       0  5006.4    0.15       0
  5080.7    0.08       0  5230.7    0.15       0
#XS Ineff=2,0
       0                 5200.00    0.00 1277.00
Permanent Ineff=
       F       F
Bank Sta=4993.6,5006.4
XS Rating Curve= 0
Exp/Cntr=0.3,0.1

Type RM Length L Ch R = 1,68362,279,279,279
BEGIN DESCRIPTION:
South Fork 228.0
END DESCRIPTION:
XS GIS Cut Line= 4
      1435072.37       960534.66      1435086.53       960384.57
      1435103.52       960166.52      1435143.17       960092.88
#Sta/Elev= 30
  4852.2 1297.87  4870.1 1293.44  4881.9 1290.23  4924.7 1277.50  4942.9 1272.93
  4947.6 1271.94  4965.5 1269.13  4971.0 1268.52  4980.7 1268.56  4985.3 1268.06
  4995.5 1265.09  4996.6 1262.09  5003.4 1262.09  5004.5 1265.09  5024.3 1267.87
  5028.9 1268.54  5056.4 1268.32  5069.7 1268.88  5154.0 1269.76  5165.1 1269.77
  5183.1 1268.58  5186.6 1268.30  5197.2 1268.70  5227.7 1271.34  5233.7 1271.93
  5241.8 1273.96  5248.4 1276.47  5262.5 1282.98  5291.0 1294.51  5305.3 1299.50
#Mann=5,-1,0
  4852.2    0.15       0  4995.5    0.05       0  5004.5    0.15       0
  5024.3    0.08       0  5183.1    0.15       0
#XS Ineff=2,0
       0                 5200.00    0.00 1272.00
Permanent Ineff=
       F       F
Bank Sta=4995.5,5004.5
XS Rating Curve= 0
Exp/Cntr=0.3,0.1

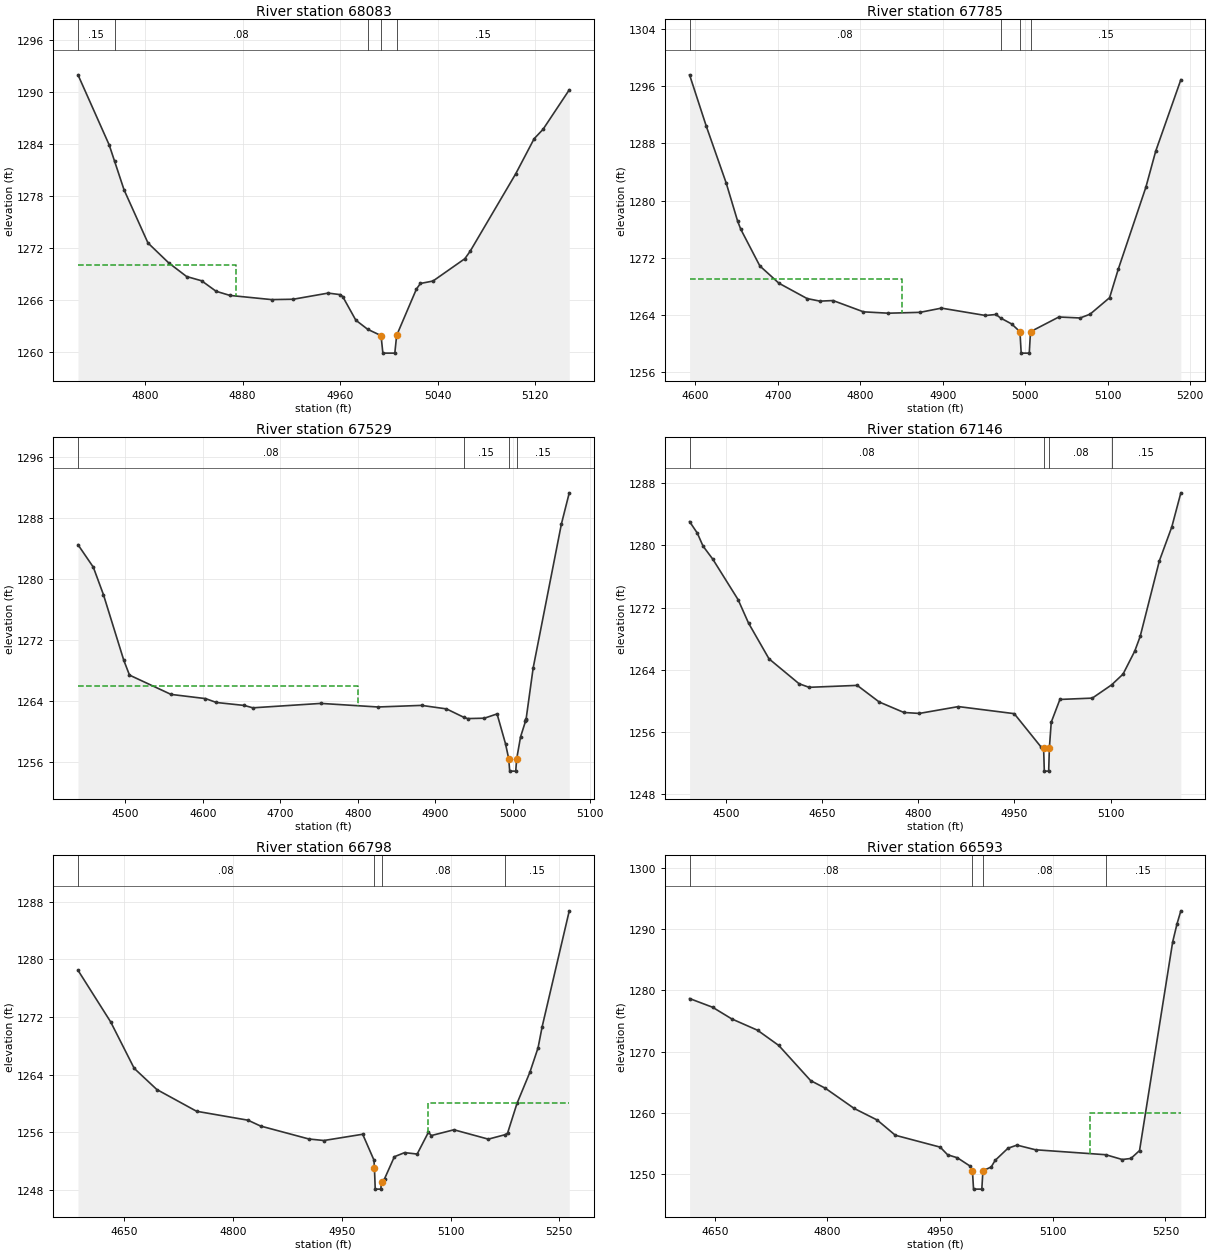
Type RM Length L Ch R = 1,68083,298,298,298
BEGIN DESCRIPTION:
South Fork 227.0
END DESCRIPTION:
XS GIS Cut Line= 4
      1435273.42       960486.55      1435296.08       960407.22
      1435281.42       960157.93      1435253.59       960092.86
#Sta/Elev= 30
  4745.0 1291.97  4770.6 1283.89  4775.1 1281.98  4782.8 1278.71  4802.4 1272.59
  4819.3 1270.31  4834.1 1268.72  4846.4 1268.23  4858.3 1267.02  4869.7 1266.54
  4903.8 1266.06  4921.5 1266.10  4950.2 1266.81  4960.3 1266.63  4962.2 1266.40
  4972.9 1263.69  4982.6 1262.64  4993.6 1261.91  4995.1 1259.89  5004.9 1259.89
  5006.4 1261.93  5022.6 1267.27  5025.9 1267.92  5036.2 1268.20  5062.3 1270.77
  5066.6 1271.61  5104.1 1280.57  5119.2 1284.61  5126.5 1285.69  5148.0 1290.24
#Mann=5,-1,0
  4745.0    0.15       0  4775.1    0.08       0  4982.6    0.15       0
  4993.6    0.05       0  5006.4    0.15       0
#XS Ineff=2,0
    0.00 4875.00 1270.00               0
Permanent Ineff=
       F       F
Bank Sta=4993.6,5006.4
XS Rating Curve= 0
Exp/Cntr=0.3,0.1

Type RM Length L Ch R = 1,67785,256,256,256
BEGIN DESCRIPTION:
South Fork 226.0
END DESCRIPTION:
XS GIS Cut Line= 3
      1435567.93       960560.16      1435579.26       960472.35
      1435562.27       959965.47
#Sta/Elev= 30
  4593.0 1297.61  4613.3 1290.41  4637.4 1282.47  4651.3 1277.12  4655.1 1275.99
  4678.2 1270.86  4701.3 1268.44  4735.5 1266.29  4751.0 1265.93  4767.0 1266.01
  4803.9 1264.43  4834.1 1264.24  4872.5 1264.36  4898.4 1264.95  4951.8 1263.92
  4964.5 1264.06  4970.1 1263.57  4983.6 1262.73  4993.6 1261.65  4995.1 1258.65
  5004.9 1258.65  5006.4 1261.65  5040.8 1263.71  5066.5 1263.57  5078.6 1264.10
  5102.3 1266.41  5112.7 1270.36  5146.3 1281.88  5158.2 1286.92  5188.7 1296.93
#Mann=4,-1,0
  4593.0    0.08       0  4970.1    0.15       0  4993.6    0.05       0
  5006.4    0.15       0
#XS Ineff=2,0
    0.00 4850.00 1269.00               0
Permanent Ineff=
       F       F
Bank Sta=4993.6,5006.4
XS Rating Curve= 0
Exp/Cntr=0.3,0.1

Type RM Length L Ch R = 1,67529,383,383,383
BEGIN DESCRIPTION:
South Fork 225.0
END DESCRIPTION:
XS GIS Cut Line= 4
      1435723.67       960557.33      1435775.19       960469.53
      1435776.03       960010.13      1435774.65       959937.14
#Sta/Elev= 30
  4438.8 1284.49  4458.6 1281.54  4471.7 1277.93  4498.0 1269.31  4505.3 1267.39
  4558.9 1264.86  4603.4 1264.31  4617.5 1263.80  4653.6 1263.41  4664.5 1263.10
  4752.4 1263.68  4826.1 1263.21  4882.3 1263.42  4914.5 1262.96  4936.8 1261.86
  4941.8 1261.69  4963.4 1261.74  4979.8 1262.30  4990.7 1258.39  4994.9 1256.40
  4996.1 1254.80  5003.9 1254.80  5005.1 1256.40  5010.1 1259.28  5016.4 1261.31
  5016.6 1261.59  5017.2 1261.56  5026.4 1268.33  5062.9 1287.23  5073.0 1291.29
#Mann=4,-1,0
  4438.8    0.08       0  4936.8    0.15       0  4994.9    0.05       0
  5005.1    0.15       0
#XS Ineff=2,0
    0.00 4800.00 1266.00               0
Permanent Ineff=
       F       F
Bank Sta=4994.9,5005.1
XS Rating Curve= 0
Exp/Cntr=0.3,0.1

Type RM Length L Ch R = 1,67146,348,348,348
BEGIN DESCRIPTION:
South Fork 224.0
END DESCRIPTION:
XS GIS Cut Line= 3
      1435802.99       960605.42      1436176.77       960044.75
      1436253.20       959993.80
#Sta/Elev= 30
  4443.7 1283.07  4455.8 1281.58  4464.7 1279.91  4479.9 1278.23  4519.4 1273.01
  4535.6 1270.00  4567.5 1265.40  4614.4 1262.19  4630.0 1261.73  4705.0 1261.98
  4739.3 1259.84  4777.8 1258.49  4801.8 1258.37  4862.7 1259.25  4949.7 1258.34
  4991.0 1254.10  4995.5 1253.94  4996.6 1250.94  5003.4 1250.94  5004.5 1253.94
  5007.4 1257.24  5020.9 1260.17  5071.4 1260.34  5101.4 1262.04  5119.3 1263.43
  5137.6 1266.40  5146.0 1268.28  5175.9 1278.01  5195.3 1282.38  5209.4 1286.77
#Mann=4,-1,0
  4443.7    0.08       0  4995.5    0.05       0  5004.5    0.08       0
  5101.4    0.15       0
Bank Sta=4995.5,5004.5
XS Rating Curve= 0
Exp/Cntr=0.3,0.1

Type RM Length L Ch R = 1,66798,205,205,205
BEGIN DESCRIPTION:
South Fork 223.0
END DESCRIPTION:
XS GIS Cut Line= 4
      1435970.32       960672.65      1436055.11       960579.44
      1436473.79       960311.54      1436527.59       960304.60
#Sta/Elev= 30
  4586.4 1278.50  4631.5 1271.32  4663.9 1264.88  4695.1 1261.94  4749.9 1258.92
  4820.8 1257.68  4838.1 1256.87  4904.8 1255.07  4925.4 1254.86  4978.9 1255.73
  4994.4 1252.15  4995.1 1251.11  4996.2 1248.11  5003.9 1248.11  5004.9 1249.11
  5009.1 1249.56  5022.6 1252.61  5036.7 1253.18  5054.0 1252.98  5069.5 1256.00
  5073.6 1255.55  5104.7 1256.35  5152.1 1255.05  5174.9 1255.66  5178.6 1255.87
  5191.6 1260.00  5209.5 1264.36  5220.7 1267.74  5226.3 1270.65  5263.7 1286.75
#Mann=4,-1,0
  4586.4    0.08       0  4995.1    0.05       0  5004.9    0.08       0
  5174.9    0.15       0
#XS Ineff=2,0
       0                 5069.00    0.00 1260.00
Permanent Ineff=
       F       F
Bank Sta=4995.1,5004.9
XS Rating Curve= 0
Exp/Cntr=0.3,0.1

Type RM Length L Ch R = 1,66593,229,229,229
BEGIN DESCRIPTION:
South Fork 222.0
END DESCRIPTION:
XS GIS Cut Line= 2
      1436031.08       960813.28      1436591.82       960476.49
#Sta/Elev= 30
  4616.4 1278.66  4647.0 1277.24  4672.6 1275.33  4706.9 1273.48  4735.2 1270.99
  4777.6 1265.25  4797.2 1264.00  4835.6 1260.70  4866.2 1258.81  4890.4 1256.32
  4950.1 1254.38  4960.0 1253.13  4973.0 1252.64  4989.2 1251.34  4993.0 1250.52
  4994.5 1247.52  5005.5 1247.52  5007.0 1250.52  5018.0 1251.14  5023.2 1252.21
  5040.3 1254.20  5052.3 1254.71  5077.0 1253.95  5170.6 1253.14  5192.4 1252.36
  5204.0 1252.53  5215.5 1253.82  5259.6 1287.90  5265.4 1290.86  5270.5 1292.99
#Mann=4,-1,0
  4616.4    0.08       0  4993.0    0.05       0  5007.0    0.08       0
  5170.6    0.15       0
#XS Ineff=2,0
       0                 5150.00    0.00 1260.00
Permanent Ineff=
       F       F
Bank Sta=4993,5007
XS Rating Curve= 0
Exp/Cntr=0.3,0.1

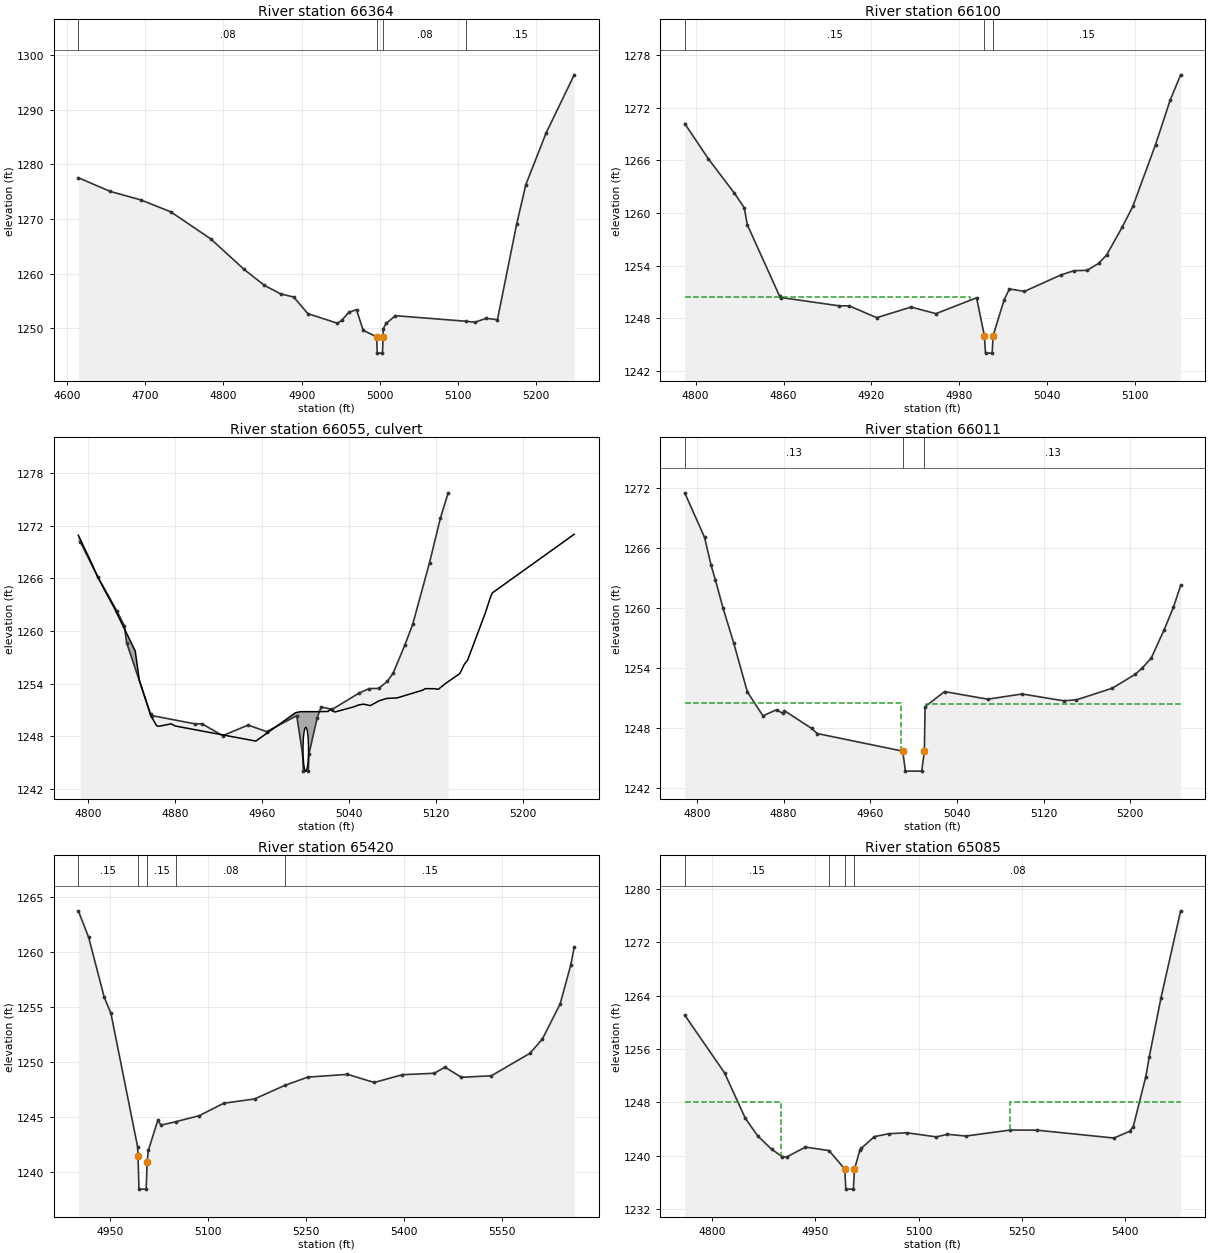
Type RM Length L Ch R = 1,66364,264,264,264
BEGIN DESCRIPTION:
South Fork 221.0
END DESCRIPTION:
XS GIS Cut Line= 3
      1436232.47       960999.05      1436501.57       960764.67
      1436680.42       960552.83
#Sta/Elev= 30
  4614.4 1277.55  4655.3 1275.04  4694.2 1273.49  4732.5 1271.31  4783.5 1266.37
  4826.5 1260.74  4852.3 1257.83  4873.1 1256.27  4889.8 1255.69  4907.9 1252.64
  4945.7 1250.89  4951.2 1251.41  4960.2 1252.89  4970.1 1253.38  4978.6 1249.59
  4995.8 1248.41  4996.7 1245.41  5003.3 1245.41  5004.2 1248.41  5004.3 1249.85
  5007.8 1250.85  5019.9 1252.27  5109.5 1251.26  5121.6 1251.07  5136.0 1251.79
  5150.3 1251.53  5175.0 1269.12  5186.6 1276.28  5212.4 1285.70  5248.5 1296.41
#Mann=4,-1,0
  4614.4    0.08       0  4995.8    0.05       0  5004.2    0.08       0
  5109.5    0.15       0
#XS Ineff=2,0
       0                 5200.00    0.00 1260.00
Permanent Ineff=
       F       F
Bank Sta=4995.8,5004.2
XS Rating Curve= 0
Exp/Cntr=0.5,0.3

Type RM Length L Ch R = 1,66100,89,89,89
BEGIN DESCRIPTION:
Private Culvert US
END DESCRIPTION:
XS GIS Cut Line= 3
      1436753.18       960956.62      1436771.43       960658.76
      1436757.33       960621.45
#Sta/Elev= 30
  4792.6 1270.21  4808.8 1266.17  4826.5 1262.26  4833.2 1260.60  4835.3 1258.66
  4857.4 1250.47  4858.3 1250.35  4898.0 1249.40  4904.7 1249.40  4923.6 1248.05
  4947.0 1249.26  4964.0 1248.51  4991.7 1250.32  4997.0 1246.00  4997.8 1244.00
  5002.3 1244.00  5003.0 1246.00  5010.5 1250.09  5014.1 1251.33  5024.3 1251.05
  5049.1 1252.92  5058.3 1253.42  5067.0 1253.45  5074.9 1254.24  5080.4 1255.21
  5091.0 1258.37  5098.3 1260.76  5113.8 1267.82  5123.7 1272.86  5130.9 1275.78
#Mann=3,-1,0
  4792.6    0.15       0  4997.0   0.055       0  5003.0    0.15       0
#XS Ineff=2,0
    0.00 4987.50 1250.37 5012.50    0.00 1250.42
Permanent Ineff=
       F       F
Bank Sta=4997,5003
XS Rating Curve= 0
Exp/Cntr=0.5,0.3

Type RM Length L Ch R =2,66055,,,
BEGIN DESCRIPTION:
Private Culvert TOR
Structure ID: LDS_SF_D
Approximate Survey Structure
END DESCRIPTION:
Bridge Culvert--1,0,-1,-1,0
Deck Dist Width WeirC Skew NumUp NumDn MinLoCord MaxHiCord MaxSubmerge Is_Ogee
10,70,3,,39,39,,,0.95,0,1,1,,,
  4790.9  4802.1  4808.3  4814.9  4823.4  4843.2  4846.9  4857.5  4862.9  4864.9
  4876.2  4880.1  4954.1  4990.6  4995.1  5007.4  5007.9  5020.5  5022.2  5026.7
  5043.8  5048.8  5053.3  5059.2  5067.7  5074.4  5084.0  5107.3  5110.0  5118.7
  5121.8  5128.4  5141.7  5145.8  5148.7  5165.0  5169.8  5171.6  5246.8
 1270.93 1268.01 1266.30 1264.70 1262.76 1257.72 1254.43 1250.33 1249.18 1249.12
 1249.40 1249.15 1247.43 1250.67 1250.79 1250.79 1250.79 1250.81 1251.02 1250.75
 1251.33 1251.56 1251.65 1251.48 1252.04 1252.30 1252.36 1253.24 1253.42 1253.41
 1253.34 1254.00 1255.15 1256.21 1256.65 1262.04 1263.86 1264.36 1271.05
 1224.00 1224.00 1224.00 1224.00 1224.00 1224.00 1224.00 1224.00 1224.00 1224.00
 1224.00 1224.00 1224.00 1224.00 1224.00 1224.00 1224.00 1224.00 1224.00 1224.00
 1224.00 1224.00 1224.00 1224.00 1224.00 1224.00 1224.00 1224.00 1224.00 1224.00
 1224.00 1224.00 1224.00 1224.00 1224.00 1224.00 1224.00 1224.00 1224.00
  4790.9  4802.1  4808.3  4814.9  4823.4  4843.2  4846.9  4857.5  4862.9  4864.9
  4876.2  4880.1  4954.1  4990.6  4995.1  5007.4  5007.9  5020.5  5022.2  5026.7
  5043.8  5048.8  5053.3  5059.2  5067.7  5074.4  5084.0  5107.3  5110.0  5118.7
  5121.8  5128.4  5141.7  5145.8  5148.7  5165.0  5169.8  5171.6  5246.8
 1270.93 1268.01 1266.30 1264.70 1262.76 1257.72 1254.43 1250.33 1249.18 1249.12
 1249.40 1249.15 1247.43 1250.67 1250.79 1250.79 1250.79 1250.81 1251.02 1250.75
 1251.33 1251.56 1251.65 1251.48 1252.04 1252.30 1252.36 1253.24 1253.42 1253.41
 1253.34 1254.00 1255.15 1256.21 1256.65 1262.04 1263.86 1264.36 1271.05
 1223.65 1223.65 1223.65 1223.65 1223.65 1223.65 1223.65 1223.65 1223.65 1223.65
 1223.65 1223.65 1223.65 1223.65 1223.65 1223.65 1223.65 1223.65 1223.65 1223.65
 1223.65 1223.65 1223.65 1223.65 1223.65 1223.65 1223.65 1223.65 1223.65 1223.65
 1223.65 1223.65 1223.65 1223.65 1223.65 1223.65 1223.65 1223.65 1223.65
Culvert=1,5,,70,0.024,0.9,1,2,3,1244,5000,1243.65,5000,Culvert #1,0,10
Culvert Bottom n=0.024
Culvert Bottom Depth=0
Culvert Depth Blocked=0
BC Design=,,0,,0,,,,,,

Type RM Length L Ch R = 1,66011,591,591,591
BEGIN DESCRIPTION:
Private Culvert DS
END DESCRIPTION:
XS GIS Cut Line= 6
      1436772.24       960962.47      1436809.00       960912.62
      1436843.98       960796.84      1436854.99       960759.49
      1436887.12       960623.56      1436822.89       960551.95
#Sta/Elev= 30
  4788.8 1271.50  4807.1 1267.04  4813.1 1264.26  4817.0 1262.82  4824.1 1259.99
  4833.9 1256.51  4846.6 1251.58  4861.0 1249.18  4873.5 1249.79  4879.3 1249.43
  4880.8 1249.70  4905.8 1247.93  4911.2 1247.41  4990.0 1245.65  4992.5 1243.65
  5007.5 1243.65  5010.0 1245.65  5010.6 1250.09  5028.6 1251.61  5068.4 1250.85
  5100.2 1251.37  5138.4 1250.69  5150.3 1250.78  5183.4 1251.95  5204.7 1253.34
  5211.2 1253.99  5219.3 1254.95  5231.1 1257.75  5239.9 1260.05  5246.5 1262.23
#Mann=3,-1,0
  4788.8    0.13       0  4990.0    0.05       0  5010.0    0.13       0
#XS Ineff=2,0
    0.00 4988.50 1250.47 5011.50    0.00 1250.39
Permanent Ineff=
       F       F
Bank Sta=4990,5010
XS Rating Curve= 0
Exp/Cntr=0.5,0.3

Type RM Length L Ch R = 1,65420,335,335,335
BEGIN DESCRIPTION:
South Fork 218.0
END DESCRIPTION:
XS GIS Cut Line= 3
      1437404.46       961051.92      1437337.99       960979.49
      1436868.05       960515.51
#Sta/Elev= 30
  4901.7 1263.74  4917.5 1261.32  4941.3 1255.87  4951.5 1254.42  4992.5 1242.22
  4993.0 1241.40  4994.5 1238.40  5005.5 1238.40  5007.0 1240.91  5008.9 1241.94
  5023.3 1244.67  5028.4 1244.23  5051.0 1244.54  5086.8 1245.09  5124.1 1246.22
  5171.3 1246.61  5217.7 1247.85  5252.9 1248.60  5313.5 1248.85  5354.5 1248.11
  5397.5 1248.82  5446.4 1248.95  5462.6 1249.51  5487.7 1248.58  5533.6 1248.72
  5592.7 1250.77  5611.7 1252.07  5638.9 1255.27  5655.0 1258.78  5660.4 1260.43
#Mann=5,-1,0
  4901.7    0.15       0  4993.0    0.05       0  5007.0    0.15       0
  5051.0    0.08       0  5217.7    0.15       0
Bank Sta=4993,5007
XS Rating Curve= 0
Exp/Cntr=0.3,0.1

Type RM Length L Ch R = 1,65085,265,265,265
BEGIN DESCRIPTION:
South Fork 217.0
END DESCRIPTION:
XS GIS Cut Line= 3
      1437608.45       960877.44      1437488.69       960723.82
      1437163.19       960312.39
#Sta/Elev= 30
  4760.8 1261.08  4818.5 1252.43  4848.6 1245.63  4866.5 1242.99  4886.7 1240.99
  4901.8 1239.88  4908.7 1239.81  4935.9 1241.29  4970.1 1240.77  4993.0 1237.99
  4994.5 1234.99  5005.5 1234.99  5007.0 1237.99  5015.0 1240.86  5017.0 1241.11
  5035.8 1242.86  5056.6 1243.29  5083.0 1243.44  5125.9 1242.82  5141.8 1243.21
  5168.6 1242.95  5233.3 1243.85  5271.8 1243.83  5383.5 1242.65  5406.2 1243.66
  5411.5 1244.37  5429.7 1251.85  5434.6 1254.77  5451.7 1263.65  5480.2 1276.71
#Mann=4,-1,0
  4760.8    0.15       0  4970.1    0.08       0  4993.0    0.05       0
  5007.0    0.08       0
#XS Ineff=2,0
    0.00 4900.00 1248.00 5233.30    0.00 1248.00
Permanent Ineff=
       F       F
Bank Sta=4993,5007
XS Rating Curve= 0
Exp/Cntr=0.3,0.1

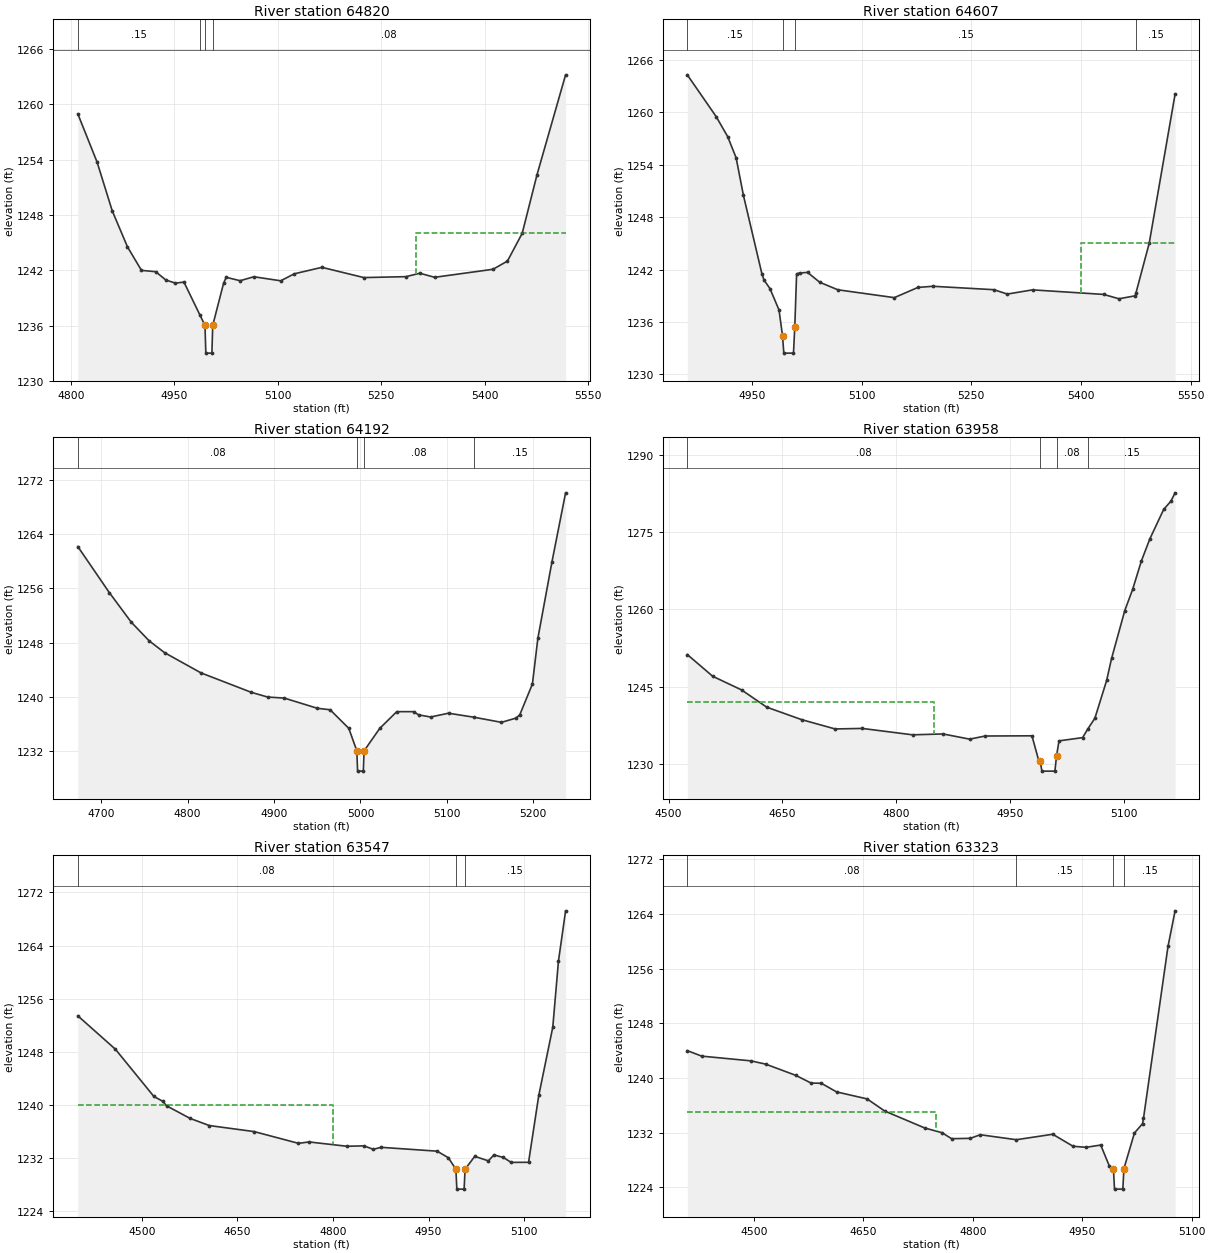
Type RM Length L Ch R = 1,64820,213,213,213
BEGIN DESCRIPTION:
South Fork 216.0
END DESCRIPTION:
XS GIS Cut Line= 3
      1437775.03       960675.02      1437619.42       960566.01
      1437210.07       960249.89
#Sta/Elev= 30
  4810.0 1258.95  4838.0 1253.71  4859.9 1248.44  4882.0 1244.53  4902.3 1241.98
  4922.9 1241.84  4937.6 1240.94  4951.4 1240.60  4963.9 1240.71  4986.8 1237.18
  4994.4 1236.01  4995.6 1233.01  5004.4 1233.01  5005.6 1236.01  5021.3 1240.57
  5025.1 1241.23  5045.3 1240.86  5065.2 1241.29  5104.2 1240.85  5123.9 1241.61
  5163.9 1242.31  5224.7 1241.20  5285.7 1241.30  5305.9 1241.67  5327.3 1241.23
  5412.0 1242.10  5432.9 1242.99  5454.3 1246.00  5475.8 1252.36  5517.2 1263.18
#Mann=4,-1,0
  4810.0    0.15       0  4986.8    0.08       0  4994.4    0.05       0
  5005.6    0.08       0
#XS Ineff=2,0
       0                 5300.00    0.00 1246.00
Permanent Ineff=
       F       F
Bank Sta=4994.4,5005.6
XS Rating Curve= 0
Exp/Cntr=0.3,0.1

Type RM Length L Ch R = 1,64607,415,415,415
BEGIN DESCRIPTION:
South Fork 215.0
END DESCRIPTION:
XS GIS Cut Line= 3
      1437910.55       960494.65      1437824.62       960481.63
      1437431.36       960054.52
#Sta/Elev= 30
  4861.3 1264.29  4900.8 1259.51  4916.5 1257.23  4928.1 1254.80  4938.1 1250.50
  4963.4 1241.52  4966.3 1240.80  4974.4 1239.83  4986.8 1237.38  4991.6 1234.44
  4993.4 1232.44  5006.6 1232.44  5008.4 1235.44  5010.9 1241.51  5015.1 1241.61
  5025.9 1241.68  5042.5 1240.55  5067.3 1239.69  5144.6 1238.79  5176.9 1239.96
  5197.4 1240.09  5280.8 1239.70  5299.2 1239.20  5333.7 1239.68  5431.0 1239.16
  5452.0 1238.66  5474.2 1239.00  5475.3 1239.34  5493.4 1245.02  5528.8 1262.08
#Mann=4,-1,0
  4861.3    0.15       0  4991.6    0.05       0  5008.4    0.15       0
  5475.3    0.15       0
#XS Ineff=2,0
       0                 5400.00    0.00 1245.00
Permanent Ineff=
       F       F
Bank Sta=4991.6,5008.4
XS Rating Curve= 0
Exp/Cntr=0.3,0.1

Type RM Length L Ch R = 1,64192,234,234,234
BEGIN DESCRIPTION:
South Fork 214.0
END DESCRIPTION:
XS GIS Cut Line= 4
      1437980.85       960367.03      1437793.37       960132.68
      1437665.78       959966.60      1437650.14       959913.92
#Sta/Elev= 30
  4672.9 1262.20  4709.3 1255.40  4734.9 1250.99  4755.4 1248.26  4773.3 1246.50
  4815.4 1243.51  4873.5 1240.64  4892.6 1239.93  4911.8 1239.78  4950.1 1238.27
  4964.9 1238.05  4986.5 1235.30  4995.8 1231.97  4996.7 1228.97  5003.3 1228.97
  5004.2 1231.97  5022.3 1235.29  5042.0 1237.77  5061.8 1237.77  5067.2 1237.30
  5081.2 1236.98  5101.9 1237.54  5131.2 1236.95  5163.2 1236.19  5180.1 1236.82
  5184.4 1237.31  5199.0 1241.86  5205.3 1248.62  5221.6 1259.92  5237.4 1270.15
#Mann=4,-1,0
  4672.9    0.08       0  4995.8    0.05       0  5004.2    0.08       0
  5131.2    0.15       0
Bank Sta=4995.8,5004.2
XS Rating Curve= 0
Exp/Cntr=0.3,0.1

Type RM Length L Ch R = 1,63958,411,411,411
BEGIN DESCRIPTION:
South Fork 213.0
END DESCRIPTION:
XS GIS Cut Line= 3
      1438098.06       960242.05      1438048.58       960033.72
      1437674.96       959824.98
#Sta/Elev= 30
  4524.7 1251.26  4558.2 1247.04  4596.1 1244.40  4629.3 1241.05  4675.1 1238.64
  4719.3 1236.83  4755.0 1236.93  4821.2 1235.69  4861.4 1235.86  4896.4 1234.85
  4916.8 1235.46  4978.4 1235.50  4987.4 1230.65  4989.2 1230.60  4991.5 1228.65
  5008.6 1228.65  5010.8 1231.65  5014.0 1234.52  5045.1 1235.15  5051.9 1236.83
  5061.2 1238.90  5076.7 1246.23  5083.2 1250.50  5100.6 1259.79  5110.9 1263.88
  5122.5 1269.43  5133.6 1273.70  5151.8 1279.41  5161.3 1281.00  5166.8 1282.62
#Mann=4,-1,0
  4524.7    0.08       0  4989.2    0.05       0  5010.8    0.08       0
  5051.9    0.15       0
#XS Ineff=2,0
    0.00 4850.00 1242.00               0
Permanent Ineff=
       F       F
Bank Sta=4989.2,5010.8
XS Rating Curve= 0
Exp/Cntr=0.3,0.1

Type RM Length L Ch R = 1,63547,224,224,224
BEGIN DESCRIPTION:
South Fork 212.0
END DESCRIPTION:
XS GIS Cut Line= 3
      1438202.24       960210.81      1438095.46       960091.01
      1438012.12       959492.06
#Sta/Elev= 30
  4399.7 1253.41  4458.7 1248.37  4519.0 1241.26  4533.1 1240.52  4538.9 1239.85
  4575.8 1237.95  4606.1 1236.87  4676.4 1235.96  4745.9 1234.19  4762.4 1234.40
  4821.9 1233.75  4848.5 1233.81  4863.3 1233.29  4875.4 1233.59  4963.4 1233.01
  4981.0 1232.02  4992.8 1230.29  4994.3 1227.29  5005.7 1227.29  5007.2 1230.29
  5022.4 1232.23  5043.8 1231.55  5052.4 1232.45  5067.2 1232.06  5079.5 1231.32
  5106.8 1231.33  5122.8 1241.40  5144.8 1251.69  5153.7 1261.65  5164.9 1269.23
#Mann=3,-1,0
  4399.7    0.08       0  4992.8    0.05       0  5007.2    0.15       0
#XS Ineff=2,0
    0.00 4800.00 1240.00               0
Permanent Ineff=
       F       F
Bank Sta=4992.8,5007.2
XS Rating Curve= 0
Exp/Cntr=0.3,0.1

Type RM Length L Ch R = 1,63323,482,482,482
BEGIN DESCRIPTION:
South Fork 211.0
END DESCRIPTION:
XS GIS Cut Line= 3
      1438460.06       960031.15      1438186.60       959525.91
      1438134.52       959447.78
#Sta/Elev= 30
  4408.9 1244.01  4428.7 1243.21  4495.9 1242.52  4516.3 1242.04  4557.5 1240.40
  4578.5 1239.27  4592.5 1239.24  4613.4 1237.98  4655.3 1236.95  4679.4 1235.18
  4734.4 1232.69  4757.8 1232.01  4771.1 1231.13  4796.8 1231.18  4810.2 1231.71
  4859.8 1230.98  4909.7 1231.78  4937.5 1230.02  4955.5 1229.87  4975.4 1230.20
  4987.1 1227.16  4992.8 1226.75  4994.3 1223.75  5005.7 1223.75  5007.2 1226.75
  5021.6 1231.96  5032.7 1233.33  5034.0 1234.10  5067.6 1259.27  5077.3 1264.47
#Mann=4,-1,0
  4408.9    0.08       0  4859.8    0.15       0  4992.8    0.05       0
  5007.2    0.15       0
#XS Ineff=2,0
    0.00 4750.00 1235.00               0
Permanent Ineff=
       F       F
Bank Sta=4992.8,5007.2
XS Rating Curve= 0
Exp/Cntr=0.3,0.1