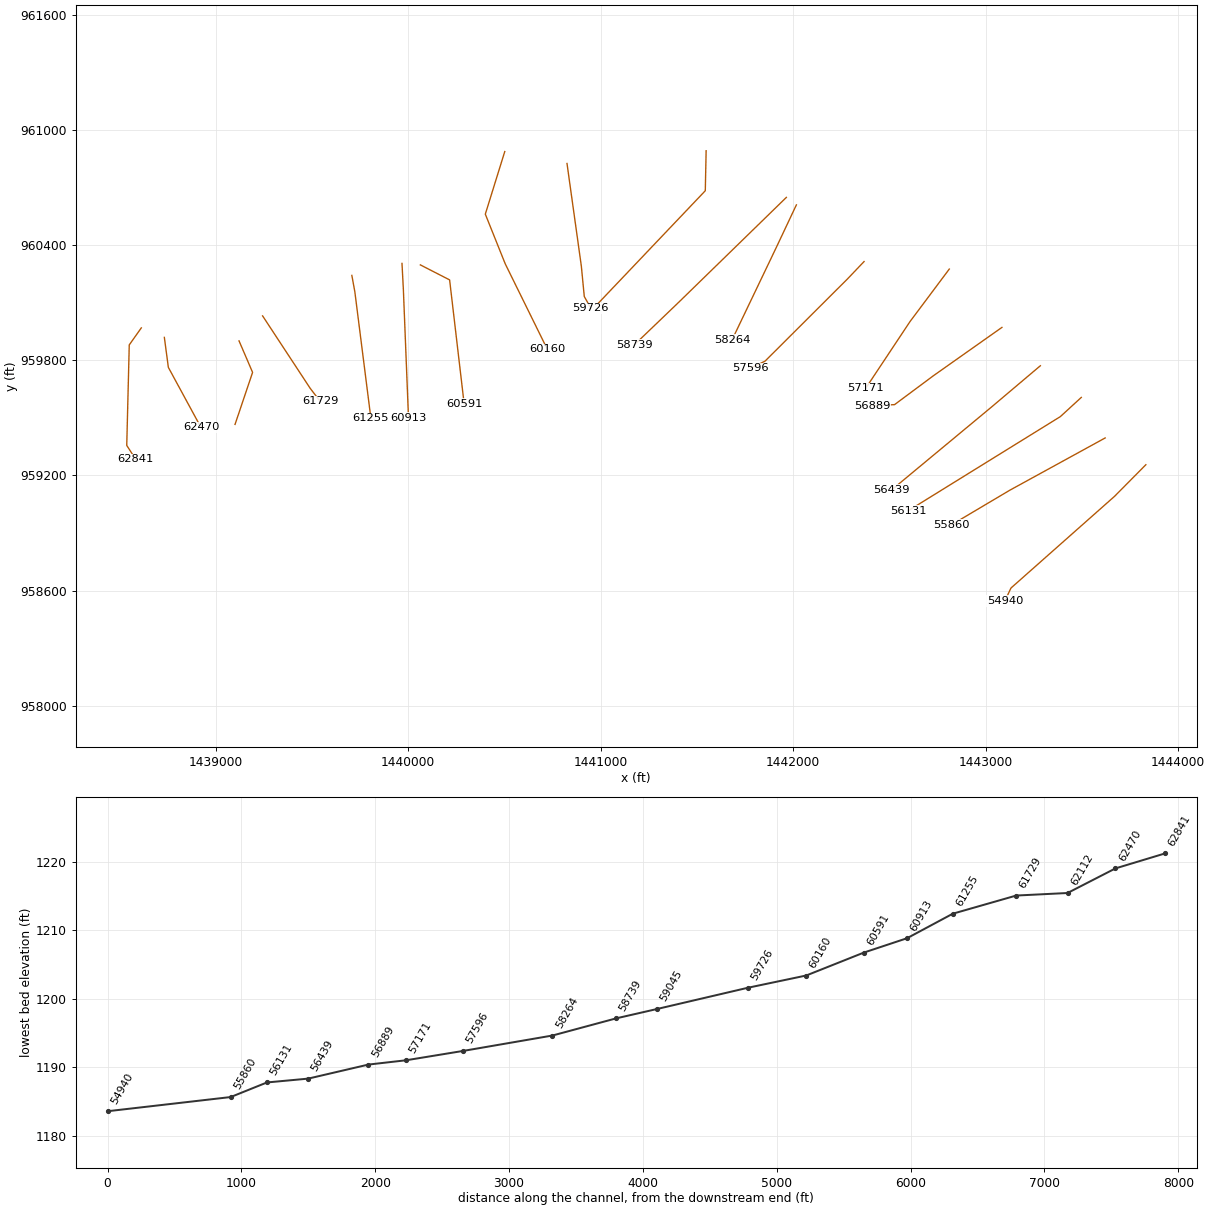
HEC-RAS study South Fork.prj: South Fork Limited Detail Study

--- South Fork.g01 (geometry) --- (continued)

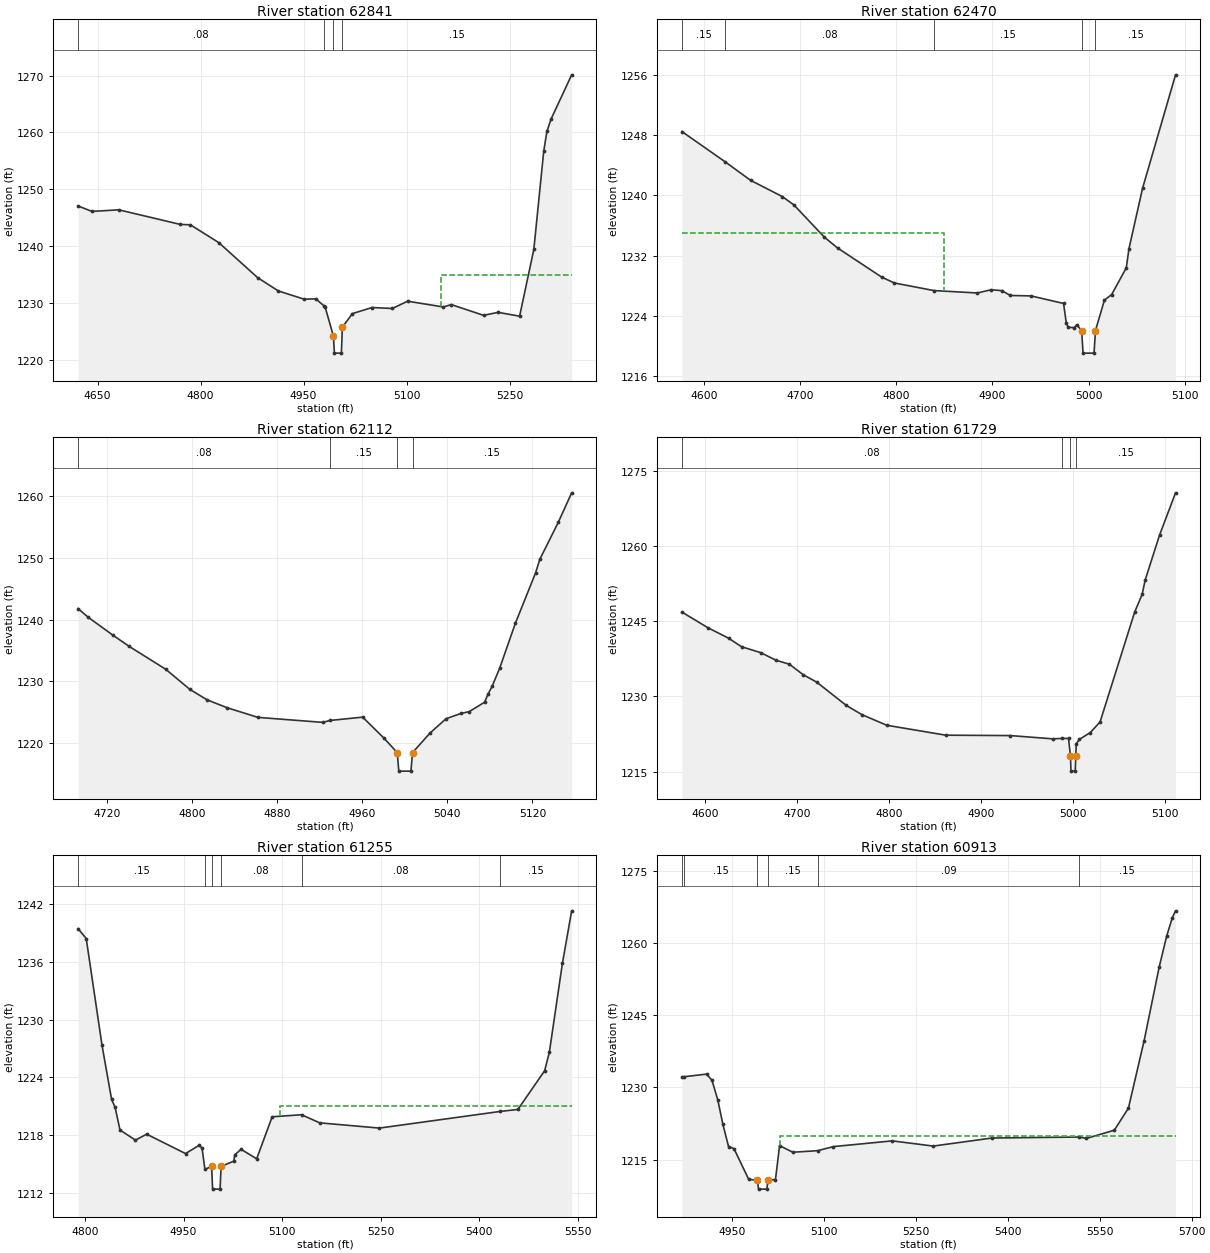
Type RM Length L Ch R = 1,62841,371,371,371
BEGIN DESCRIPTION:
South Fork 210.0
END DESCRIPTION:
XS GIS Cut Line= 4
      1438613.70       959968.63      1438551.19       959880.07
      1438538.16       959356.63      1438585.05       959283.71
#Sta/Elev= 30
  4621.7 1247.08  4641.9 1246.13  4681.0 1246.41  4770.4 1243.85  4785.2 1243.78
  4826.8 1240.63  4883.1 1234.50  4913.3 1232.16  4951.0 1230.71  4967.8 1230.78
  4979.3 1229.59  4981.3 1229.38  4993.5 1224.24  4994.9 1221.24  5005.1 1221.24
  5006.5 1225.80  5021.1 1228.18  5049.7 1229.25  5079.3 1229.08  5101.5 1230.36
  5153.4 1229.35  5165.2 1229.76  5212.1 1227.88  5233.3 1228.40  5264.6 1227.73
  5285.3 1239.45  5299.7 1256.68  5304.3 1260.17  5310.4 1262.35  5340.4 1270.12
#Mann=4,-1,0
  4621.7    0.08       0  4979.3    0.15       0  4993.5    0.05       0
  5006.5    0.15       0
#XS Ineff=2,0
       0                 5150.00    0.00 1235.00
Permanent Ineff=
       F       F
Bank Sta=4993.5,5006.5
XS Rating Curve= 0
Exp/Cntr=0.3,0.1

Type RM Length L Ch R = 1,62470,358,358,358
BEGIN DESCRIPTION:
South Fork 208.0
END DESCRIPTION:
XS GIS Cut Line= 3
      1438733.48       959919.09      1438754.31       959762.88
      1438923.59       959450.37
#Sta/Elev= 30
  4577.4 1248.48  4622.0 1244.49  4648.8 1242.00  4681.7 1239.85  4693.9 1238.72
  4725.3 1234.47  4739.1 1233.02  4785.1 1229.14  4798.1 1228.37  4839.3 1227.36
  4884.4 1227.04  4898.8 1227.47  4909.9 1227.35  4918.7 1226.71  4940.2 1226.65
  4974.0 1225.65  4976.9 1223.04  4978.9 1222.48  4985.0 1222.44  4987.8 1222.82
  4992.8 1222.05  4994.3 1219.05  5005.7 1219.05  5007.2 1222.05  5016.5 1226.10
  5024.0 1226.83  5039.2 1230.37  5042.0 1232.92  5056.1 1240.93  5090.4 1256.02
#Mann=5,-1,0
  4577.4    0.15       0  4622.0    0.08       0  4839.3    0.15       0
  4992.8    0.05       0  5007.2    0.15       0
#XS Ineff=2,0
    0.00 4850.00 1235.00               0
Permanent Ineff=
       F       F
Bank Sta=4992.8,5007.2
XS Rating Curve= 0
Exp/Cntr=0.3,0.1

Type RM Length L Ch R = 1,62112,383,383,383
BEGIN DESCRIPTION:
South Fork 207.0
END DESCRIPTION:
XS GIS Cut Line= 3
      1439121.48       959900.95      1439191.81       959736.84
      1439100.67       959466.01
#Sta/Elev= 30
  4692.6 1241.80  4702.2 1240.38  4725.6 1237.46  4740.7 1235.67  4775.1 1231.96
  4797.7 1228.71  4814.0 1227.01  4832.7 1225.74  4861.8 1224.17  4922.8 1223.36
  4929.5 1223.67  4960.3 1224.21  4980.6 1220.76  4992.8 1218.46  4994.3 1215.46
  5005.7 1215.46  5007.2 1218.46  5023.7 1221.64  5038.7 1223.95  5052.8 1224.81
  5060.6 1225.11  5075.0 1226.63  5078.1 1227.89  5082.2 1229.26  5089.2 1232.15
  5104.0 1239.45  5122.9 1247.56  5127.0 1249.81  5144.3 1255.78  5156.9 1260.56
#Mann=4,-1,0
  4692.6    0.08       0  4929.5    0.15       0  4992.8    0.05       0
  5007.2    0.15       0
Bank Sta=4992.8,5007.2
XS Rating Curve= 0
Exp/Cntr=0.3,0.1

Type RM Length L Ch R = 1,61729,474,474,474
BEGIN DESCRIPTION:
South Fork 206.0
END DESCRIPTION:
XS GIS Cut Line= 3
      1439243.87       960031.14      1439491.29       959653.51
      1439543.38       959585.79
#Sta/Elev= 30
  4574.5 1246.85  4602.8 1243.72  4625.2 1241.64  4639.5 1239.92  4660.1 1238.76
  4676.7 1237.24  4691.4 1236.44  4706.2 1234.37  4721.2 1232.85  4753.1 1228.23
  4770.3 1226.37  4797.3 1224.25  4861.4 1222.27  4931.7 1222.19  4977.7 1221.54
  4987.5 1221.62  4995.0 1221.62  4997.1 1218.09  4997.7 1215.09  5002.3 1215.09
  5002.9 1218.09  5003.4 1220.53  5006.8 1221.43  5018.6 1222.78  5029.3 1224.91
  5066.9 1246.83  5075.1 1250.40  5078.4 1253.27  5094.0 1262.22  5111.4 1270.67
#Mann=4,-1,0
  4574.5    0.08       0  4987.5    0.15       0  4997.1    0.05       0
  5002.9    0.15       0
Bank Sta=4997.1,5002.9
XS Rating Curve= 0
Exp/Cntr=0.3,0.1

Type RM Length L Ch R = 1,61255,342,342,342
BEGIN DESCRIPTION:
South Fork 204.0
END DESCRIPTION:
XS GIS Cut Line= 3
      1439707.43       960242.07      1439723.06       960156.11
      1439806.40       959497.23
#Sta/Elev= 30
  4789.5 1239.40  4801.9 1238.38  4825.9 1227.34  4840.5 1221.73  4845.8 1220.92
  4853.3 1218.56  4876.9 1217.51  4893.9 1218.13  4953.1 1216.12  4974.3 1217.00
  4978.3 1216.65  4982.6 1214.49  4992.8 1214.79  4994.3 1212.44  5005.7 1212.44
  5007.2 1214.79  5026.6 1215.34  5028.1 1216.00  5037.7 1216.56  5061.4 1215.58
  5085.0 1219.93  5129.7 1220.14  5157.4 1219.30  5248.3 1218.76  5431.9 1220.48
  5459.1 1220.69  5499.8 1224.69  5507.0 1226.60  5526.9 1235.81  5541.0 1241.25
#Mann=6,-1,0
  4789.5    0.15       0  4982.6    0.08       0  4992.8    0.05       0
  5007.2    0.08       0  5129.7    0.08       0  5431.9    0.15       0
#XS Ineff=2,0
       0                 5097.30    0.00 1221.00
Permanent Ineff=
       F       F
Bank Sta=4992.8,5007.2
XS Rating Curve= 0
Exp/Cntr=0.3,0.1

Type RM Length L Ch R = 1,60913,322,322,322
BEGIN DESCRIPTION:
South Fork 203.0
END DESCRIPTION:
XS GIS Cut Line= 3
      1439967.85       960304.52      1439974.84       960173.00
      1440001.71       959499.84
#Sta/Elev= 30
  4868.3 1232.18  4871.1 1232.21  4908.6 1232.77  4917.3 1231.48  4926.8 1227.39
  4935.0 1222.38  4944.3 1217.71  4953.2 1217.27  4977.2 1210.89  4991.4 1210.70
  4993.2 1208.86  5006.8 1208.86  5008.6 1210.70  5020.9 1210.86  5027.6 1217.90
  5049.2 1216.53  5089.7 1216.85  5115.4 1217.70  5211.5 1218.89  5278.3 1217.81
  5373.9 1219.48  5516.2 1219.69  5528.4 1219.40  5573.8 1221.11  5596.8 1225.68
  5622.5 1239.75  5647.0 1255.01  5659.2 1261.44  5668.4 1265.26  5673.7 1266.71
#Mann=6,-1,0
  4868.3     0.1       0  4871.1    0.15       0  4991.4    0.05       0
  5008.6    0.15       0  5089.7    0.09       0  5516.2    0.15       0
#XS Ineff=2,0
       0                 5027.60    0.00 1220.00
Permanent Ineff=
       F       F
Bank Sta=4991.4,5008.6
XS Rating Curve= 0
Exp/Cntr=0.3,0.1

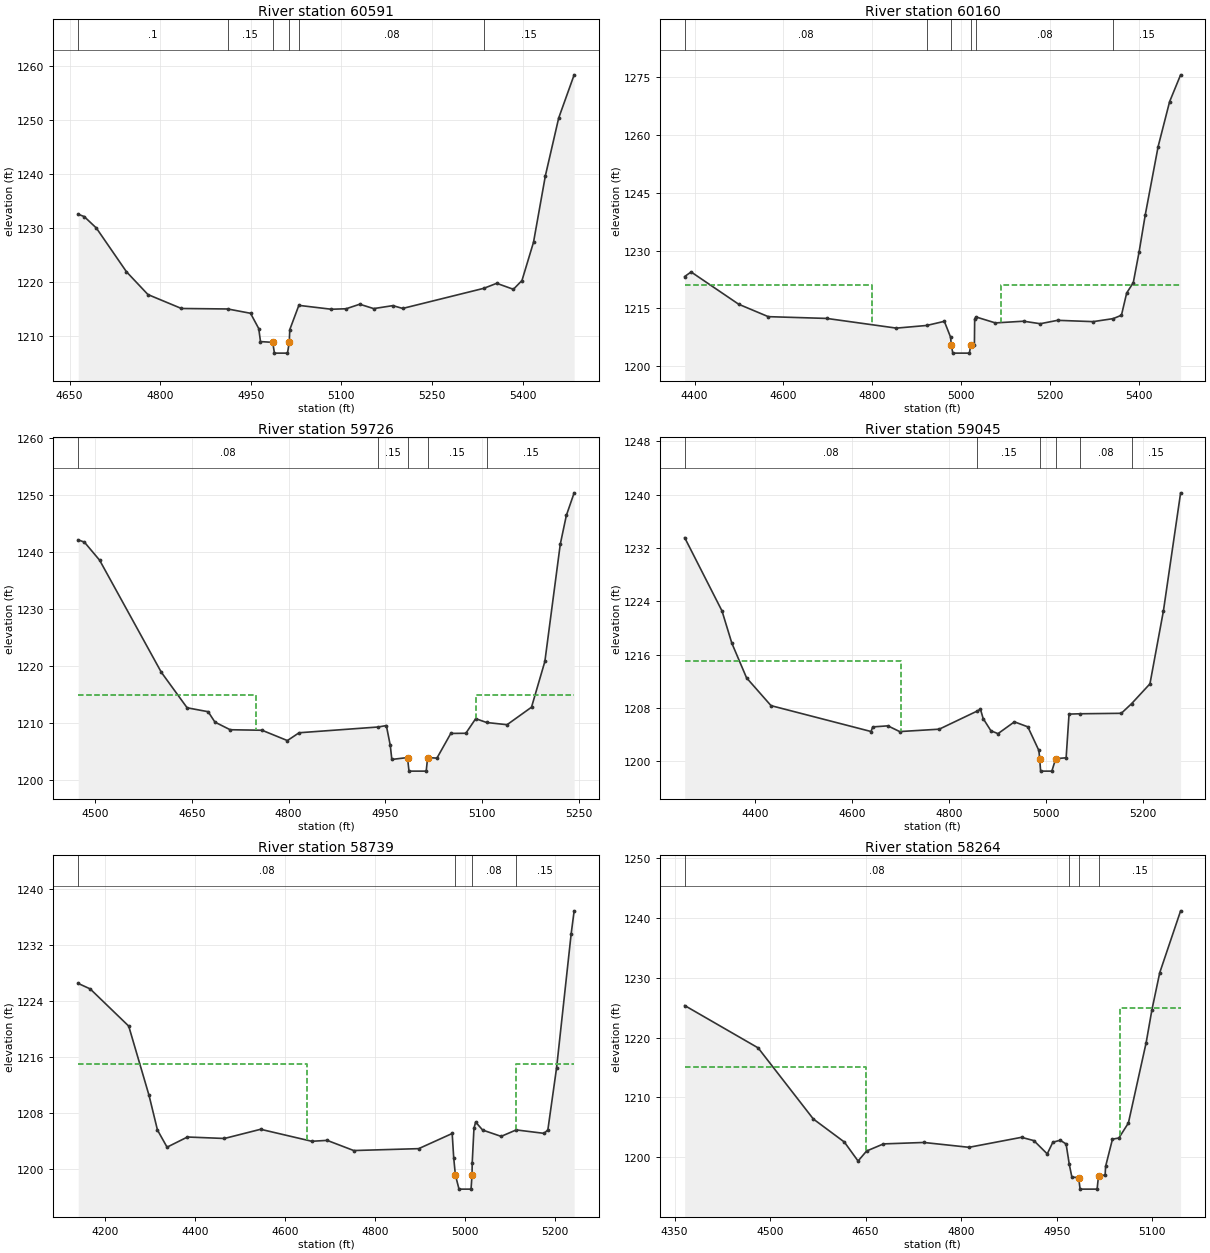
Type RM Length L Ch R = 1,60591,431,431,431
BEGIN DESCRIPTION:
South Fork 202.0
END DESCRIPTION:
XS GIS Cut Line= 3
      1440063.30       960296.76      1440215.25       960218.61
      1440290.77       959572.78
#Sta/Elev= 30
  4664.3 1232.53  4674.2 1232.10  4694.3 1229.98  4744.2 1221.86  4779.8 1217.63
  4835.2 1215.05  4911.9 1214.96  4949.6 1214.16  4963.2 1211.32  4966.1 1208.91
  4986.3 1208.77  4989.2 1206.77  5010.8 1206.77  5013.7 1208.77  5014.6 1211.14
  5029.6 1215.63  5083.4 1214.91  5107.9 1215.00  5130.4 1215.84  5153.5 1215.03
  5185.2 1215.58  5201.5 1215.06  5335.8 1218.79  5357.2 1219.72  5384.8 1218.61
  5399.0 1220.24  5418.1 1227.33  5437.8 1239.69  5459.8 1250.38  5485.4 1258.39
#Mann=6,-1,0
  4664.3     0.1       0  4911.9    0.15       0  4986.3    0.05       0
  5013.7    0.15       0  5029.6    0.08       0  5335.8    0.15       0
Bank Sta=4986.3,5013.7
XS Rating Curve= 0
Exp/Cntr=0.3,0.1

Type RM Length L Ch R = 1,60160,434,434,434
BEGIN DESCRIPTION:
South Fork 201.0
END DESCRIPTION:
XS GIS Cut Line= 4
      1440501.70       960887.00      1440400.68       960561.02
      1440504.31       960301.95      1440723.04       959856.67
#Sta/Elev= 30
  4377.8 1223.27  4392.3 1224.45  4499.5 1216.08  4566.0 1212.87  4697.7 1212.41
  4854.4 1209.90  4922.8 1210.59  4962.3 1211.66  4976.2 1207.61  4978.2 1205.45
  4981.3 1203.42  5018.7 1203.42  5021.8 1205.45  5030.0 1205.51  5030.6 1212.16
  5033.3 1212.80  5077.2 1211.25  5140.6 1211.69  5178.3 1211.04  5217.3 1211.92
  5297.2 1211.58  5342.4 1212.36  5361.0 1213.24  5372.8 1219.01  5387.6 1221.66
  5400.7 1229.62  5414.7 1239.31  5443.6 1256.95  5469.4 1268.57  5494.2 1275.53
#Mann=6,-1,0
  4377.8    0.08       0  4922.8    0.15       0  4978.2    0.05       0
  5021.8    0.15       0  5033.3    0.08       0  5342.4    0.15       0
#XS Ineff=2,0
    0.00 4800.00 1221.00 5090.10    0.00 1221.00
Permanent Ineff=
       F       F
Bank Sta=4978.2,5021.8
XS Rating Curve= 0
Exp/Cntr=0.3,0.1

Type RM Length L Ch R = 1,59726,681,681,681
BEGIN DESCRIPTION:
South Fork 199.0
END DESCRIPTION:
XS GIS Cut Line= 4
      1440825.00       960824.97      1440899.56       960289.94
      1440914.70       960132.29      1440948.78       960071.00
#Sta/Elev= 30
  4474.0 1242.20  4483.6 1241.80  4507.2 1238.63  4602.8 1218.98  4642.8 1212.75
  4675.4 1212.06  4685.9 1210.24  4709.5 1208.90  4758.9 1208.81  4798.2 1207.00
  4816.4 1208.37  4938.9 1209.38  4951.6 1209.63  4957.7 1206.15  4960.1 1203.69
  4984.4 1204.02  4986.7 1201.64  5013.4 1201.64  5015.6 1204.02  5030.0 1203.92
  5051.5 1208.25  5074.8 1208.28  5090.1 1210.84  5107.0 1210.17  5138.7 1209.78
  5176.6 1212.85  5197.3 1220.87  5221.2 1241.44  5230.6 1246.48  5242.7 1250.45
#Mann=5,-1,0
  4474.0    0.08       0  4938.9    0.15       0  4984.4    0.05       0
  5015.6    0.15       0  5107.0    0.15       0
#XS Ineff=2,0
    0.00 4750.00 1215.00 5090.10    0.00 1215.00
Permanent Ineff=
       F       F
Bank Sta=4984.4,5015.6
XS Rating Curve= 0
Exp/Cntr=0.3,0.1

Type RM Length L Ch R = 1,59045,306,306,306
BEGIN DESCRIPTION:
South Fork 197.0
END DESCRIPTION:
XS GIS Cut Line= 3
      1441547.71       960891.34      1441543.37       960683.02
      1440983.50       960092.77
#Sta/Elev= 30
  4255.0 1233.54  4331.9 1222.55  4352.2 1217.71  4382.5 1212.52  4432.9 1208.35
  4639.0 1204.47  4642.5 1205.16  4673.7 1205.32  4698.0 1204.46  4779.5 1204.82
  4857.5 1207.53  4864.5 1207.81  4870.0 1206.42  4886.0 1204.58  4900.6 1204.15
  4934.4 1205.92  4962.1 1205.17  4984.8 1201.63  4986.5 1200.40  4988.4 1198.53
  5011.6 1198.53  5019.5 1200.40  5041.0 1200.53  5047.0 1207.08  5069.1 1207.13
  5154.7 1207.20  5175.8 1208.64  5213.7 1211.62  5241.5 1222.57  5276.9 1240.26
#Mann=6,-1,0
  4255.0    0.08       0  4857.5    0.15       0  4986.5    0.05       0
  5019.5    0.15       0  5069.1    0.08       0  5175.8    0.15       0
#XS Ineff=2,0
    0.00 4700.00 1215.00               0
Permanent Ineff=
       F       F
Bank Sta=4986.5,5019.5
XS Rating Curve= 0
Exp/Cntr=0.3,0.1

Type RM Length L Ch R = 1,58739,475,475,475
BEGIN DESCRIPTION:
South Fork 196.0
END DESCRIPTION:
XS GIS Cut Line= 3
      1441964.36       960648.29      1441400.14       960097.09
      1441174.43       959880.06
#Sta/Elev= 30
  4140.6 1226.48  4167.2 1225.70  4252.8 1220.40  4298.0 1210.51  4316.7 1205.58
  4338.0 1203.14  4383.3 1204.59  4465.4 1204.38  4545.9 1205.69  4659.6 1203.98
  4693.7 1204.11  4752.8 1202.66  4897.1 1202.93  4971.5 1205.09  4974.9 1201.63
  4978.6 1199.17  4986.7 1197.16  5013.4 1197.16  5015.6 1199.17  5016.0 1200.88
  5019.9 1205.83  5023.6 1206.72  5039.2 1205.58  5080.3 1204.68  5113.8 1205.60
  5175.8 1205.11  5184.1 1205.61  5203.5 1214.47  5235.9 1233.57  5242.5 1236.83
#Mann=4,-1,0
  4140.6    0.08       0  4978.6    0.05       0  5015.6    0.08       0
  5113.8    0.15       0
#XS Ineff=2,0
    0.00 4650.00 1215.00 5113.50    0.00 1215.00
Permanent Ineff=
       F       F
Bank Sta=4978.6,5015.6
XS Rating Curve= 0
Exp/Cntr=0.3,0.1

Type RM Length L Ch R = 1,58264,668,668,668
BEGIN DESCRIPTION:
South Fork 194.0
END DESCRIPTION:
XS GIS Cut Line= 3
      1442016.48       960609.27      1441912.30       960387.88
      1441682.24       959906.07
#Sta/Elev= 30
  4365.9 1225.35  4481.2 1218.27  4567.9 1206.38  4616.6 1202.53  4638.1 1199.36
  4651.5 1201.03  4678.0 1202.22  4741.4 1202.46  4812.3 1201.65  4894.7 1203.32
  4914.1 1202.77  4935.1 1200.55  4943.9 1202.50  4955.5 1202.83  4964.7 1202.21
  4969.7 1198.81  4973.8 1196.66  4984.4 1196.60  4986.7 1194.66  5013.4 1194.66
  5015.6 1196.88  5026.0 1197.01  5026.7 1198.45  5037.5 1203.01  5047.6 1203.21
  5062.5 1205.71  5090.4 1219.15  5099.5 1224.67  5111.7 1230.83  5144.5 1241.18
#Mann=4,-1,0
  4365.9    0.08       0  4969.7    0.15       0  4984.4    0.05       0
  5015.6    0.15       0
#XS Ineff=2,0
    0.00 4650.00 1215.00 5050.00    0.00 1225.00
Permanent Ineff=
       F       F
Bank Sta=4984.4,5015.6
XS Rating Curve= 0
Exp/Cntr=0.3,0.1

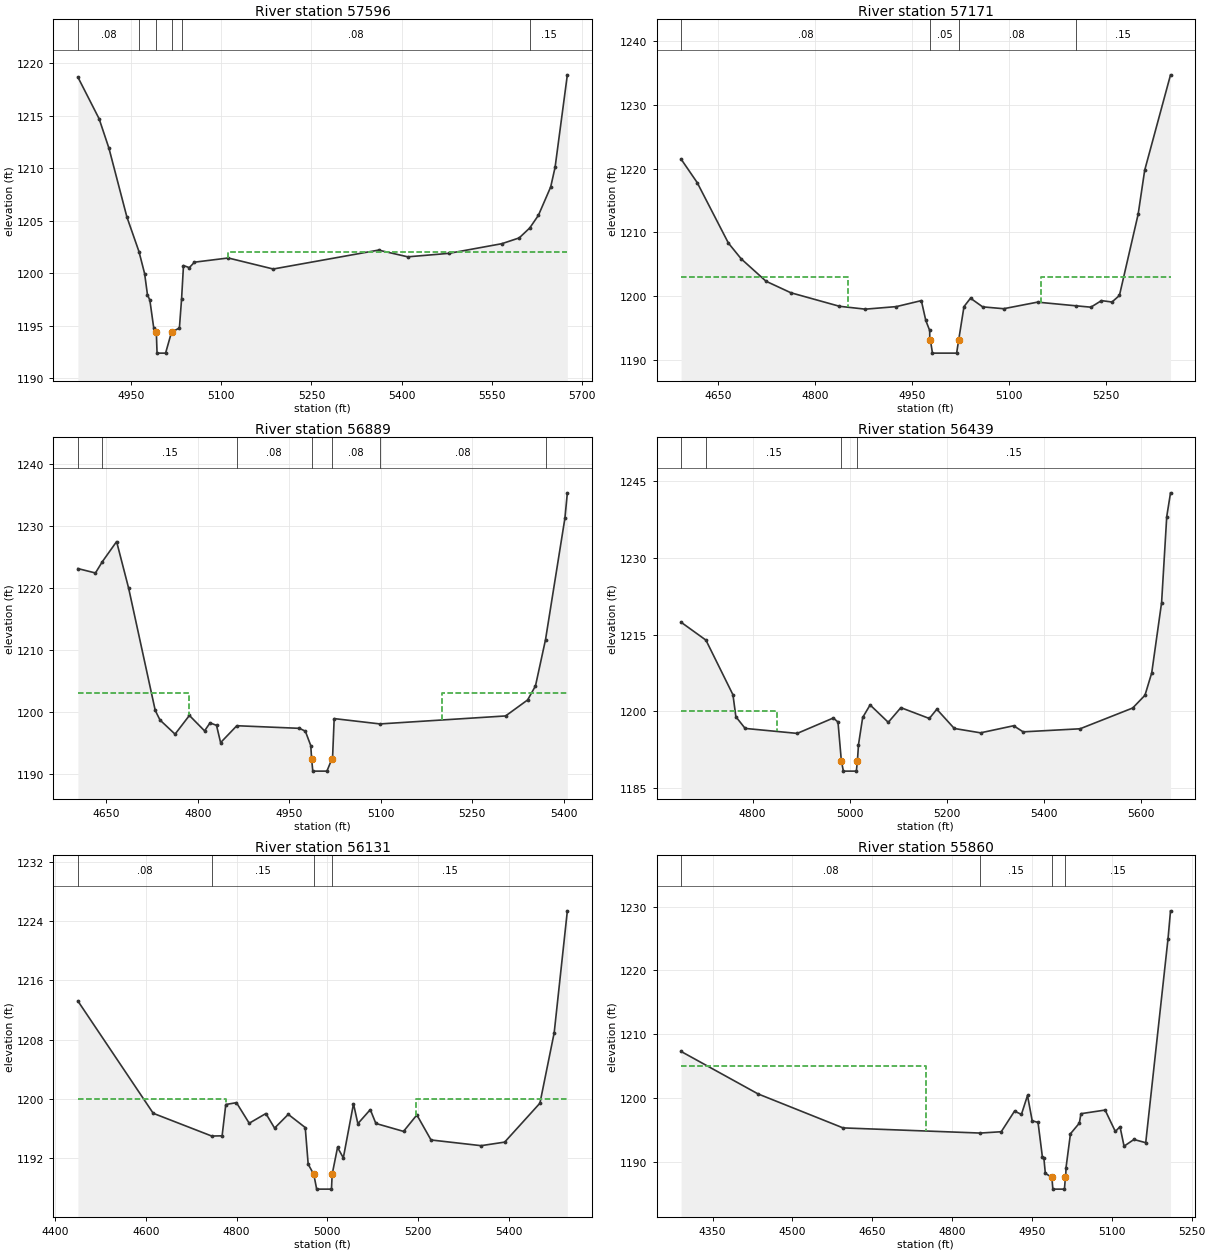
Type RM Length L Ch R = 1,57596,425,425,425
BEGIN DESCRIPTION:
South Fork 192.0
END DESCRIPTION:
XS GIS Cut Line= 4
      1442368.05       960314.12      1442281.22       960222.95
      1441853.70       959795.44      1441777.79       959758.56
#Sta/Elev= 30
  4861.1 1218.69  4896.4 1214.73  4912.8 1211.92  4942.7 1205.37  4962.8 1202.08
  4972.2 1199.98  4976.9 1197.98  4980.9 1197.45  4987.3 1194.84  4991.7 1194.41
  4992.9 1192.41  5007.1 1192.41  5017.0 1194.41  5030.1 1194.80  5033.7 1197.54
  5036.9 1200.75  5046.6 1200.55  5055.2 1201.07  5111.4 1201.47  5186.3 1200.42
  5361.6 1202.22  5410.3 1201.58  5478.8 1201.91  5566.9 1202.83  5595.8 1203.38
  5613.4 1204.33  5627.8 1205.53  5648.3 1208.24  5655.6 1210.11  5676.0 1218.91
#Mann=6,-1,0
  4861.1    0.08       0  4962.8    0.15       0  4991.7    0.05       0
  5017.0    0.15       0  5033.7    0.08       0  5613.4    0.15       0
#XS Ineff=2,0
       0                 5111.40    0.00 1202.00
Permanent Ineff=
       F       F
Bank Sta=4991.7,5017
XS Rating Curve= 0
Exp/Cntr=0.3,0.1

Type RM Length L Ch R = 1,57171,282,282,282
BEGIN DESCRIPTION:
South Fork 191.0
END DESCRIPTION:
XS GIS Cut Line= 3
      1442810.72       960275.02      1442606.74       960001.60
      1442376.73       959654.41
#Sta/Elev= 30
  4592.2 1221.50  4617.1 1217.82  4665.5 1208.31  4685.3 1205.84  4723.7 1202.33
  4762.2 1200.52  4837.4 1198.40  4877.4 1197.95  4925.4 1198.35  4964.1 1199.29
  4971.0 1196.17  4977.0 1194.61  4977.2 1193.05  4978.2 1193.05  4981.3 1191.05
  5018.7 1191.05  5021.8 1193.05  5030.1 1198.35  5040.2 1199.67  5059.0 1198.31
  5091.5 1198.02  5143.9 1199.05  5203.0 1198.48  5226.5 1198.26  5242.9 1199.29
  5259.2 1199.07  5270.7 1200.10  5299.7 1212.86  5309.8 1219.75  5349.8 1234.72
#Mann=4,-1,0
  4592.2    0.08       0  4978.2    0.05       0  5021.8    0.08       0
  5203.0    0.15       0
#XS Ineff=2,0
    0.00 4850.00 1203.00 5150.00    0.00 1203.00
Permanent Ineff=
       F       F
Bank Sta=4978.2,5021.8
XS Rating Curve= 0
Exp/Cntr=0.3,0.1

Type RM Length L Ch R = 1,56889,450,450,450
BEGIN DESCRIPTION:
South Fork 190.0
END DESCRIPTION:
XS GIS Cut Line= 4
      1443084.19       959971.23      1442728.27       959719.48
      1442526.46       959568.98      1442411.41       959563.23
#Sta/Elev= 30
  4603.1 1223.12  4631.9 1222.41  4643.1 1224.22  4666.6 1227.48  4686.4 1219.93
  4730.0 1200.21  4737.8 1198.67  4762.5 1196.39  4786.0 1199.41  4810.9 1196.92
  4819.9 1198.21  4830.5 1197.81  4837.2 1195.02  4863.8 1197.75  4966.5 1197.33
  4976.2 1196.87  4985.1 1194.54  4986.5 1192.44  4988.4 1190.42  5011.6 1190.42
  5020.0 1192.44  5020.8 1192.42  5023.5 1198.90  5098.7 1198.04  5304.7 1199.33
  5340.8 1201.91  5353.7 1204.17  5370.2 1211.65  5402.0 1231.25  5406.0 1235.35
#Mann=7,-1,0
  4603.1    0.08       0  4643.1    0.15       0  4863.8    0.08       0
  4986.5    0.05       0  5020.0    0.08       0  5098.7    0.08       0
  5370.2    0.15       0
#XS Ineff=2,0
    0.00 4786.00 1203.00 5200.00    0.00 1203.00
Permanent Ineff=
       F       F
Bank Sta=4986.5,5020
XS Rating Curve= 0
Exp/Cntr=0.3,0.1

Type RM Length L Ch R = 1,56439,308,308,308
BEGIN DESCRIPTION:
South Fork 189.0
END DESCRIPTION:
XS GIS Cut Line= 3
      1443283.83       959771.57      1443027.75       959554.55
      1442511.28       959124.88
#Sta/Elev= 30
  4652.6 1217.41  4703.8 1213.92  4759.4 1203.26  4765.4 1198.98  4784.5 1196.70
  4891.7 1195.73  4965.9 1198.73  4975.6 1197.95  4982.5 1190.38  4986.7 1188.37
  5013.4 1188.37  5015.6 1190.38  5017.8 1193.53  5026.4 1198.83  5041.7 1201.28
  5079.1 1197.89  5105.0 1200.75  5163.6 1198.64  5179.0 1200.44  5215.0 1196.69
  5269.0 1195.84  5337.1 1197.22  5356.7 1196.03  5473.9 1196.63  5582.2 1200.68
  5607.5 1203.17  5621.4 1207.54  5641.7 1221.24  5652.3 1238.03  5660.1 1242.65
#Mann=4,-1,0
  4652.6    0.08       0  4703.8    0.15       0  4982.5    0.05       0
  5015.6    0.15       0
#XS Ineff=2,0
    0.00 4850.00 1200.00 5179.00    0.00 1200.00
Permanent Ineff=
       F       F
Bank Sta=4982.5,5015.6
XS Rating Curve= 0
Exp/Cntr=0.3,0.1

Type RM Length L Ch R = 1,56131,271,271,271
BEGIN DESCRIPTION:
South Fork 188.0
END DESCRIPTION:
XS GIS Cut Line= 3
      1443496.48       959606.62      1443387.99       959506.81
      1442597.10       959016.05
#Sta/Elev= 30
  4450.3 1213.22  4616.3 1198.05  4745.1 1194.98  4768.0 1195.01  4776.1 1199.24
  4799.6 1199.49  4827.7 1196.71  4864.4 1198.02  4883.6 1196.05  4913.7 1197.91
  4951.1 1196.13  4957.6 1191.17  4970.0 1189.80  4976.3 1187.81  5008.9 1187.81
  5010.4 1189.80  5022.3 1193.45  5035.0 1192.03  5057.4 1199.34  5067.0 1196.65
  5094.4 1198.55  5106.7 1196.68  5167.6 1195.61  5197.0 1197.83  5228.2 1194.45
  5338.5 1193.68  5390.4 1194.16  5468.1 1199.42  5499.5 1208.93  5528.5 1225.40
#Mann=4,-1,0
  4450.3    0.08       0  4745.1    0.15       0  4970.0    0.05       0
  5010.4    0.15       0
#XS Ineff=2,0
    0.00 4776.10 1200.00 5195.50    0.00 1200.00
Permanent Ineff=
       F       F
Bank Sta=4970,5010.4
XS Rating Curve= 0
Exp/Cntr=0.3,0.1

Type RM Length L Ch R = 1,55860,920,920,920
BEGIN DESCRIPTION:
South Fork 186.0
END DESCRIPTION:
XS GIS Cut Line= 3
      1443620.52       959395.46      1443124.19       959122.68
      1442820.65       958942.20
#Sta/Elev= 30
  4290.7 1207.29  4435.4 1200.62  4595.0 1195.29  4852.9 1194.48  4892.2 1194.69
  4917.1 1197.92  4930.1 1197.41  4941.5 1200.38  4950.3 1196.41  4961.3 1196.15
  4969.6 1190.65  4972.2 1190.60  4975.0 1188.15  4987.3 1187.54  4989.1 1185.68
  5010.9 1185.68  5012.7 1187.54  5013.3 1187.68  5013.9 1189.07  5022.2 1194.37
  5038.9 1196.04  5041.9 1197.52  5087.3 1198.09  5106.5 1194.73  5115.3 1195.48
  5122.9 1192.42  5141.4 1193.47  5163.6 1192.97  5205.5 1225.00  5210.2 1229.36
#Mann=4,-1,0
  4290.7    0.08       0  4852.9    0.15       0  4987.3    0.05       0
  5012.7    0.15       0
#XS Ineff=2,0
    0.00 4750.00 1205.00               0
Permanent Ineff=
       F       F
Bank Sta=4987.3,5012.7
XS Rating Curve= 0
Exp/Cntr=0.3,0.1

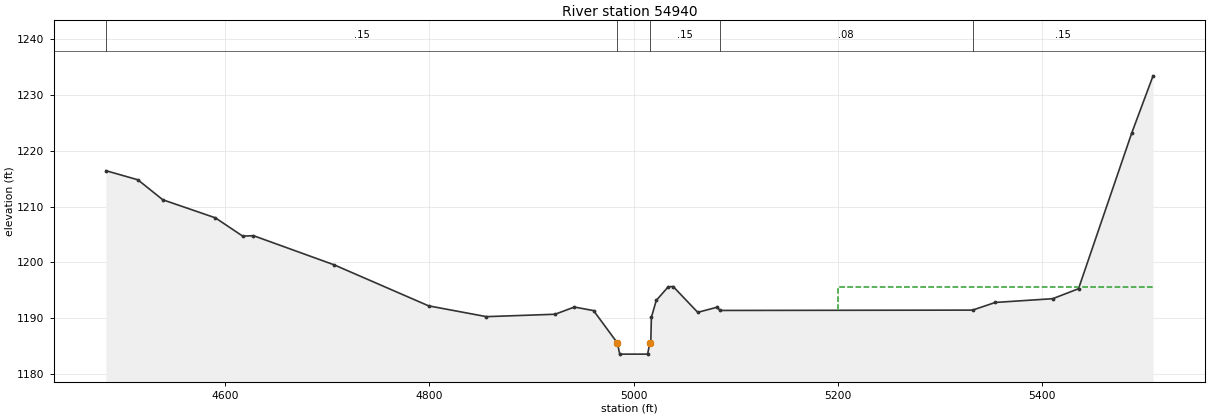
Type RM Length L Ch R = 1,54940,512,512,512
BEGIN DESCRIPTION:
South Fork 183.0
END DESCRIPTION:
XS GIS Cut Line= 4
      1443831.80       959256.01      1443669.75       959091.92
      1443130.96       958613.60      1443099.58       958546.36
#Sta/Elev= 30
  4483.3 1216.41  4514.6 1214.78  4539.0 1211.21  4590.5 1207.98  4617.3 1204.70
  4627.8 1204.79  4706.7 1199.58  4799.3 1192.24  4855.9 1190.31  4923.1 1190.74
  4942.0 1192.03  4960.8 1191.39  4984.1 1185.61  4986.4 1183.61  5013.7 1183.61
  5015.9 1185.61  5016.8 1185.61  5017.4 1190.19  5022.2 1193.22  5033.9 1195.65
  5038.7 1195.70  5062.8 1191.08  5081.8 1192.00  5084.6 1191.42  5331.9 1191.48
  5354.1 1192.85  5410.3 1193.52  5435.6 1195.30  5487.6 1223.08  5508.6 1233.37
#Mann=5,-1,0
  4483.3    0.15       0  4984.1    0.05       0  5015.9    0.15       0
  5084.6    0.08       0  5331.9    0.15       0
#XS Ineff=2,0
       0                 5200.00    0.00 1195.70
Permanent Ineff=
       F       F
Bank Sta=4984.1,5015.9
XS Rating Curve= 0
Exp/Cntr=0.3,0.1