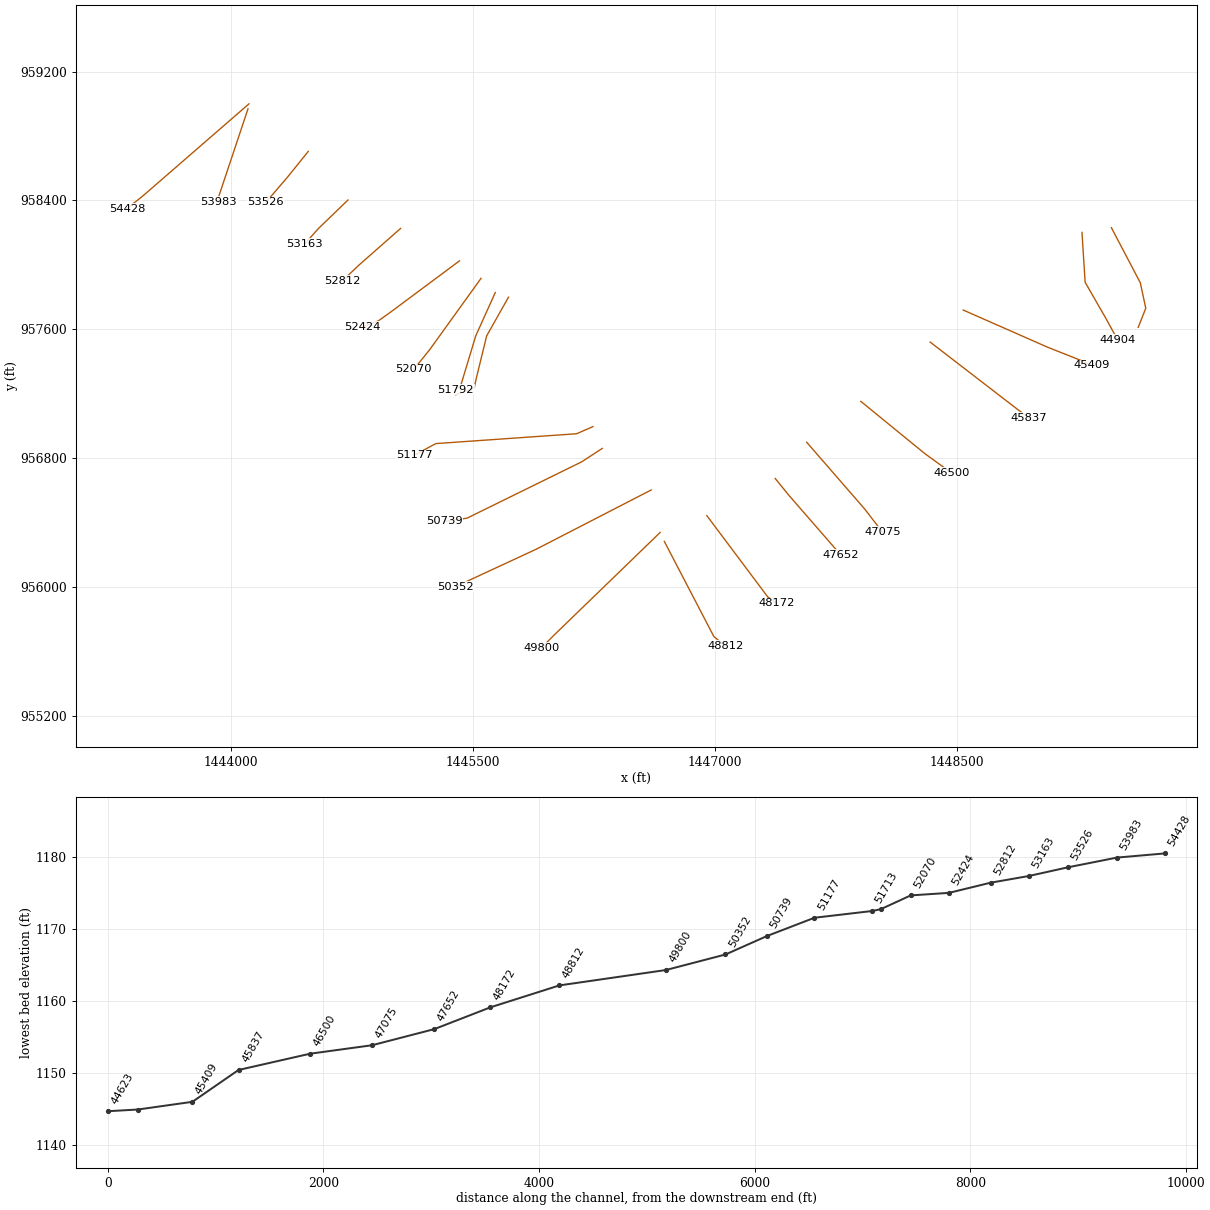
HEC-RAS study South Fork.prj: South Fork Limited Detail Study

--- South Fork.g01 (geometry) --- (continued)

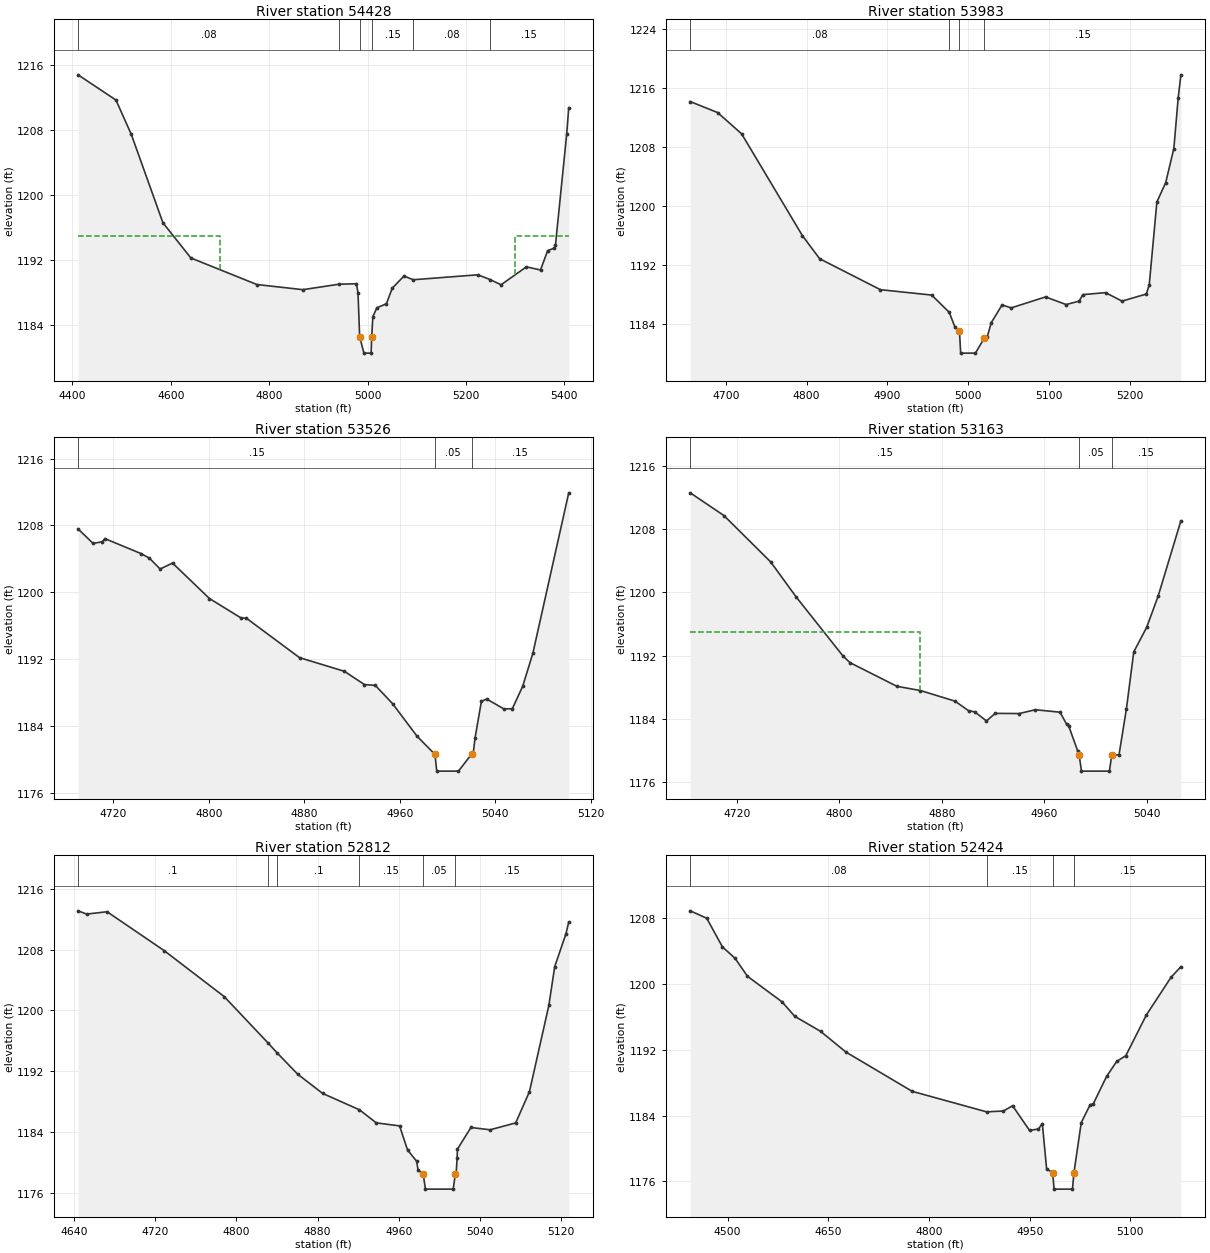
Type RM Length L Ch R = 1,54428,445,445,445
BEGIN DESCRIPTION:
South Fork 181.0
END DESCRIPTION:
XS GIS Cut Line= 3
      1444112.76       958999.62      1443454.40       958427.40
      1443355.99       958349.49
#Sta/Elev= 30
  4411.4 1214.81  4488.5 1211.70  4519.7 1207.47  4583.9 1196.61  4640.8 1192.27
  4775.1 1189.00  4868.6 1188.37  4941.9 1189.04  4977.5 1189.10  4980.7 1187.97
  4984.0 1182.60  4992.7 1180.56  5007.3 1180.56  5008.5 1182.60  5010.9 1185.04
  5019.0 1186.14  5038.4 1186.63  5050.3 1188.55  5074.2 1190.05  5092.9 1189.59
  5224.3 1190.20  5249.1 1189.62  5271.5 1188.97  5323.2 1191.18  5351.8 1190.79
  5366.4 1193.18  5380.2 1193.49  5382.2 1193.86  5405.1 1207.54  5409.2 1210.76
#Mann=6,-1,0
  4411.4    0.08       0  4941.9    0.15       0  4984.0    0.05       0
  5008.5    0.15       0  5092.9    0.08       0  5249.1    0.15       0
#XS Ineff=2,0
    0.00 4700.00 1195.00 5300.00    0.00 1195.00
Permanent Ineff=
       F       F
Bank Sta=4984,5008.5
XS Rating Curve= 0
Exp/Cntr=0.3,0.1

Type RM Length L Ch R = 1,53983,457,457,457
BEGIN DESCRIPTION:
South Fork 180.0
END DESCRIPTION:
XS GIS Cut Line= 3
      1444106.60       958968.82      1443926.13       958427.40
      1443926.13       958390.51
#Sta/Elev= 30
  4656.0 1214.12  4689.9 1212.63  4719.6 1209.75  4795.0 1195.91  4816.3 1192.79
  4891.5 1188.59  4955.0 1187.86  4976.8 1185.51  4984.0 1183.46  4989.4 1182.98
  4990.9 1179.98  5009.1 1179.98  5020.0 1181.98  5023.8 1182.17  5028.7 1184.10
  5042.2 1186.52  5053.5 1186.12  5096.0 1187.61  5121.5 1186.57  5137.6 1187.04
  5142.2 1187.92  5170.3 1188.19  5190.7 1187.04  5220.8 1188.00  5224.4 1189.23
  5233.9 1200.50  5244.8 1203.12  5254.9 1207.75  5260.3 1214.67  5263.6 1217.75
#Mann=4,-1,0
  4656.0    0.08       0  4976.8    0.15       0  4989.4    0.05       0
  5020.0    0.15       0
Bank Sta=4989.4,5020
XS Rating Curve= 0
Exp/Cntr=0.3,0.1

Type RM Length L Ch R = 1,53526,363,363,363
BEGIN DESCRIPTION:
South Fork 179.0
END DESCRIPTION:
XS GIS Cut Line= 3
      1444479.91       958704.30      1444352.73       958546.36
      1444217.36       958388.41
#Sta/Elev= 30
  4690.6 1207.58  4703.2 1205.85  4710.8 1206.05  4713.1 1206.42  4743.4 1204.63
  4750.4 1204.08  4759.3 1202.79  4769.7 1203.50  4800.6 1199.26  4826.9 1196.95
  4831.6 1196.90  4876.0 1192.19  4913.5 1190.56  4930.4 1188.97  4939.5 1188.87
  4953.9 1186.69  4974.5 1182.78  4989.4 1180.62  4990.9 1178.62  5009.1 1178.62
  5020.0 1180.64  5021.4 1180.71  5023.0 1182.61  5028.3 1186.98  5032.9 1187.23
  5047.2 1186.05  5054.2 1186.09  5062.9 1188.78  5071.4 1192.73  5101.4 1211.90
#Mann=3,-1,0
  4690.6    0.15       0  4989.4    0.05       0  5020.0    0.15       0
Bank Sta=4989.4,5020
XS Rating Curve= 0
Exp/Cntr=0.3,0.1

Type RM Length L Ch R = 1,53163,351,351,351
BEGIN DESCRIPTION:
South Fork 177.0
END DESCRIPTION:
XS GIS Cut Line= 3
      1444726.01       958402.78      1444543.48       958226.40
      1444457.34       958130.01
#Sta/Elev= 30
  4683.6 1212.59  4709.9 1209.72  4746.4 1203.86  4766.5 1199.39  4802.9 1191.96
  4808.4 1191.12  4845.0 1188.13  4863.3 1187.60  4890.3 1186.26  4900.9 1185.05
  4905.8 1184.90  4914.9 1183.75  4921.7 1184.71  4940.5 1184.69  4953.0 1185.17
  4972.3 1184.86  4977.5 1183.33  4979.0 1183.17  4986.1 1179.97  4986.8 1179.43
  4987.3 1179.41  4989.1 1177.41  5010.9 1177.41  5012.7 1179.41  5018.4 1179.47
  5024.2 1185.31  5029.9 1192.48  5040.0 1195.59  5048.9 1199.51  5066.7 1209.05
#Mann=3,-1,0
  4683.6    0.15       0  4987.3    0.05       0  5012.7    0.15       0
#XS Ineff=2,0
    0.00 4863.00 1195.00               0
Permanent Ineff=
       F       F
Bank Sta=4987.3,5012.7
XS Rating Curve= 0
Exp/Cntr=0.3,0.1

Type RM Length L Ch R = 1,52812,388,388,388
BEGIN DESCRIPTION:
South Fork 176.0
END DESCRIPTION:
XS GIS Cut Line= 3
      1445052.11       958226.39      1444793.70       957998.74
      1444693.23       957902.37
#Sta/Elev= 30
  4644.0 1213.11  4652.4 1212.68  4672.6 1212.99  4728.9 1207.87  4788.0 1201.83
  4831.4 1195.70  4840.4 1194.39  4860.4 1191.62  4885.1 1189.08  4921.3 1186.93
  4937.9 1185.21  4960.9 1184.81  4968.7 1181.65  4977.7 1180.16  4979.1 1178.99
  4984.1 1178.49  4986.4 1176.49  5013.7 1176.49  5015.9 1178.49  5016.6 1178.49
  5017.6 1180.57  5017.9 1181.75  5031.2 1184.60  5050.1 1184.30  5075.3 1185.20
  5088.9 1189.32  5108.0 1200.66  5113.8 1205.77  5124.9 1210.11  5127.6 1211.64
#Mann=6,-1,0
  4644.0     0.1       0  4831.4    0.15       0  4840.4     0.1       0
  4921.3    0.15       0  4984.1    0.05       0  5015.9    0.15       0
Bank Sta=4984.1,5015.9
XS Rating Curve= 0
Exp/Cntr=0.3,0.1

Type RM Length L Ch R = 1,52424,354,354,354
BEGIN DESCRIPTION:
South Fork 175.0
END DESCRIPTION:
XS GIS Cut Line= 4
      1445417.19       958025.39      1444982.39       957701.35
      1444913.20       957652.19      1444816.26       957615.20
#Sta/Elev= 30
  4444.3 1208.85  4468.9 1207.95  4492.3 1204.47  4511.0 1203.10  4529.6 1200.90
  4581.1 1197.80  4599.9 1196.05  4638.5 1194.22  4676.2 1191.71  4774.9 1186.94
  4885.8 1184.45  4910.8 1184.55  4924.5 1185.19  4949.8 1182.19  4963.0 1182.37
  4968.8 1183.03  4975.2 1177.53  4984.1 1177.07  4986.4 1175.07  5013.7 1175.07
  5015.9 1177.07  5026.8 1183.15  5040.1 1185.32  5044.6 1185.41  5064.6 1188.76
  5079.6 1190.57  5093.2 1191.27  5123.8 1196.21  5160.5 1200.78  5175.2 1202.07
#Mann=4,-1,0
  4444.3    0.08       0  4885.8    0.15       0  4984.1    0.05       0
  5015.9    0.15       0
Bank Sta=4984.1,5015.9
XS Rating Curve= 0
Exp/Cntr=0.3,0.1

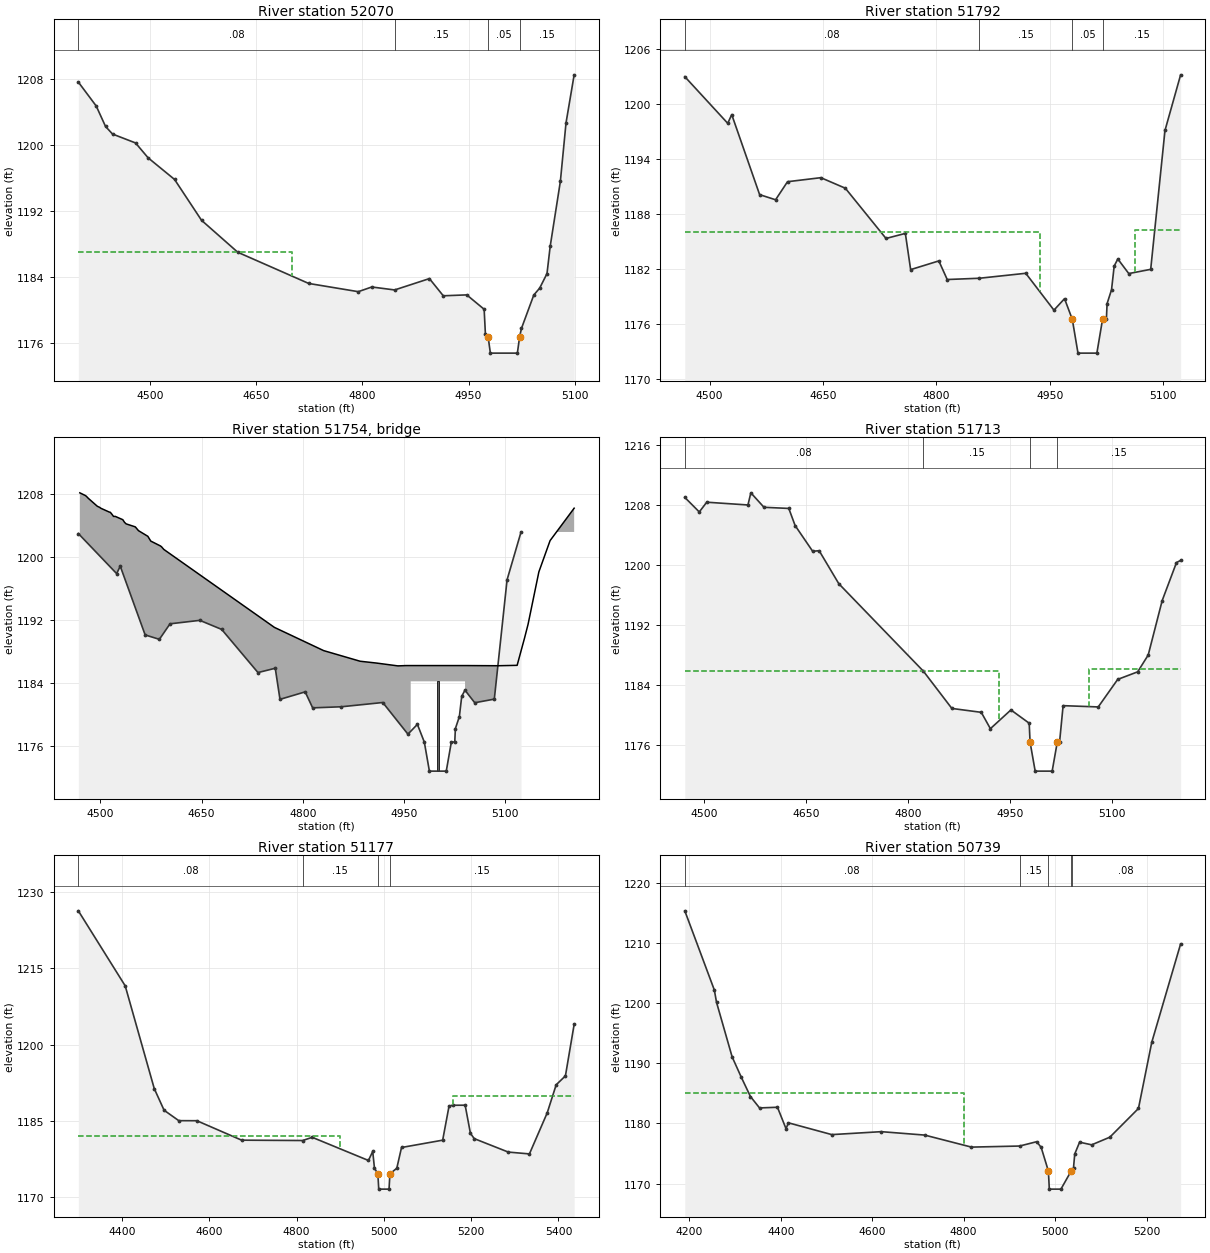
Type RM Length L Ch R = 1,52070,278,278,278
BEGIN DESCRIPTION:
South Fork 174.0
END DESCRIPTION:
XS GIS Cut Line= 3
      1445550.50       957916.68      1445230.56       957471.63
      1445134.17       957352.69
#Sta/Elev= 30
  4398.2 1207.67  4423.5 1204.76  4436.7 1202.27  4446.6 1201.35  4479.1 1200.27
  4496.9 1198.46  4534.3 1195.83  4572.4 1190.87  4623.7 1186.98  4724.0 1183.19
  4794.1 1182.19  4813.2 1182.76  4845.5 1182.40  4894.7 1183.78  4914.3 1181.69
  4947.5 1181.80  4972.1 1180.05  4973.9 1177.03  4977.7 1176.72  4980.9 1174.72
  5019.1 1174.72  5022.3 1176.72  5024.9 1177.73  5042.3 1181.78  5050.7 1182.63
  5061.0 1184.39  5065.5 1187.70  5079.9 1195.60  5087.9 1202.71  5099.4 1208.55
#Mann=4,-1,0
  4398.2    0.08       0  4845.5    0.15       0  4977.7    0.05       0
  5022.3    0.15       0
#XS Ineff=2,0
    0.00 4700.00 1187.00               0
Permanent Ineff=
       F       F
Bank Sta=4977.7,5022.3
XS Rating Curve= 0
Exp/Cntr=0.5,0.3

Type RM Length L Ch R = 1,51792,79,79,79
BEGIN DESCRIPTION:
Zephyr Mountain Park Rd US
END DESCRIPTION:
XS GIS Cut Line= 5
      1445638.70       957828.49      1445517.70       957559.83
      1445443.13       957312.27      1445426.23       957256.27
      1445393.66       957226.23
#Sta/Elev= 30
  4467.3 1202.96  4524.1 1197.87  4529.4 1198.82  4566.3 1190.09  4587.4 1189.53
  4603.2 1191.50  4647.3 1191.94  4679.7 1190.79  4733.5 1185.31  4759.1 1185.86
  4766.1 1181.91  4803.4 1182.86  4814.5 1180.83  4857.2 1180.97  4918.4 1181.51
  4955.7 1177.49  4969.7 1178.74  4980.0 1176.48  4987.5 1172.80  5012.5 1172.80
  5020.0 1176.48  5025.1 1176.51  5026.0 1178.20  5031.9 1179.72  5035.4 1182.30
  5040.2 1183.07  5054.7 1181.48  5083.7 1181.94  5102.6 1197.09  5123.3 1203.16
#Mann=4,-1,0
  4467.3    0.08       0  4857.2    0.15       0  4980.0    0.05       0
  5020.0    0.15       0
#XS Ineff=2,0
    0.00 4936.80 1186.00 5063.30    0.00 1186.24
Permanent Ineff=
       F       F
Bank Sta=4980,5020
XS Rating Curve= 0
Exp/Cntr=0.5,0.3

Type RM Length L Ch R =3,51754,,,
BEGIN DESCRIPTION:
Zephyr Mountain Park Rd TOR
Structure ID: LDS_SFMR_05
Approximate Survey Structure
END DESCRIPTION:
Bridge Culvert--1,0,-1,-1,0
Deck Dist Width WeirC Skew NumUp NumDn MinLoCord MaxHiCord MaxSubmerge Is_Ogee
23,30,3,,44,44,,,0.95,0,1,1,,,
  4469.5  4477.4  4479.1  4482.0  4495.5  4498.6  4500.7  4513.1  4514.7  4517.1
  4519.5  4522.0  4533.2  4535.7  4538.1  4551.3  4551.6  4551.9  4556.4  4570.3
  4574.4  4575.1  4575.9  4589.1  4590.7  4593.9  4757.8  4830.8  4884.9  4909.1
  4940.8  4953.0  4959.8  4959.8  5040.3  5040.3  5042.5  5089.9  5117.5  5128.5
  5133.7  5149.7  5166.3  5202.0
 1208.13 1207.80 1207.70 1207.44 1206.42 1206.30 1206.17 1205.69 1205.66 1205.41
 1205.13 1205.14 1204.72 1204.39 1204.19 1203.82 1203.79 1203.79 1203.33 1202.61
 1202.04 1201.97 1201.95 1201.38 1201.27 1200.95 1191.05 1188.10 1186.75 1186.52
 1186.16 1186.20 1186.20 1186.20 1186.20 1186.20 1186.20 1186.18 1186.23 1189.70
 1191.44 1198.09 1202.06 1206.18
 1152.80 1152.80 1152.80 1152.80 1152.80 1152.80 1152.80 1152.80 1152.80 1152.80
 1152.80 1152.80 1152.80 1152.80 1152.80 1152.80 1152.80 1152.80 1152.80 1152.80
 1152.80 1152.80 1152.80 1152.80 1152.80 1152.80 1152.80 1152.80 1152.80 1152.80
 1152.80 1152.80 1152.80 1184.20 1184.20 1152.80 1152.80 1152.80 1152.80 1152.80
 1152.80 1152.80 1152.80 1152.80
  4469.5  4477.4  4479.1  4482.0  4495.5  4498.6  4500.7  4513.1  4514.7  4517.1
  4519.5  4522.0  4533.2  4535.7  4538.1  4551.3  4551.6  4551.9  4556.4  4570.3
  4574.4  4575.1  4575.9  4589.1  4590.7  4593.9  4757.8  4830.8  4884.9  4909.1
  4940.8  4953.0  4959.8  4959.8  5040.3  5040.3  5042.5  5089.9  5117.5  5128.5
  5133.7  5149.7  5166.3  5202.0
 1208.13 1207.80 1207.70 1207.44 1206.42 1206.30 1206.17 1205.69 1205.66 1205.41
 1205.13 1205.14 1204.72 1204.39 1204.19 1203.82 1203.79 1203.79 1203.33 1202.61
 1202.04 1201.97 1201.95 1201.38 1201.27 1200.95 1191.05 1188.10 1186.75 1186.52
 1186.16 1186.20 1186.20 1186.20 1186.20 1186.20 1186.20 1186.18 1186.23 1189.70
 1191.44 1198.09 1202.06 1206.18
 1152.80 1152.80 1152.80 1152.80 1152.80 1152.80 1152.80 1152.80 1152.80 1152.80
 1152.80 1152.80 1152.80 1152.80 1152.80 1152.80 1152.80 1152.80 1152.80 1152.80
 1152.80 1152.80 1152.80 1152.80 1152.80 1152.80 1152.80 1152.80 1152.80 1152.80
 1152.80 1152.80 1152.80 1184.20 1184.20 1152.80 1152.80 1152.80 1152.80 1152.80
 1152.80 1152.80 1152.80 1152.80
Pier Skew, UpSta & Num, DnSta & Num=,5000,2,5000,2,0,0,0,0,0
       3       3
 1172.80 1184.20
       3       3
 1172.55 1184.20
Abutment Skew #Up #Dn=,2,2
  4959.8  4974.8
 1184.20 1177.64
  4959.8  4974.9
 1184.20 1179.17
Abutment Skew #Up #Dn=,2,2
  5025.3  5040.3
 1176.89 1184.20
  5025.3  5040.3
 1178.39 1184.20
BR Coef=1,1,0,1.25,0,,,0.8,0,2,0,
WSPro=,,,, 1 ,,,, 0 ,,,, 0 ,,,,-1 ,-1 ,-1 , 0 , 0 , 0 , 0 , 0
BC Design=,,0,,0,,,,,,

Type RM Length L Ch R = 1,51713,536,536,536
BEGIN DESCRIPTION:
Zephyr Mountain Park Rd DS
END DESCRIPTION:
XS GIS Cut Line= 5
      1445720.76       957799.82      1445585.38       957559.83
      1445520.87       957295.77      1445508.44       957236.09
      1445394.52       957194.82
#Sta/Elev= 30
  4472.0 1209.05  4493.3 1207.11  4504.3 1208.41  4564.9 1208.04  4569.2 1209.66
  4588.5 1207.73  4625.0 1207.58  4634.3 1205.30  4660.1 1201.87  4669.7 1201.94
  4698.6 1197.54  4823.1 1185.87  4864.9 1180.91  4908.2 1180.39  4921.6 1178.21
  4951.8 1180.71  4978.7 1178.94  4980.0 1176.41  4987.5 1172.55  5012.5 1172.55
  5020.0 1176.41  5023.4 1176.42  5028.6 1181.28  5080.3 1181.11  5108.9 1184.78
  5138.3 1185.79  5153.8 1188.03  5174.4 1195.30  5195.4 1200.36  5201.5 1200.65
#Mann=4,-1,0
  4472.0    0.08       0  4823.1    0.15       0  4980.0    0.05       0
  5020.0    0.15       0
#XS Ineff=2,0
    0.00 4933.80 1185.88 5066.30    0.00 1186.15
Permanent Ineff=
       F       F
Bank Sta=4980,5020
XS Rating Curve= 0
Exp/Cntr=0.5,0.3

Type RM Length L Ch R = 1,51177,438,438,438
BEGIN DESCRIPTION:
South Fork 171.0
END DESCRIPTION:
XS GIS Cut Line= 4
      1446244.01       956996.53      1446142.48       956952.27
      1445270.17       956891.21      1445137.30       956819.47
#Sta/Elev= 30
  4299.8 1226.29  4407.2 1211.55  4473.8 1191.36  4496.3 1187.11  4530.0 1185.06
  4571.4 1185.05  4674.0 1181.23  4813.8 1181.16  4835.8 1181.79  4964.6 1177.24
  4974.4 1179.02  4978.4 1175.72  4986.2 1174.61  4988.2 1171.61  5011.8 1171.61
  5013.8 1174.61  5029.6 1175.72  5040.4 1179.79  5134.7 1181.23  5149.3 1187.92
  5157.3 1188.09  5186.2 1188.10  5198.3 1182.57  5207.1 1181.53  5285.0 1178.89
  5333.5 1178.53  5374.2 1186.58  5394.8 1192.11  5416.0 1193.86  5436.0 1203.99
#Mann=4,-1,0
  4299.8    0.08       0  4813.8    0.15       0  4986.2    0.05       0
  5013.8    0.15       0
#XS Ineff=2,0
    0.00 4900.00 1182.00 5157.30    0.00 1190.00
Permanent Ineff=
       F       F
Bank Sta=4986.2,5013.8
XS Rating Curve= 0
Exp/Cntr=0.3,0.1

Type RM Length L Ch R = 1,50739,387,387,387
BEGIN DESCRIPTION:
South Fork 169.0
END DESCRIPTION:
XS GIS Cut Line= 4
      1446301.33       956861.12      1446173.73       956777.79
      1445464.19       956428.69      1445324.79       956408.00
#Sta/Elev= 30
  4190.3 1215.38  4254.9 1202.20  4259.7 1200.15  4293.8 1191.08  4313.8 1187.70
  4333.8 1184.49  4353.7 1182.59  4392.9 1182.70  4411.6 1179.14  4416.9 1180.11
  4511.7 1178.15  4620.0 1178.64  4714.9 1178.07  4817.1 1176.07  4922.4 1176.25
  4959.7 1176.97  4969.5 1176.02  4985.3 1172.08  4987.3 1169.08  5012.7 1169.08
  5035.0 1172.08  5036.5 1172.24  5040.2 1172.63  5042.9 1174.93  5053.5 1176.89
  5079.9 1176.45  5119.6 1177.72  5182.2 1182.50  5211.3 1193.51  5274.4 1209.88
#Mann=5,-1,0
  4190.3    0.08       0  4922.4    0.15       0  4985.3    0.05       0
  5035.0    0.15       0  5036.5    0.08       0
#XS Ineff=2,0
    0.00 4800.00 1185.00               0
Permanent Ineff=
       F       F
Bank Sta=4985.3,5035
XS Rating Curve= 0
Exp/Cntr=0.3,0.1

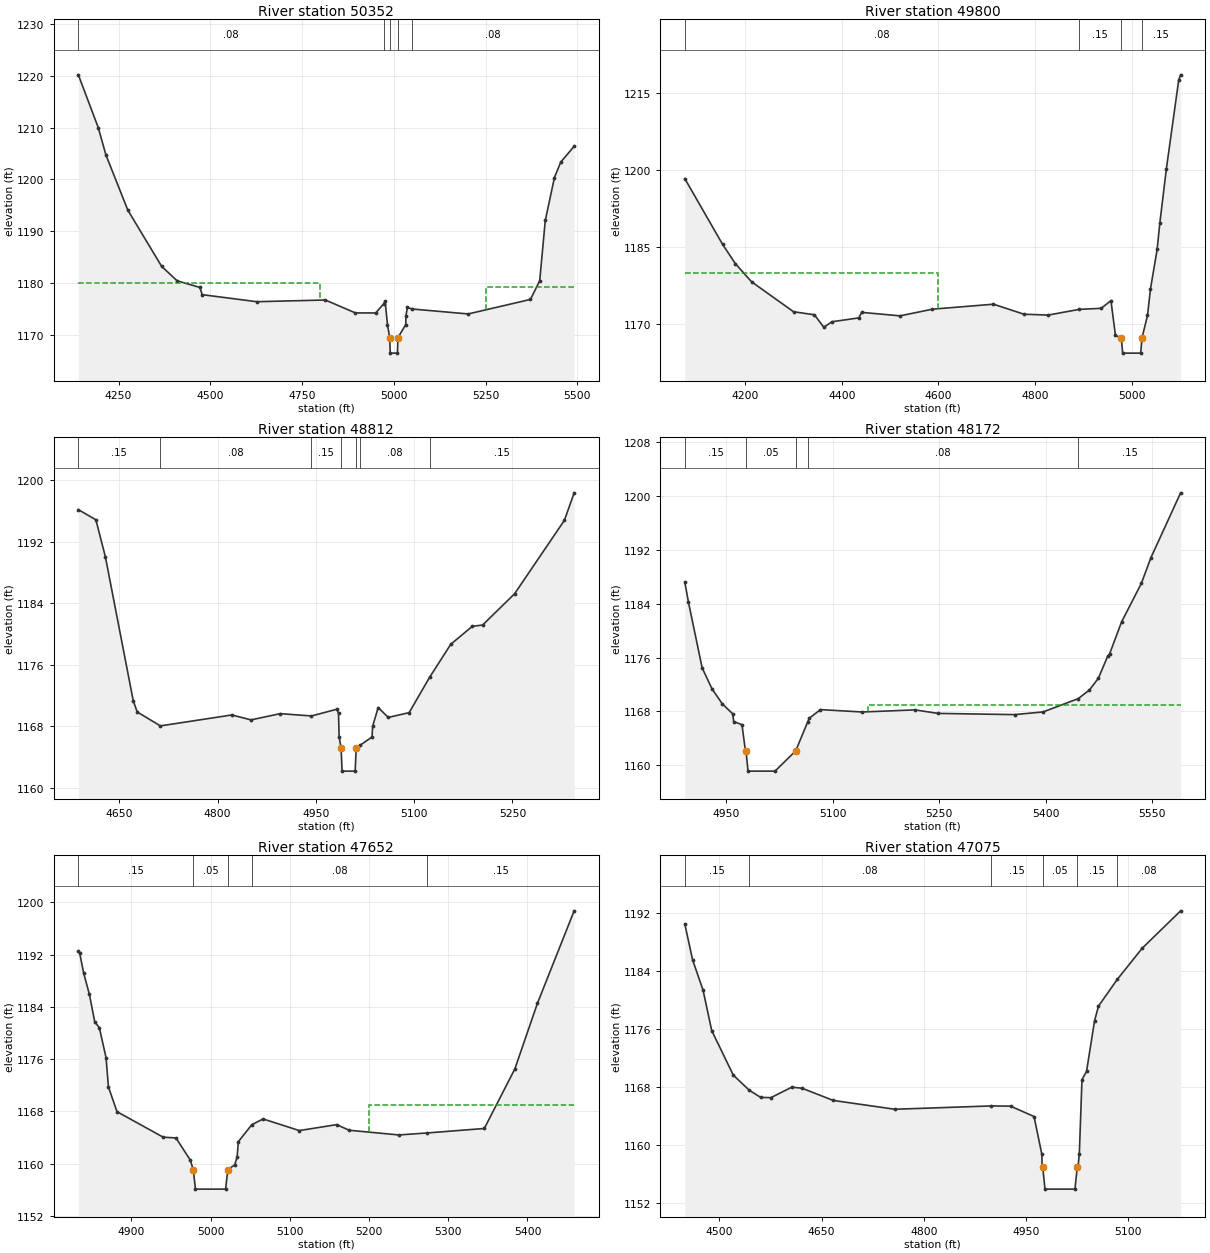
Type RM Length L Ch R = 1,50352,552,552,552
BEGIN DESCRIPTION:
South Fork 168.0
END DESCRIPTION:
XS GIS Cut Line= 3
      1446604.68       956603.29      1445891.83       956235.47
      1445393.80       956004.36
#Sta/Elev= 30
  4140.2 1220.19  4194.5 1210.01  4215.3 1204.75  4275.1 1194.08  4367.2 1183.24
  4409.5 1180.45  4471.5 1179.17  4477.7 1177.78  4626.5 1176.42  4813.2 1176.75
  4895.2 1174.26  4950.5 1174.25  4972.4 1176.01  4976.2 1176.59  4982.7 1171.99
  4988.7 1169.50  4990.2 1166.50  5009.8 1166.50  5011.3 1169.50  5032.4 1172.00
  5033.0 1173.75  5037.2 1175.33  5048.7 1175.02  5202.5 1174.06  5372.3 1176.86
  5397.5 1180.46  5412.7 1192.10  5437.7 1200.37  5454.9 1203.36  5491.4 1206.40
#Mann=5,-1,0
  4140.2    0.08       0  4972.4    0.15       0  4988.7    0.05       0
  5011.3    0.15       0  5048.7    0.08       0
#XS Ineff=2,0
    0.00 4800.00 1180.00 5250.00    0.00 1179.35
Permanent Ineff=
       F       F
Bank Sta=4988.7,5011.3
XS Rating Curve= 0
Exp/Cntr=0.3,0.1

Type RM Length L Ch R = 1,49800,988,988,988
BEGIN DESCRIPTION:
South Fork 166.0
END DESCRIPTION:
XS GIS Cut Line= 3
      1446660.05       956339.63      1445995.67       955695.60
      1445924.38       955623.49
#Sta/Elev= 30
  4074.7 1198.37  4153.0 1185.54  4179.4 1181.79  4212.9 1178.26  4299.9 1172.41
  4343.1 1171.82  4362.6 1169.37  4379.3 1170.46  4434.9 1171.21  4441.1 1172.29
  4520.4 1171.61  4587.6 1172.91  4713.9 1173.88  4776.9 1171.93  4827.2 1171.76
  4891.4 1172.87  4937.0 1173.08  4957.1 1174.58  4966.5 1167.78  4978.5 1167.34
  4981.4 1164.34  5018.6 1164.34  5021.5 1167.34  5032.8 1171.68  5039.0 1176.87
  5052.8 1184.57  5058.3 1189.67  5071.9 1200.30  5097.5 1217.63  5101.4 1218.61
#Mann=4,-1,0
  4074.7    0.08       0  4891.4    0.15       0  4978.5    0.05       0
  5021.5    0.15       0
#XS Ineff=2,0
    0.00 4600.00 1180.00               0
Permanent Ineff=
       F       F
Bank Sta=4978.5,5021.5
XS Rating Curve= 0
Exp/Cntr=0.3,0.1

Type RM Length L Ch R = 1,48812,640,640,640
BEGIN DESCRIPTION:
South Fork 164.0
END DESCRIPTION:
XS GIS Cut Line= 3
      1446686.08       956284.33      1446993.12       955693.63
      1447063.68       955636.53
#Sta/Elev= 30
  4587.6 1196.14  4614.4 1194.82  4628.9 1190.00  4671.4 1171.33  4677.4 1169.88
  4712.8 1168.07  4821.9 1169.49  4851.0 1168.85  4895.7 1169.66  4943.3 1169.36
  4981.9 1170.23  4984.6 1169.69  4985.5 1166.64  4988.5 1165.20  4990.0 1162.20
  5010.0 1162.20  5011.5 1165.20  5017.0 1165.53  5035.7 1166.63  5036.7 1168.04
  5045.1 1170.45  5060.5 1169.17  5092.3 1169.79  5123.5 1174.37  5155.9 1178.67
  5188.8 1181.00  5204.4 1181.16  5253.3 1185.23  5329.2 1194.75  5344.1 1198.32
#Mann=7,-1,0
  4587.6    0.15       0  4712.8    0.08       0  4943.3    0.15       0
  4988.5    0.05       0  5011.5    0.15       0  5017.0    0.08       0
  5123.5    0.15       0
Bank Sta=4988.5,5011.5
XS Rating Curve= 0
Exp/Cntr=0.3,0.1

Type RM Length L Ch R = 1,48172,520,520,520
BEGIN DESCRIPTION:
South Fork 162.0
END DESCRIPTION:
XS GIS Cut Line= 3
      1446949.76       956443.82      1447327.38       955939.25
      1447382.75       955900.16
#Sta/Elev= 30
  4892.0 1187.18  4897.1 1184.23  4916.4 1174.47  4930.3 1171.35  4944.7 1169.14
  4959.4 1167.65  4960.8 1166.50  4972.5 1166.04  4977.3 1162.19  4978.2 1162.15
  4981.0 1159.15  5019.0 1159.15  5048.1 1162.15  5064.8 1166.39  5067.5 1167.02
  5083.0 1168.27  5141.9 1167.92  5216.0 1168.23  5248.7 1167.71  5356.2 1167.53
  5396.4 1167.93  5445.9 1169.90  5461.7 1171.19  5474.3 1172.94  5487.3 1176.19
  5489.9 1176.50  5506.8 1181.26  5534.7 1186.99  5548.2 1190.81  5590.0 1200.42
#Mann=5,-1,0
  4892.0    0.15       0  4978.2    0.05       0  5048.1    0.15       0
  5064.8    0.08       0  5445.9    0.15       0
#XS Ineff=2,0
       0                 5150.00    0.00 1169.00
Permanent Ineff=
       F       F
Bank Sta=4978.2,5048.1
XS Rating Curve= 0
Exp/Cntr=0.3,0.1

Type RM Length L Ch R = 1,47652,577,577,577
BEGIN DESCRIPTION:
South Fork 159.0
END DESCRIPTION:
XS GIS Cut Line= 3
      1447372.95       956674.92      1447457.58       956570.76
      1447779.85       956199.67
#Sta/Elev= 30
  4833.2 1192.57  4835.0 1192.19  4840.0 1189.15  4847.2 1185.91  4853.9 1181.72
  4859.7 1180.82  4868.2 1176.23  4871.2 1171.75  4882.0 1167.97  4940.3 1164.07
  4956.4 1163.95  4974.5 1160.56  4978.2 1159.12  4981.0 1156.12  5019.0 1156.12
  5021.9 1159.12  5030.5 1159.82  5033.6 1161.03  5035.1 1163.38  5052.1 1165.98
  5066.4 1166.86  5112.1 1165.08  5159.1 1165.99  5175.0 1165.13  5237.7 1164.41
  5273.7 1164.72  5345.5 1165.40  5384.0 1174.50  5412.6 1184.57  5458.9 1198.71
#Mann=5,-1,0
  4833.2    0.15       0  4978.2    0.05       0  5021.9    0.15       0
  5052.1    0.08       0  5273.7    0.15       0
#XS Ineff=2,0
       0                 5200.00    0.00 1169.00
Permanent Ineff=
       F       F
Bank Sta=4978.2,5021.9
XS Rating Curve= 0
Exp/Cntr=0.3,0.1

Type RM Length L Ch R = 1,47075,575,575,575
BEGIN DESCRIPTION:
South Fork 157.0
END DESCRIPTION:
XS GIS Cut Line= 3
      1447568.28       956899.51      1447929.59       956482.87
      1448036.99       956342.92
#Sta/Elev= 30
  4449.2 1190.47  4460.7 1185.50  4476.1 1181.30  4488.7 1175.76  4520.4 1169.61
  4544.0 1167.51  4560.6 1166.54  4575.6 1166.50  4606.3 1167.95  4621.4 1167.80
  4667.0 1166.12  4757.6 1164.90  4898.9 1165.36  4927.5 1165.33  4961.9 1163.90
  4973.4 1158.67  4973.7 1156.92  4974.7 1156.88  4978.0 1153.88  5022.0 1153.88
  5025.3 1156.88  5026.4 1156.88  5028.4 1158.76  5032.3 1169.00  5039.0 1170.13
  5050.7 1177.08  5056.5 1179.13  5084.2 1182.83  5120.6 1187.11  5177.1 1192.28
#Mann=6,-1,0
  4449.2    0.15       0  4544.0    0.08       0  4898.9    0.15       0
  4974.7    0.05       0  5025.3    0.15       0  5084.2    0.08       0
Bank Sta=4974.7,5025.3
XS Rating Curve= 0
Exp/Cntr=0.3,0.1

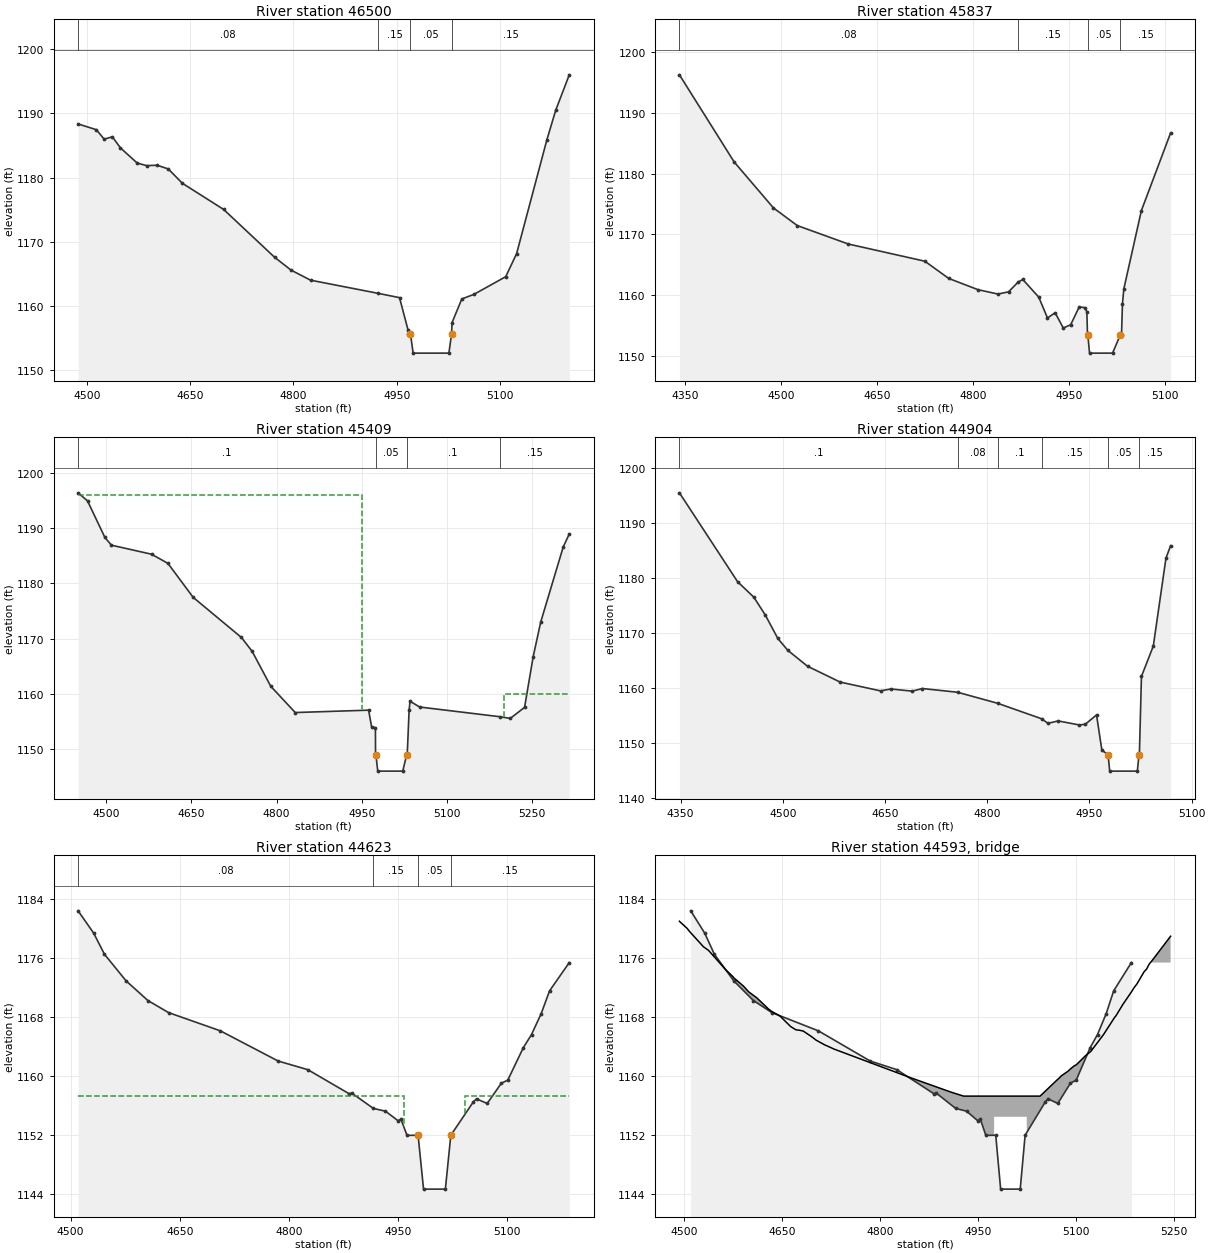
Type RM Length L Ch R = 1,46500,663,663,663
BEGIN DESCRIPTION:
South Fork 155.0
END DESCRIPTION:
XS GIS Cut Line= 3
      1447903.52       957153.47      1448300.71       956828.65
      1448463.48       956710.71
#Sta/Elev= 30
  4486.9 1188.35  4513.5 1187.45  4524.8 1185.98  4536.7 1186.35  4548.5 1184.62
  4572.9 1182.26  4586.4 1181.87  4602.0 1181.92  4618.0 1181.35  4638.5 1179.12
  4698.5 1175.05  4772.5 1167.62  4796.4 1165.62  4824.8 1164.05  4923.6 1161.99
  4954.2 1161.33  4966.7 1156.26  4967.2 1155.75  4970.1 1155.70  4974.0 1152.70
  5026.0 1152.70  5029.9 1155.70  5030.6 1157.45  5044.8 1161.13  5062.2 1161.83
  5108.6 1164.59  5124.4 1168.16  5168.5 1185.90  5181.3 1190.48  5201.0 1195.99
#Mann=4,-1,0
  4486.9    0.08       0  4923.6    0.15       0  4970.1    0.05       0
  5029.9    0.15       0
Bank Sta=4970.1,5029.9
XS Rating Curve= 0
Exp/Cntr=0.3,0.1

Type RM Length L Ch R = 1,45837,428,428,428
BEGIN DESCRIPTION:
South Fork 153.0
END DESCRIPTION:
XS GIS Cut Line= 3
      1448333.27       957521.25      1448860.58       957114.38
      1448941.92       957052.56
#Sta/Elev= 30
  4340.6 1196.28  4426.1 1181.94  4487.5 1174.37  4524.9 1171.45  4604.8 1168.41
  4724.4 1165.58  4761.8 1162.74  4807.3 1160.90  4838.7 1160.17  4855.3 1160.53
  4870.1 1162.12  4877.6 1162.57  4902.6 1159.66  4916.2 1156.23  4928.2 1157.09
  4940.9 1154.58  4952.5 1155.11  4965.8 1158.05  4975.0 1157.93  4977.8 1157.23
  4978.8 1153.51  4979.3 1153.44  4982.0 1150.44  5018.0 1150.44  5030.1 1153.44
  5032.0 1153.44  5033.5 1158.57  5035.7 1161.05  5063.1 1173.92  5108.8 1186.71
#Mann=4,-1,0
  4340.6    0.08       0  4870.1    0.15       0  4979.3    0.05       0
  5030.1    0.15       0
Bank Sta=4979.3,5030.1
XS Rating Curve= 0
Exp/Cntr=0.3,0.1

Type RM Length L Ch R = 1,45409,505,505,505
BEGIN DESCRIPTION:
South Fork 151.0
END DESCRIPTION:
XS GIS Cut Line= 4
      1448538.33       957719.84      1449062.40       957488.73
      1449283.76       957400.84      1449332.56       957378.06
#Sta/Elev= 30
  4450.4 1196.41  4467.0 1194.95  4497.6 1188.32  4509.1 1186.93  4579.8 1185.29
  4608.6 1183.63  4653.0 1177.48  4738.0 1170.21  4756.9 1167.69  4789.6 1161.38
  4832.7 1156.62  4961.9 1157.05  4967.1 1154.08  4973.9 1153.85  4974.1 1149.01
  4974.7 1149.01  4978.0 1146.01  5022.0 1146.01  5029.0 1149.01  5029.9 1149.01
  5033.2 1156.99  5034.8 1158.67  5051.7 1157.62  5192.5 1155.87  5211.4 1155.56
  5236.5 1157.56  5251.7 1166.75  5264.9 1173.00  5304.6 1186.62  5315.2 1188.96
#Mann=4,-1,0
  4450.4     0.1       0  4974.7    0.05       0  5029.0     0.1       0
  5192.5    0.15       0
#XS Ineff=2,0
    0.00 4950.00 1196.00 5200.00    0.00 1160.00
Permanent Ineff=
       F       F
Bank Sta=4974.7,5029
XS Rating Curve= 0
Exp/Cntr=0.3,0.1

Type RM Length L Ch R = 1,44904,281,281,281
BEGIN DESCRIPTION:
South Fork 149.0
END DESCRIPTION:
XS GIS Cut Line= 5
      1449273.99       958201.65      1449293.52       957892.37
      1449414.65       957681.18      1449420.48       957671.02
      1449495.33       957534.34
#Sta/Elev= 30
  4348.2 1195.54  4433.5 1179.39  4457.5 1176.55  4474.5 1173.26  4492.6 1169.06
  4507.2 1166.91  4536.2 1164.01  4584.1 1161.13  4643.4 1159.53  4658.4 1159.88
  4689.9 1159.48  4704.7 1159.96  4756.4 1159.28  4815.4 1157.27  4880.0 1154.45
  4889.1 1153.62  4904.0 1154.07  4935.3 1153.33  4944.0 1153.47  4960.4 1155.16
  4968.2 1148.75  4977.3 1147.94  4979.7 1144.94  5020.3 1144.94  5022.7 1147.94
  5023.3 1148.08  5026.3 1162.16  5043.7 1167.68  5062.3 1183.68  5069.1 1185.93
#Mann=6,-1,0
  4348.2     0.1       0  4756.4    0.08       0  4815.4     0.1       0
  4880.0    0.15       0  4977.3    0.05       0  5022.7    0.15       0
Bank Sta=4977.3,5022.7
XS Rating Curve= 0
Exp/Cntr=0.5,0.3

Type RM Length L Ch R = 1,44623,58,58,58
BEGIN DESCRIPTION:
Golden Rd US
END DESCRIPTION:
XS GIS Cut Line= 4
      1449456.27       958230.93      1449635.33       957889.21
      1449669.24       957730.95      1449622.31       957612.45
#Sta/Elev= 30
  4510.2 1182.40  4531.6 1179.38  4546.4 1176.52  4576.1 1172.92  4606.1 1170.25
  4634.6 1168.61  4705.8 1166.14  4785.2 1162.05  4826.0 1160.88  4882.9 1157.61
  4886.1 1157.73  4916.1 1155.63  4932.7 1155.26  4950.0 1153.96  4953.9 1154.18
  4962.3 1151.98  4977.5 1152.00  4985.0 1144.70  5015.0 1144.70  5022.5 1152.00
  5053.4 1156.51  5057.8 1156.93  5072.5 1156.30  5091.9 1159.04  5100.8 1159.47
  5122.2 1163.87  5133.4 1165.64  5146.7 1168.47  5158.2 1171.56  5185.3 1175.39
#Mann=4,-1,0
  4510.2    0.08       0  4916.1    0.15       0  4977.5    0.05       0
  5022.5    0.15       0
#XS Ineff=2,0
    0.00 4958.00 1157.30 5042.00    0.00 1157.30
Permanent Ineff=
       F       F
Bank Sta=4977.5,5022.5
XS Rating Curve= 0
Exp/Cntr=0.5,0.3

Type RM Length L Ch R =3,44593,,,
BEGIN DESCRIPTION:
Golden Rd TOR
Structure ID: LDS_SFMR_04
Approximate Survey Structure
END DESCRIPTION:
Bridge Culvert--1,0,-1,-1,0
Deck Dist Width WeirC Skew NumUp NumDn MinLoCord MaxHiCord MaxSubmerge Is_Ogee
17,26,3,,56,56,,,0.95,0,1,1,,,
  4492.9  4493.2  4504.7  4508.3  4529.7  4537.5  4563.6  4575.1  4576.8  4579.2
  4590.8  4599.1  4611.2  4629.9  4635.1  4645.0  4647.5  4663.3  4671.3  4676.4
  4682.6  4695.4  4702.3  4716.7  4717.4  4729.8  4846.4  4909.9  4928.3  4975.0
  4975.0  5025.0  5025.0  5045.4  5072.9  5075.2  5077.5  5088.0  5092.0  5097.9
  5101.0  5115.1  5123.1  5142.5  5159.5  5161.4  5170.9  5171.1  5185.6  5189.5
  5193.7  5204.9  5208.7  5212.4  5217.6  5245.4
 1180.99 1180.95 1180.02 1179.61 1177.53 1177.04 1174.44 1173.46 1173.26 1173.10
 1172.22 1171.42 1170.63 1169.05 1168.72 1168.25 1168.10 1166.72 1166.28 1166.23
 1166.11 1165.35 1164.88 1164.18 1164.17 1163.67 1159.81 1157.81 1157.30 1157.30
 1157.30 1157.30 1157.30 1157.30 1159.61 1159.78 1160.02 1160.66 1160.99 1161.41
 1161.55 1162.78 1163.35 1165.62 1167.95 1168.14 1169.52 1169.57 1171.45 1172.00
 1172.48 1174.16 1174.52 1175.16 1175.73 1178.96
 1124.70 1124.70 1124.70 1124.70 1124.70 1124.70 1124.70 1124.70 1124.70 1124.70
 1124.70 1124.70 1124.70 1124.70 1124.70 1124.70 1124.70 1124.70 1124.70 1124.70
 1124.70 1124.70 1124.70 1124.70 1124.70 1124.70 1124.70 1124.70 1124.70 1124.70
 1154.50 1154.50 1124.70 1124.70 1124.70 1124.70 1124.70 1124.70 1124.70 1124.70
 1124.70 1124.70 1124.70 1124.70 1124.70 1124.70 1124.70 1124.70 1124.70 1124.70
 1124.70 1124.70 1124.70 1124.70 1124.70 1124.70
  4492.9  4493.2  4504.7  4508.3  4529.7  4537.5  4563.6  4575.1  4576.8  4579.2
  4590.8  4599.1  4611.2  4629.9  4635.1  4645.0  4647.5  4663.3  4671.3  4676.4
  4682.6  4695.4  4702.3  4716.7  4717.4  4729.8  4846.4  4909.9  4928.3  4975.0
  4975.0  5025.0  5025.0  5045.4  5072.9  5075.2  5077.5  5088.0  5092.0  5097.9
  5101.0  5115.1  5123.1  5142.5  5159.5  5161.4  5170.9  5171.1  5185.6  5189.5
  5193.7  5204.9  5208.7  5212.4  5217.6  5245.4
 1180.99 1180.95 1180.02 1179.61 1177.53 1177.04 1174.44 1173.46 1173.26 1173.10
 1172.22 1171.42 1170.63 1169.05 1168.72 1168.25 1168.10 1166.72 1166.28 1166.23
 1166.11 1165.35 1164.88 1164.18 1164.17 1163.67 1159.81 1157.81 1157.30 1157.30
 1157.30 1157.30 1157.30 1157.30 1159.61 1159.78 1160.02 1160.66 1160.99 1161.41
 1161.55 1162.78 1163.35 1165.62 1167.95 1168.14 1169.52 1169.57 1171.45 1172.00
 1172.48 1174.16 1174.52 1175.16 1175.73 1178.96
 1124.70 1124.70 1124.70 1124.70 1124.70 1124.70 1124.70 1124.70 1124.70 1124.70
 1124.70 1124.70 1124.70 1124.70 1124.70 1124.70 1124.70 1124.70 1124.70 1124.70
 1124.70 1124.70 1124.70 1124.70 1124.70 1124.70 1124.70 1124.70 1124.70 1124.70
 1154.50 1154.50 1124.70 1124.70 1124.70 1124.70 1124.70 1124.70 1124.70 1124.70
 1124.70 1124.70 1124.70 1124.70 1124.70 1124.70 1124.70 1124.70 1124.70 1124.70
 1124.70 1124.70 1124.70 1124.70 1124.70 1124.70
Abutment Skew #Up #Dn=,2,2
  4975.0  4976.0
 1154.50 1153.98
  4975.0  4976.0
 1154.50 1147.22
Abutment Skew #Up #Dn=,2,2
  5024.0  5025.0
 1153.40 1154.50
  5024.0  5025.0
 1152.79 1154.50
BR Coef=1,1,0,1.25,0,,,0.8,0,2,0,
WSPro=,,,, 1 ,,,, 0 ,,,, 0 ,,,,-1 ,-1 ,-1 , 0 , 0 , 0 , 0 , 0
BC Design=,,0,,0,,,,,,