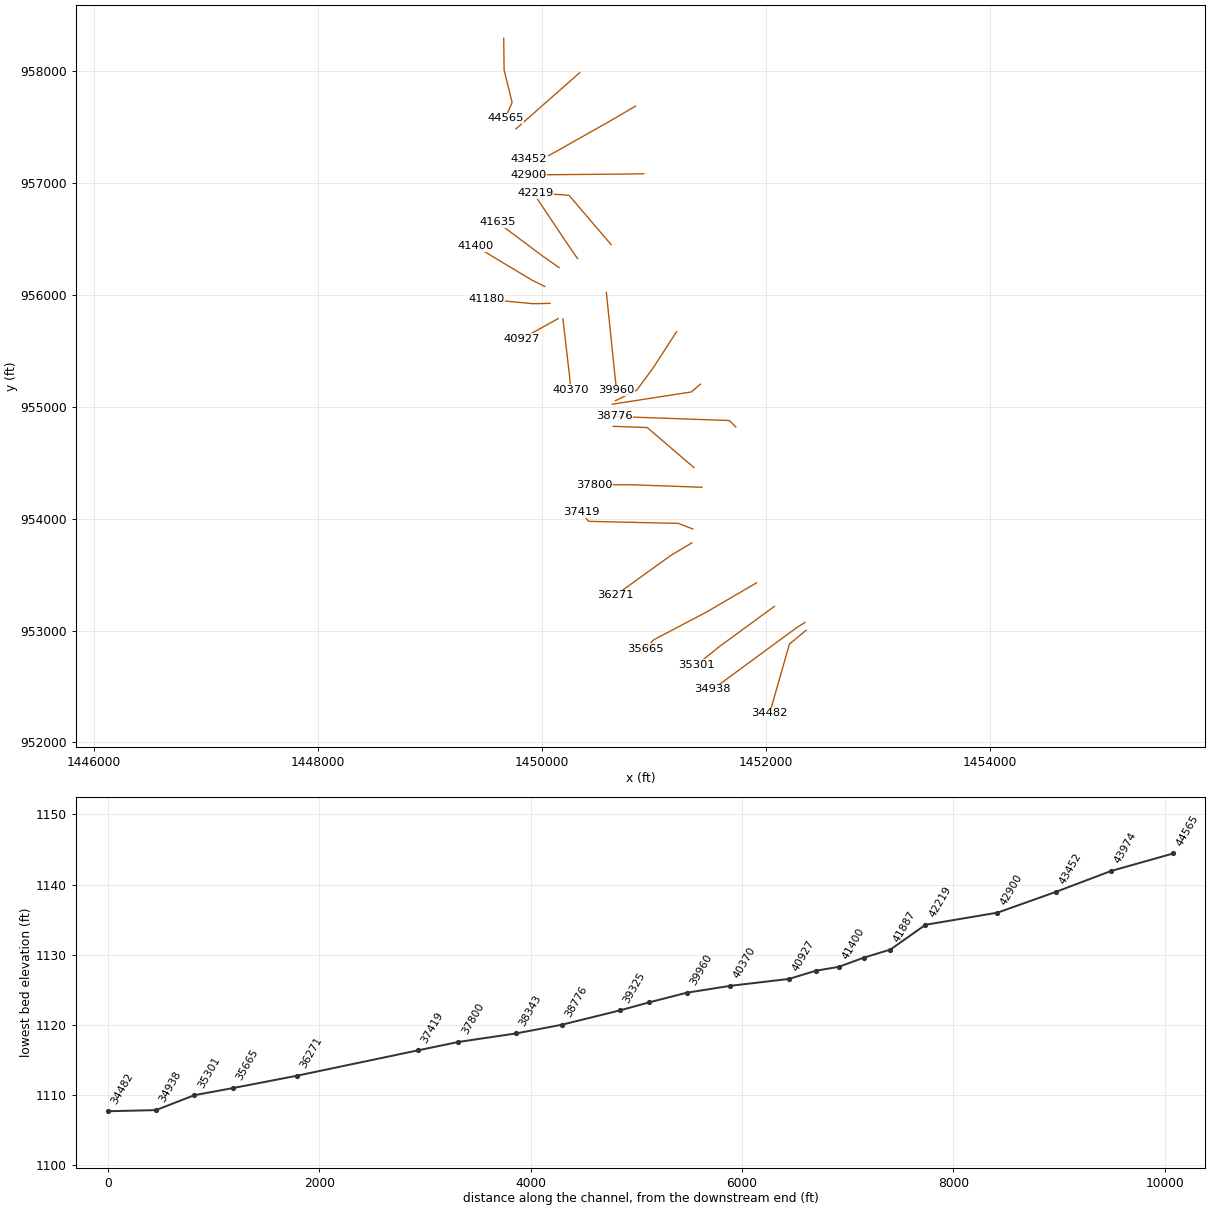
HEC-RAS study South Fork.prj: South Fork Limited Detail Study

--- South Fork.g01 (geometry) --- (continued)

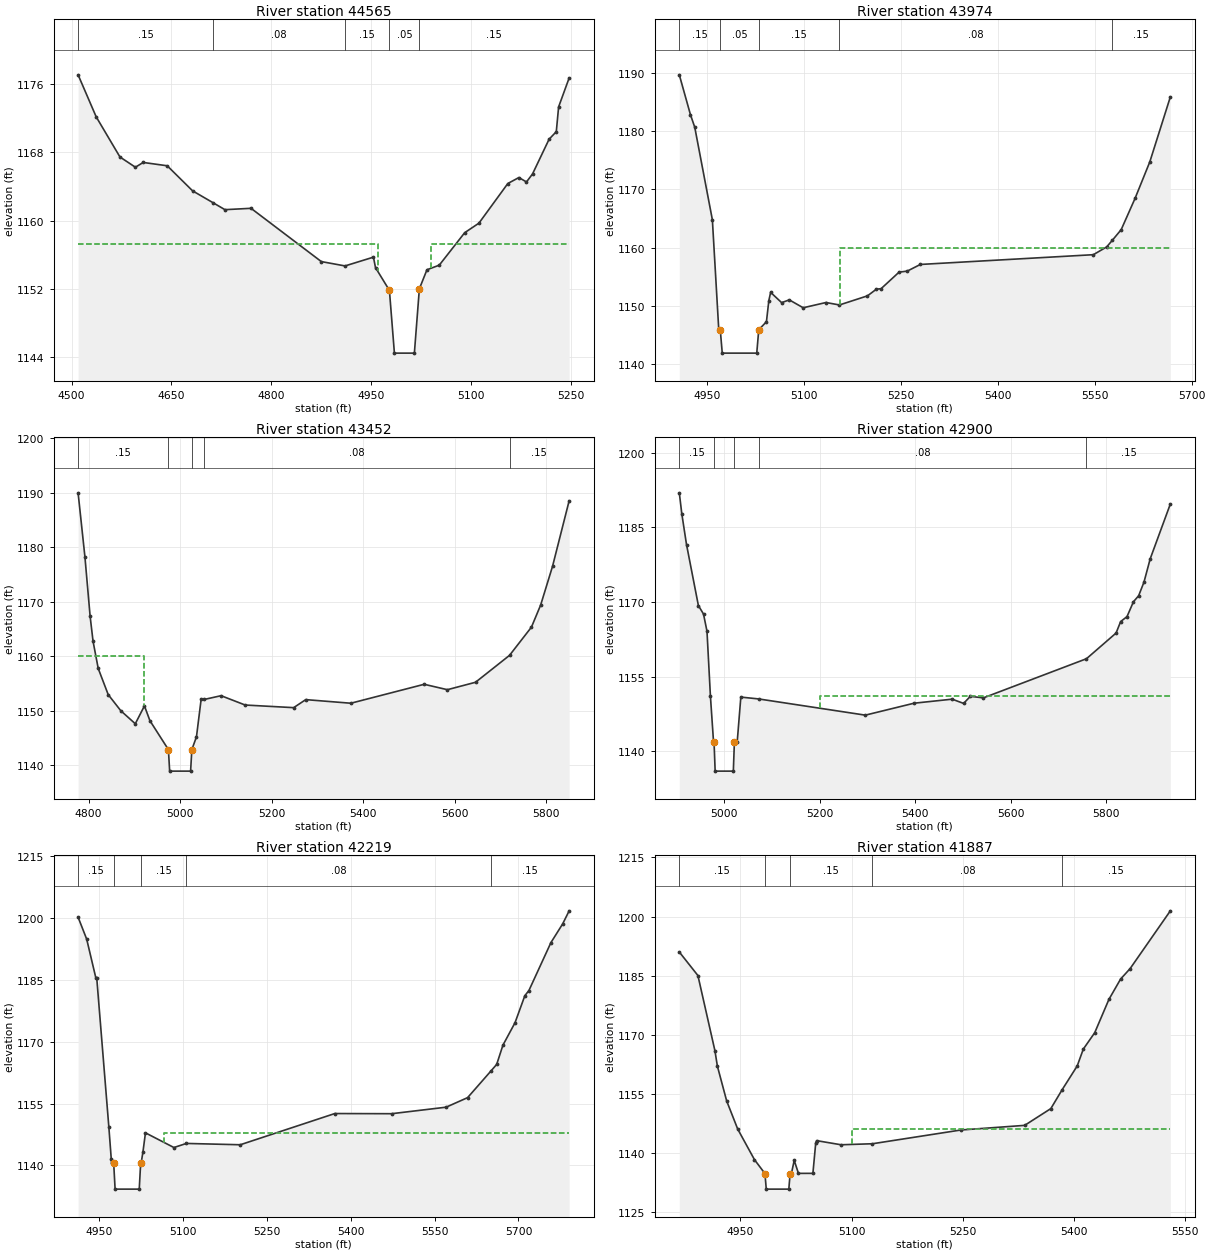
Type RM Length L Ch R = 1,44565,591,591,591
BEGIN DESCRIPTION:
Golden Rd DS
END DESCRIPTION:
XS GIS Cut Line= 4
      1449658.10       958292.80      1449661.36       958009.56
      1449732.98       957719.85      1449671.13       957576.63
#Sta/Elev= 30
  4509.8 1177.10  4537.0 1172.17  4572.7 1167.46  4595.9 1166.26  4607.6 1166.82
  4643.7 1166.43  4681.8 1163.49  4713.1 1162.07  4730.4 1161.28  4769.6 1161.44
  4875.2 1155.19  4910.8 1154.68  4953.5 1155.71  4956.6 1154.48  4977.5 1151.81
  4985.0 1144.45  5015.0 1144.45  5022.5 1152.00  5033.9 1154.23  5052.4 1154.77
  5090.6 1158.58  5112.0 1159.70  5155.4 1164.35  5172.0 1165.05  5183.4 1164.53
  5192.5 1165.47  5217.4 1169.55  5228.2 1170.43  5231.7 1173.34  5247.5 1176.73
#Mann=5,-1,0
  4509.8    0.15       0  4713.1    0.08       0  4910.8    0.15       0
  4977.5    0.05       0  5022.5    0.15       0
#XS Ineff=2,0
    0.00 4960.00 1157.30 5040.00    0.00 1157.30
Permanent Ineff=
       F       F
Bank Sta=4977.5,5022.5
XS Rating Curve= 0
Exp/Cntr=0.5,0.3

Type RM Length L Ch R = 1,43974,522,522,522
BEGIN DESCRIPTION:
South Fork 147.0
END DESCRIPTION:
XS GIS Cut Line= 3
      1450337.50       957986.48      1450251.53       957910.93
      1449767.17       957483.86
#Sta/Elev= 30
  4906.8 1189.61  4924.1 1182.77  4930.7 1180.64  4958.0 1164.78  4967.9 1145.94
  4970.2 1145.94  4973.3 1141.94  5026.7 1141.94  5029.8 1145.94  5041.7 1147.32
  5045.4 1150.93  5048.2 1152.35  5065.2 1150.59  5077.1 1151.06  5098.6 1149.71
  5133.9 1150.61  5154.7 1150.19  5198.1 1151.75  5212.0 1152.90  5219.1 1152.97
  5247.0 1155.81  5259.7 1155.99  5280.0 1157.13  5547.8 1158.80  5568.5 1160.14
  5577.2 1161.27  5590.9 1163.09  5612.3 1168.43  5635.2 1174.70  5667.0 1185.83
#Mann=5,-1,0
  4906.8    0.15       0  4970.2    0.05       0  5029.8    0.15       0
  5154.7    0.08       0  5577.2    0.15       0
#XS Ineff=2,0
       0                 5155.00    0.00 1160.00
Permanent Ineff=
       F       F
Bank Sta=4970.2,5029.8
XS Rating Curve= 0
Exp/Cntr=0.3,0.1

Type RM Length L Ch R = 1,43452,552,552,552
BEGIN DESCRIPTION:
South Fork 145.0
END DESCRIPTION:
XS GIS Cut Line= 4
      1450834.90       957686.99      1450644.76       957574.99
      1450063.31       957246.14      1449881.78       957213.02
#Sta/Elev= 30
  4777.0 1189.95  4791.9 1178.25  4803.3 1167.32  4809.7 1162.75  4821.0 1157.77
  4842.8 1152.98  4870.4 1150.02  4902.0 1147.64  4922.0 1150.91  4934.0 1148.20
  4974.4 1142.90  4977.1 1138.96  5022.9 1138.96  5025.6 1142.90  5035.7 1145.24
  5045.9 1152.10  5053.1 1152.10  5089.5 1152.78  5142.2 1151.07  5248.1 1150.59
  5274.6 1152.06  5373.1 1151.40  5533.4 1154.87  5584.1 1153.88  5645.6 1155.24
  5719.9 1160.17  5767.8 1165.34  5787.9 1169.38  5813.9 1176.48  5850.2 1188.49
#Mann=5,-1,0
  4777.0    0.15       0  4974.4    0.05       0  5025.6    0.15       0
  5053.1    0.08       0  5719.9    0.15       0
#XS Ineff=2,0
    0.00 4922.00 1160.00               0
Permanent Ineff=
       F       F
Bank Sta=4974.4,5025.6
XS Rating Curve= 0
Exp/Cntr=0.3,0.1

Type RM Length L Ch R = 1,42900,681,681,681
BEGIN DESCRIPTION:
South Fork 143.0
END DESCRIPTION:
XS GIS Cut Line= 3
      1450907.76       957082.80      1450813.69       957080.35
      1449879.12       957072.39
#Sta/Elev= 30
  4905.9 1191.93  4911.2 1187.68  4921.0 1181.54  4945.9 1169.27  4956.6 1167.57
  4963.9 1164.12  4971.1 1151.06  4977.6 1141.90  4978.7 1141.81  4981.0 1136.00
  5019.1 1136.00  5021.3 1141.81  5027.2 1141.86  5034.8 1150.88  5072.0 1150.51
  5295.6 1147.25  5397.7 1149.65  5477.5 1150.46  5501.5 1149.61  5515.6 1151.03
  5542.9 1150.72  5758.9 1158.59  5820.9 1163.75  5830.5 1166.06  5843.8 1167.05
  5857.3 1170.04  5868.2 1171.25  5879.4 1174.00  5892.4 1178.67  5934.6 1189.69
#Mann=5,-1,0
  4905.9    0.15       0  4978.7    0.05       0  5021.3    0.15       0
  5072.0    0.08       0  5758.9    0.15       0
#XS Ineff=2,0
       0                 5200.00    0.00 1151.00
Permanent Ineff=
       F       F
Bank Sta=4978.7,5021.3
XS Rating Curve= 0
Exp/Cntr=0.3,0.1

Type RM Length L Ch R = 1,42219,332,332,332
BEGIN DESCRIPTION:
South Fork 141.0
END DESCRIPTION:
XS GIS Cut Line= 3
      1450616.14       956449.96      1450241.11       956890.09
      1449941.67       956910.93
#Sta/Elev= 30
  4912.2 1200.22  4927.6 1194.88  4944.0 1185.47  4945.5 1185.58  4967.2 1149.35
  4971.5 1141.63  4972.3 1140.56  4975.9 1140.52  4978.4 1134.27  5021.6 1134.27
  5024.1 1140.52  5024.9 1140.47  5028.3 1143.38  5032.7 1147.92  5083.6 1144.36
  5106.0 1145.35  5202.3 1145.03  5371.4 1152.60  5473.0 1152.56  5570.5 1154.14
  5609.0 1156.46  5650.8 1162.93  5661.0 1164.52  5672.2 1169.19  5693.8 1174.63
  5711.4 1181.19  5718.6 1182.42  5758.0 1194.05  5779.1 1198.61  5790.6 1201.76
#Mann=5,-1,0
  4912.2    0.15       0  4975.9    0.05       0  5024.1    0.15       0
  5106.0    0.08       0  5650.8    0.15       0
#XS Ineff=2,0
       0                 5066.60    0.00 1148.00
Permanent Ineff=
       F       F
Bank Sta=4975.9,5024.1
XS Rating Curve= 0
Exp/Cntr=0.3,0.1

Type RM Length L Ch R = 1,41887,252,252,252
BEGIN DESCRIPTION:
South Fork 140.0
END DESCRIPTION:
XS GIS Cut Line= 3
      1450316.63       956325.00      1450225.49       956457.80
      1449946.85       956874.45
#Sta/Elev= 30
  4867.5 1190.99  4892.6 1185.01  4915.5 1165.95  4918.9 1161.96  4931.4 1153.14
  4946.3 1145.99  4968.9 1138.22  4983.0 1134.70  4984.8 1130.74  5015.2 1130.74
  5017.0 1134.70  5018.8 1134.78  5022.5 1138.04  5028.2 1134.74  5047.7 1134.75
  5051.5 1142.45  5052.7 1143.06  5085.7 1142.01  5128.0 1142.27  5247.2 1145.76
  5333.3 1146.94  5368.6 1151.20  5384.0 1156.04  5404.2 1162.04  5412.4 1166.32
  5427.8 1170.48  5446.9 1178.93  5462.7 1184.12  5475.5 1186.76  5529.8 1201.45
#Mann=5,-1,0
  4867.5    0.15       0  4983.0    0.05       0  5017.0    0.15       0
  5128.0    0.08       0  5384.0    0.15       0
#XS Ineff=2,0
       0                 5100.00    0.00 1146.00
Permanent Ineff=
       F       F
Bank Sta=4983,5017
XS Rating Curve= 0
Exp/Cntr=0.3,0.1

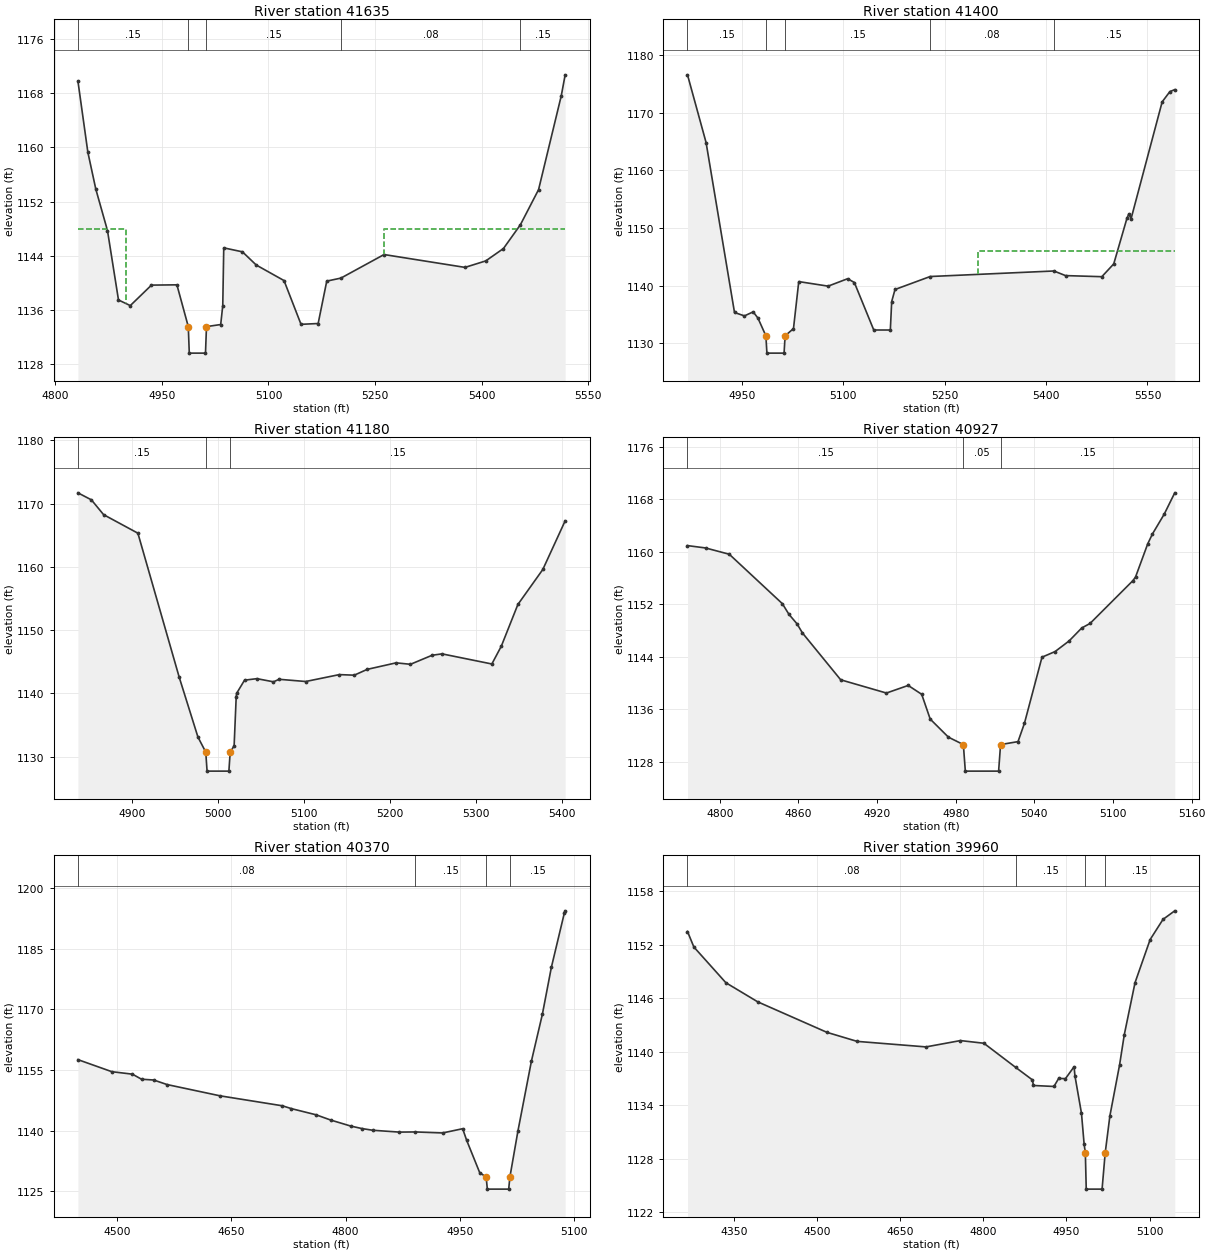
Type RM Length L Ch R = 1,41635,235,235,235
BEGIN DESCRIPTION:
South Fork 139.0
END DESCRIPTION:
XS GIS Cut Line= 3
      1450152.58       956244.26      1450006.74       956345.82
      1449600.52       956650.49
#Sta/Elev= 30
  4831.9 1169.83  4845.9 1159.29  4857.1 1153.83  4873.5 1147.71  4889.0 1137.44
  4905.6 1136.61  4935.4 1139.64  4971.2 1139.68  4987.2 1133.50  4988.6 1129.58
  5011.4 1129.58  5012.8 1133.50  5032.8 1133.81  5035.7 1136.62  5037.1 1145.15
  5063.4 1144.56  5082.8 1142.61  5121.9 1140.31  5145.8 1133.84  5169.9 1133.96
  5182.0 1140.23  5202.0 1140.68  5262.6 1144.16  5376.5 1142.26  5405.7 1143.22
  5430.6 1145.05  5454.4 1148.56  5480.0 1153.76  5512.0 1167.67  5517.4 1170.74
#Mann=5,-1,0
  4831.9    0.15       0  4987.2    0.05       0  5012.8    0.15       0
  5202.0    0.08       0  5454.4    0.15       0
#XS Ineff=2,0
    0.00 4900.00 1148.00 5262.00    0.00 1148.00
Permanent Ineff=
       F       F
Bank Sta=4987.2,5012.8
XS Rating Curve= 0
Exp/Cntr=0.3,0.1

Type RM Length L Ch R = 1,41400,220,220,220
BEGIN DESCRIPTION:
South Fork 138.0
END DESCRIPTION:
XS GIS Cut Line= 3
      1450025.00       956075.00      1449908.42       956132.76
      1449402.55       956436.98
#Sta/Elev= 30
  4869.9 1176.56  4897.4 1164.80  4939.4 1135.33  4954.1 1134.74  4967.0 1135.44
  4974.1 1134.35  4985.8 1131.28  4987.3 1128.28  5012.7 1128.28  5014.2 1131.28
  5026.6 1132.54  5034.4 1140.69  5077.8 1139.90  5106.7 1141.19  5116.6 1140.53
  5145.3 1132.29  5169.8 1132.29  5171.8 1137.23  5176.7 1139.32  5228.7 1141.57
  5411.6 1142.53  5428.8 1141.73  5482.5 1141.54  5500.1 1143.76  5519.6 1151.66
  5522.5 1152.44  5525.7 1151.58  5571.7 1171.87  5583.1 1173.65  5590.3 1173.99
#Mann=5,-1,0
  4869.9    0.15       0  4985.8    0.05       0  5014.2    0.15       0
  5228.7    0.08       0  5411.6    0.15       0
#XS Ineff=2,0
       0                 5300.00    0.00 1146.00
Permanent Ineff=
       F       F
Bank Sta=4985.8,5014.2
XS Rating Curve= 0
Exp/Cntr=0.3,0.1

Type RM Length L Ch R = 1,41180,253,253,253
BEGIN DESCRIPTION:
South Fork 137.0
END DESCRIPTION:
XS GIS Cut Line= 3
      1450071.86       955923.95      1449918.20       955921.34
      1449506.73       955960.41
#Sta/Elev= 30
  4837.0 1171.71  4852.7 1170.60  4866.9 1168.26  4906.8 1165.33  4954.9 1142.55
  4976.7 1133.09  4985.8 1130.71  4987.3 1127.71  5012.7 1127.71  5014.2 1130.71
  5018.8 1131.72  5021.2 1139.44  5021.7 1140.01  5030.9 1142.09  5045.3 1142.33
  5064.6 1141.83  5071.1 1142.23  5102.1 1141.88  5141.2 1142.97  5158.6 1142.88
  5173.7 1143.80  5207.3 1144.83  5224.0 1144.60  5249.2 1146.03  5260.7 1146.25
  5318.7 1144.65  5329.7 1147.46  5349.0 1154.06  5378.0 1159.59  5404.0 1167.28
#Mann=3,-1,0
  4837.0    0.15       0  4985.8    0.05       0  5014.2    0.15       0
Bank Sta=4985.8,5014.2
XS Rating Curve= 0
Exp/Cntr=0.3,0.1

Type RM Length L Ch R = 1,40927,557,557,557
BEGIN DESCRIPTION:
South Fork 136.0
END DESCRIPTION:
XS GIS Cut Line= 3
      1450144.74       955788.52      1449957.26       955684.37
      1449819.24       955608.85
#Sta/Elev= 30
  4775.3 1160.95  4789.1 1160.59  4807.2 1159.63  4847.7 1152.09  4852.7 1150.47
  4858.9 1149.01  4863.0 1147.63  4892.2 1140.48  4927.1 1138.46  4943.7 1139.62
  4954.0 1138.27  4960.5 1134.49  4974.4 1131.73  4985.8 1130.60  4987.3 1126.55
  5012.7 1126.55  5014.2 1130.60  5027.5 1131.05  5032.4 1133.84  5045.8 1143.93
  5055.8 1144.79  5066.5 1146.41  5076.1 1148.38  5082.5 1149.08  5115.2 1155.61
  5117.2 1156.17  5126.5 1161.23  5130.1 1162.73  5139.1 1165.76  5147.1 1169.00
#Mann=3,-1,0
  4775.3    0.15       0  4985.8    0.05       0  5014.2    0.15       0
Bank Sta=4985.8,5014.2
XS Rating Curve= 0
Exp/Cntr=0.3,0.1

Type RM Length L Ch R = 1,40370,410,410,410
BEGIN DESCRIPTION:
South Fork 135.0
END DESCRIPTION:
XS GIS Cut Line= 3
      1450186.42       955785.96      1450246.32       955270.30
      1450256.74       955150.48
#Sta/Elev= 30
  4448.7 1157.56  4493.2 1154.58  4520.2 1153.97  4532.2 1152.72  4548.2 1152.52
  4565.7 1151.40  4635.4 1148.61  4717.1 1146.15  4728.7 1145.46  4761.2 1143.93
  4780.3 1142.64  4806.6 1141.15  4821.1 1140.54  4835.4 1140.11  4870.5 1139.65
  4891.6 1139.69  4927.3 1139.44  4953.6 1140.49  4958.8 1137.65  4976.0 1129.62
  4984.4 1128.56  4986.0 1125.56  5014.0 1125.56  5015.6 1128.56  5026.1 1139.89
  5043.9 1157.25  5058.2 1168.76  5070.0 1180.36  5087.1 1193.84  5088.1 1194.33
#Mann=4,-1,0
  4448.7    0.08       0  4891.6    0.15       0  4984.4    0.05       0
  5015.6    0.15       0
Bank Sta=4984.4,5015.6
XS Rating Curve= 0
Exp/Cntr=0.3,0.1

Type RM Length L Ch R = 1,39960,360,360,360
BEGIN DESCRIPTION:
South Fork 133.0
END DESCRIPTION:
XS GIS Cut Line= 3
      1450574.45       956022.86      1450649.97       955291.14
      1450665.59       955147.90
#Sta/Elev= 30
  4265.8 1153.49  4277.3 1151.75  4335.1 1147.74  4392.5 1145.60  4517.7 1142.17
  4572.0 1141.16  4696.4 1140.54  4758.6 1141.25  4800.9 1140.95  4858.1 1138.25
  4888.5 1136.84  4890.4 1136.21  4927.4 1136.10  4935.9 1137.00  4948.2 1136.98
  4963.8 1138.32  4965.3 1137.29  4977.1 1133.09  4981.8 1129.69  4984.1 1128.63
  4985.7 1124.58  5014.3 1124.58  5019.9 1128.63  5028.4 1132.80  5045.9 1138.52
  5054.4 1141.91  5073.8 1147.75  5101.1 1152.59  5124.3 1154.85  5145.5 1155.81
#Mann=4,-1,0
  4265.8    0.08       0  4858.1    0.15       0  4984.1    0.05       0
  5019.9    0.15       0
Bank Sta=4984.1,5019.9
XS Rating Curve= 0
Exp/Cntr=0.3,0.1

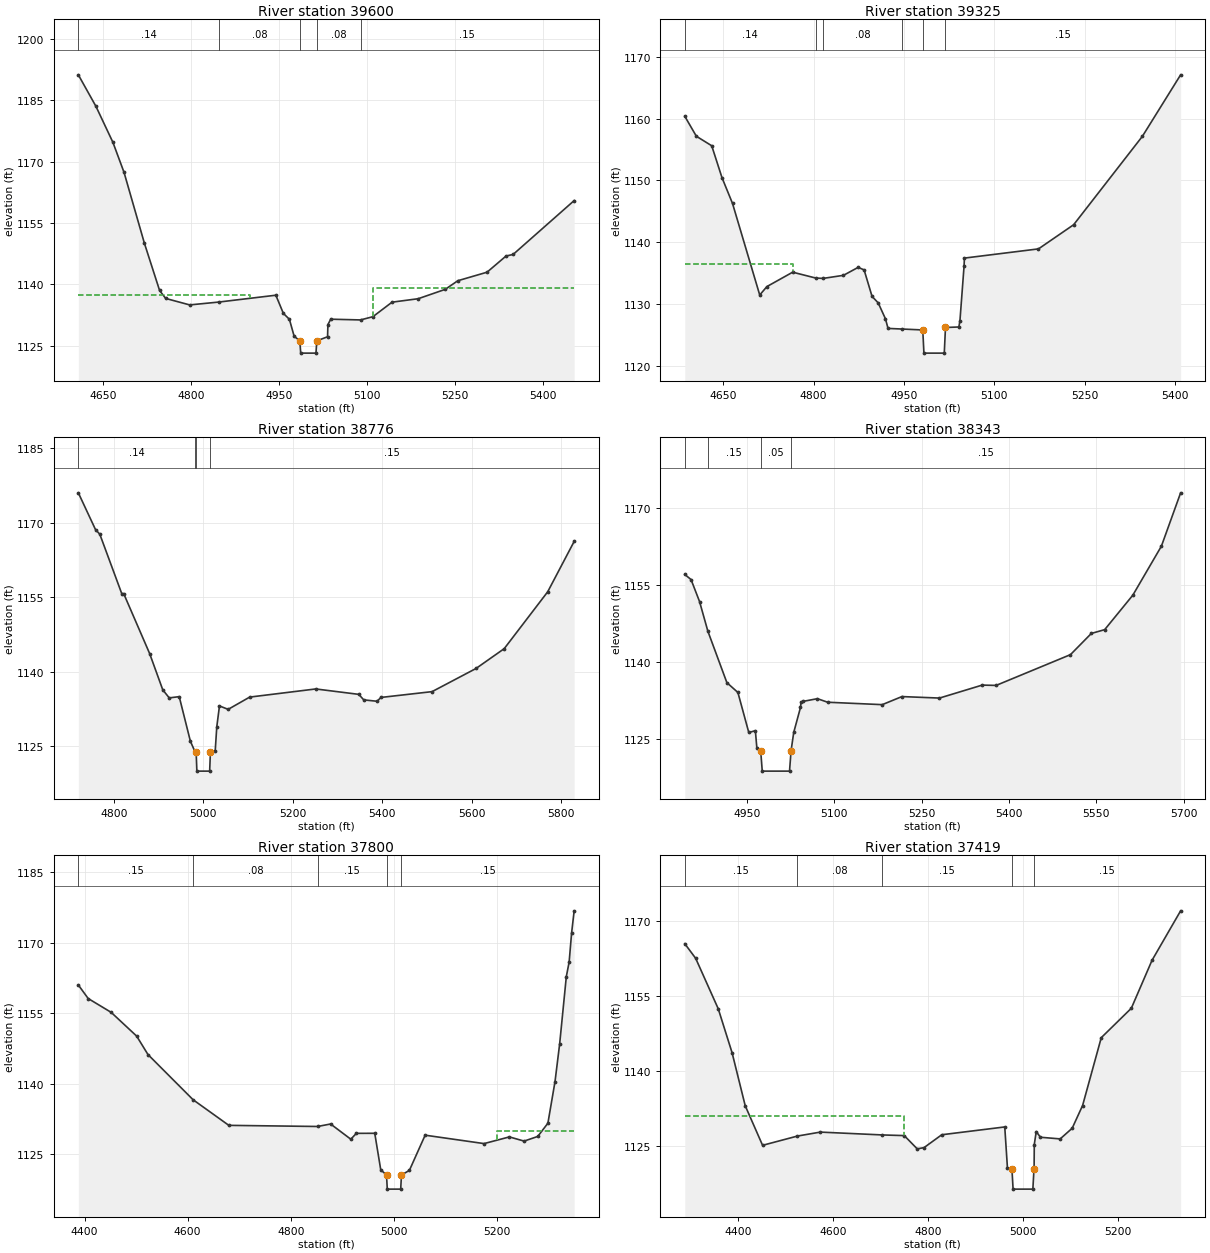
Type RM Length L Ch R = 1,39600,275,275,275
BEGIN DESCRIPTION:
South Fork 132.0
END DESCRIPTION:
XS GIS Cut Line= 4
      1451202.05       955671.34      1450988.74       955342.11
      1450845.28       955147.91      1450655.18       955054.16
#Sta/Elev= 30
  4607.7 1191.18  4637.8 1183.46  4666.7 1174.68  4685.7 1167.33  4720.4 1150.03
  4746.3 1138.50  4756.7 1136.55  4797.6 1134.97  4847.5 1135.67  4944.6 1137.34
  4957.4 1132.90  4967.7 1131.46  4975.8 1127.32  4985.5 1126.19  4987.0 1123.19
  5013.0 1123.19  5014.5 1126.19  5032.8 1127.19  5033.4 1130.16  5038.2 1131.48
  5089.0 1131.30  5110.1 1132.09  5142.8 1135.64  5187.3 1136.48  5233.5 1138.77
  5255.0 1140.88  5304.8 1142.96  5337.2 1146.91  5349.3 1147.30  5453.4 1160.46
#Mann=5,-1,0
  4607.7    0.14       0  4847.5    0.08       0  4985.5    0.05       0
  5014.5    0.08       0  5089.0    0.15       0
#XS Ineff=2,0
    0.00 4900.00 1137.50 5110.00    0.00 1139.00
Permanent Ineff=
       F       F
Bank Sta=4985.5,5014.5
XS Rating Curve= 0
Exp/Cntr=0.3,0.1

Type RM Length L Ch R = 1,39325,549,549,549
BEGIN DESCRIPTION:
South Fork 131.0
END DESCRIPTION:
XS GIS Cut Line= 3
      1451415.61       955202.61      1451332.26       955132.28
      1450626.54       955022.91
#Sta/Elev= 30
  4586.1 1160.38  4605.3 1157.15  4630.8 1155.61  4647.8 1150.46  4665.3 1146.28
  4710.5 1131.46  4722.4 1132.82  4765.2 1135.15  4803.1 1134.21  4815.5 1134.14
  4849.5 1134.64  4873.9 1135.93  4883.8 1135.52  4897.0 1131.23  4907.2 1130.18
  4919.3 1127.59  4923.5 1126.05  4946.8 1125.95  4981.2 1125.80  4983.1 1122.05
  5016.9 1122.05  5018.9 1126.20  5041.1 1126.28  5042.9 1127.27  5049.8 1136.20
  5050.3 1137.43  5173.3 1138.92  5231.7 1142.83  5345.9 1157.15  5409.3 1167.09
#Mann=6,-1,0
  4586.1    0.14       0  4803.1    0.15       0  4815.5    0.08       0
  4946.8    0.15       0  4981.2    0.05       0  5018.9    0.15       0
#XS Ineff=2,0
    0.00 4765.00 1136.50               0
Permanent Ineff=
       F       F
Bank Sta=4981.2,5018.9
XS Rating Curve= 0
Exp/Cntr=0.3,0.1

Type RM Length L Ch R = 1,38776,433,433,433
BEGIN DESCRIPTION:
South Fork 130.0
END DESCRIPTION:
XS GIS Cut Line= 3
      1451730.69       954819.79      1451673.40       954877.07
      1450647.36       954913.53
#Sta/Elev= 30
  4720.9 1176.06  4759.3 1168.65  4768.9 1167.72  4817.9 1155.76  4822.3 1155.75
  4880.2 1143.69  4909.6 1136.37  4924.0 1134.76  4946.3 1135.01  4971.3 1126.01
  4981.4 1123.95  4984.1 1123.90  4985.7 1120.01  5014.3 1120.01  5016.0 1123.90
  5026.7 1124.07  5030.2 1128.93  5036.2 1133.14  5055.6 1132.45  5103.7 1134.92
  5251.3 1136.56  5347.5 1135.47  5358.5 1134.36  5388.3 1134.08  5396.9 1134.85
  5511.2 1136.02  5609.3 1140.68  5672.4 1144.68  5769.5 1156.13  5828.6 1166.27
#Mann=4,-1,0
  4720.9    0.14       0  4981.4    0.15       0  4984.1    0.05       0
  5016.0    0.15       0
#XS Ineff=2,0
       0                 5067.80    0.00 1133.00
Permanent Ineff=
       F       F
Bank Sta=4984.1,5016
XS Rating Curve= 0
Exp/Cntr=0.3,0.1

Type RM Length L Ch R = 1,38343,543,543,543
BEGIN DESCRIPTION:
South Fork 127.0
END DESCRIPTION:
XS GIS Cut Line= 3
      1451355.70       954457.80      1450939.03       954814.57
      1450636.95       954824.99
#Sta/Elev= 30
  4843.7 1156.99  4854.4 1156.01  4869.0 1151.73  4883.3 1145.96  4915.9 1135.97
  4934.8 1134.06  4953.5 1126.28  4964.8 1126.63  4967.4 1123.18  4973.9 1122.77
  4976.6 1118.77  5023.4 1118.77  5026.1 1122.77  5030.6 1126.28  5042.2 1131.14
  5043.2 1132.17  5047.2 1132.34  5071.3 1132.85  5088.8 1132.16  5182.5 1131.69
  5216.3 1133.26  5280.7 1132.97  5354.0 1135.49  5377.9 1135.43  5505.5 1141.41
  5541.3 1145.53  5564.2 1146.27  5612.5 1152.97  5661.5 1162.49  5694.5 1172.86
#Mann=4,-1,0
  4843.7    0.14       0  4883.3    0.15       0  4973.9    0.05       0
  5026.1    0.15       0
Bank Sta=4973.9,5026.1
XS Rating Curve= 0
Exp/Cntr=0.3,0.1

Type RM Length L Ch R = 1,37800,381,381,381
BEGIN DESCRIPTION:
South Fork 126.0
END DESCRIPTION:
XS GIS Cut Line= 3
      1451428.63       954280.72      1450817.02       954302.46
      1450467.72       954304.16
#Sta/Elev= 30
  4388.0 1161.00  4407.1 1158.12  4451.6 1155.18  4501.1 1150.12  4523.0 1146.20
  4610.5 1136.58  4679.8 1131.13  4851.8 1130.89  4877.1 1131.42  4916.3 1128.18
  4927.0 1129.43  4962.7 1129.44  4974.3 1121.68  4985.5 1120.56  4987.0 1117.56
  5013.0 1117.56  5014.5 1120.56  5029.9 1121.56  5060.4 1129.04  5174.6 1127.25
  5223.7 1128.67  5252.3 1127.78  5278.7 1128.77  5298.4 1131.59  5312.2 1140.45
  5321.2 1148.47  5334.1 1162.78  5339.6 1165.89  5344.3 1172.02  5349.3 1176.78
#Mann=5,-1,0
  4388.0    0.15       0  4610.5    0.08       0  4851.8    0.15       0
  4985.5    0.05       0  5014.5    0.15       0
#XS Ineff=2,0
       0                 5200.00    0.00 1130.00
Permanent Ineff=
       F       F
Bank Sta=4985.5,5014.5
XS Rating Curve= 0
Exp/Cntr=0.3,0.1

Type RM Length L Ch R = 1,37419,1148,1148,1148
BEGIN DESCRIPTION:
South Fork 125.0
END DESCRIPTION:
XS GIS Cut Line= 4
      1451345.32       953908.31      1451217.68       953957.80
      1450415.59       953976.03      1450350.49       954056.76
#Sta/Elev= 30
  4288.7 1165.38  4311.6 1162.46  4359.0 1152.40  4388.1 1143.63  4415.8 1133.02
  4452.3 1125.12  4525.7 1126.97  4573.8 1127.76  4704.5 1127.19  4750.3 1127.06
  4777.6 1124.41  4791.9 1124.66  4829.2 1127.23  4961.7 1128.79  4967.3 1120.66
  4976.8 1120.37  4979.2 1116.37  5020.8 1116.37  5023.2 1120.37  5023.4 1120.37
  5023.8 1125.28  5027.9 1127.87  5036.7 1126.73  5078.3 1126.40  5103.5 1128.53
  5125.4 1133.07  5164.7 1146.62  5227.9 1152.49  5271.4 1162.06  5331.6 1171.95
#Mann=5,-1,0
  4288.7    0.15       0  4525.7    0.08       0  4704.5    0.15       0
  4976.8    0.05       0  5023.2    0.15       0
#XS Ineff=2,0
    0.00 4750.00 1131.00               0
Permanent Ineff=
       F       F
Bank Sta=4976.8,5023.2
XS Rating Curve= 0
Exp/Cntr=0.3,0.1

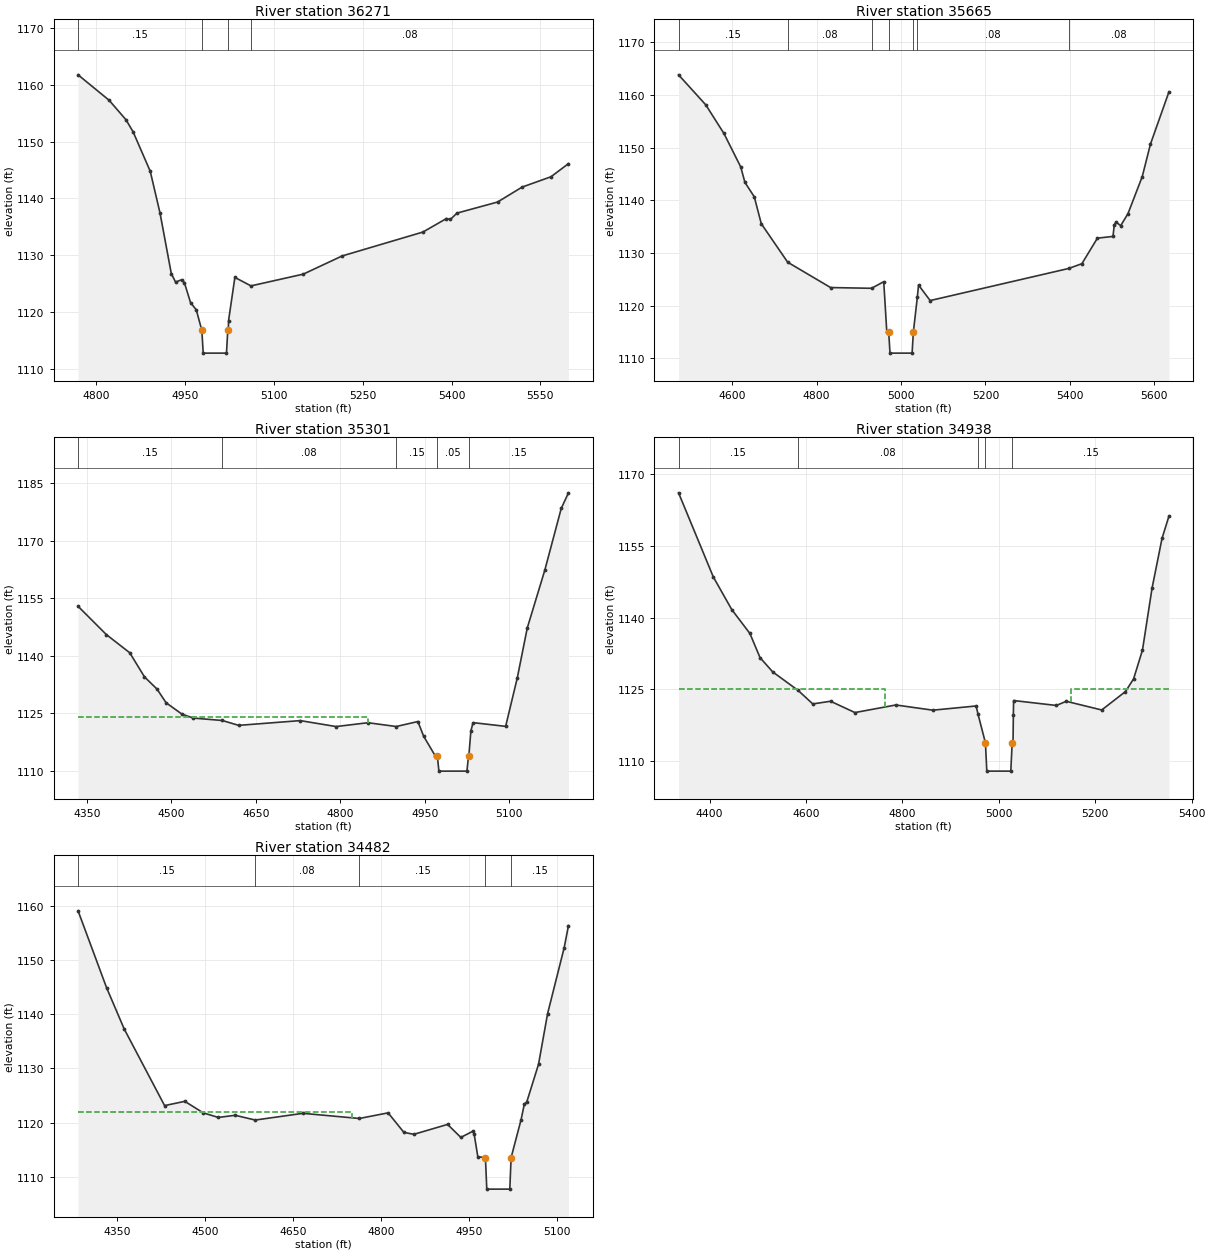
Type RM Length L Ch R = 1,36271,606,606,606
BEGIN DESCRIPTION:
South Fork 121.0
END DESCRIPTION:
XS GIS Cut Line= 3
      1451337.49       953783.34      1451149.97       953671.34
      1450655.19       953314.59
#Sta/Elev= 30
  4769.0 1161.74  4821.6 1157.25  4850.0 1153.82  4861.9 1151.72  4890.9 1144.77
  4907.4 1137.43  4926.5 1126.75  4933.7 1125.25  4944.2 1125.67  4948.6 1125.15
  4959.0 1121.64  4968.7 1120.36  4978.1 1116.74  4980.4 1112.74  5019.7 1112.74
  5021.9 1116.74  5022.9 1116.81  5023.2 1118.44  5033.9 1126.07  5061.1 1124.58
  5149.5 1126.65  5215.1 1129.85  5351.6 1134.06  5391.3 1136.44  5398.0 1136.28
  5409.0 1137.39  5477.6 1139.34  5519.0 1141.97  5567.8 1143.79  5597.4 1146.10
#Mann=4,-1,0
  4769.0    0.15       0  4978.1    0.05       0  5021.9    0.15       0
  5061.1    0.08       0
Bank Sta=4978.1,5021.9
XS Rating Curve= 0
Exp/Cntr=0.3,0.1

Type RM Length L Ch R = 1,35665,364,364,364
BEGIN DESCRIPTION:
South Fork 119.0
END DESCRIPTION:
XS GIS Cut Line= 4
      1451915.61       953426.56      1451470.28       953166.14
      1450995.99       952916.51      1450920.77       952835.37
#Sta/Elev= 30
  4472.6 1163.82  4537.2 1158.11  4580.2 1152.68  4620.0 1146.33  4629.9 1143.40
  4652.1 1140.66  4668.7 1135.55  4731.3 1128.24  4833.0 1123.43  4930.1 1123.29
  4959.0 1124.54  4966.2 1115.04  4970.8 1114.98  4973.8 1110.98  5026.2 1110.98
  5029.2 1114.98  5038.6 1121.58  5041.5 1123.91  5069.0 1120.96  5397.3 1127.05
  5428.7 1127.96  5465.5 1132.81  5502.4 1133.14  5505.5 1135.30  5509.3 1135.87
  5520.8 1135.19  5538.0 1137.47  5571.8 1144.50  5591.3 1150.68  5635.1 1160.59
#Mann=7,-1,0
  4472.6    0.15       0  4731.3    0.08       0  4930.1    0.15       0
  4970.8    0.05       0  5029.2    0.15       0  5038.6    0.08       0
  5397.3    0.08       0
Bank Sta=4970.8,5029.2
XS Rating Curve= 0
Exp/Cntr=0.3,0.1

Type RM Length L Ch R = 1,35301,363,363,363
BEGIN DESCRIPTION:
South Fork 118.0
END DESCRIPTION:
XS GIS Cut Line= 3
      1452074.47       953215.63      1451590.07       952861.45
      1451379.16       952692.20
#Sta/Elev= 30
  4334.6 1152.94  4384.8 1145.57  4426.3 1140.83  4452.5 1134.54  4474.7 1131.37
  4490.9 1127.79  4518.9 1124.84  4539.2 1123.80  4590.6 1123.17  4619.7 1121.90
  4729.0 1123.14  4792.6 1121.59  4849.2 1122.59  4899.4 1121.60  4937.8 1122.90
  4948.1 1119.05  4968.5 1113.98  4972.3 1113.97  4975.1 1109.97  5024.9 1109.97
  5027.7 1113.97  5028.3 1113.98  5031.9 1120.42  5035.7 1122.61  5093.6 1121.64
  5114.3 1134.29  5132.0 1147.29  5163.0 1162.30  5192.3 1178.46  5205.1 1182.52
#Mann=5,-1,0
  4334.6    0.15       0  4590.6    0.08       0  4899.4    0.15       0
  4972.3    0.05       0  5027.7    0.15       0
#XS Ineff=2,0
    0.00 4849.00 1124.00               0
Permanent Ineff=
       F       F
Bank Sta=4972.3,5027.7
XS Rating Curve= 0
Exp/Cntr=0.3,0.1

Type RM Length L Ch R = 1,34938,456,456,456
BEGIN DESCRIPTION:
South Fork 117.0
END DESCRIPTION:
XS GIS Cut Line= 3
      1452347.88       953072.38      1452269.76       953022.91
      1451524.97       952474.98
#Sta/Elev= 30
  4335.8 1166.15  4407.8 1148.54  4446.2 1141.68  4483.8 1136.68  4504.8 1131.62
  4531.1 1128.63  4583.9 1124.74  4614.2 1121.92  4651.1 1122.48  4701.6 1120.11
  4786.4 1121.70  4863.2 1120.61  4953.0 1121.49  4956.7 1119.86  4972.3 1113.75
  4975.1 1107.84  5024.9 1107.84  5027.7 1113.75  5029.5 1113.84  5030.2 1119.67
  5030.7 1122.63  5119.3 1121.60  5139.9 1122.47  5213.4 1120.65  5262.7 1124.51
  5279.6 1127.18  5298.0 1133.21  5317.8 1146.15  5338.6 1156.63  5352.9 1161.27
#Mann=5,-1,0
  4335.8    0.15       0  4583.9    0.08       0  4956.7    0.15       0
  4972.3    0.05       0  5027.7    0.15       0
#XS Ineff=2,0
    0.00 4763.00 1125.00 5150.00    0.00 1125.00
Permanent Ineff=
       F       F
Bank Sta=4972.3,5027.7
XS Rating Curve= 0
Exp/Cntr=0.3,0.1

Type RM Length L Ch R = 1,34482,409,409,409
BEGIN DESCRIPTION:
South Fork 115.0
END DESCRIPTION:
XS GIS Cut Line= 3
      1452358.31       953002.08      1452209.86       952879.68
      1452032.78       952259.88
#Sta/Elev= 30
  4282.8 1159.16  4331.4 1144.96  4361.4 1137.34  4430.5 1123.13  4465.0 1123.92
  4496.4 1121.79  4522.2 1120.94  4550.9 1121.34  4585.2 1120.46  4666.6 1121.70
  4762.9 1120.75  4812.0 1121.79  4838.9 1118.18  4855.9 1117.82  4913.5 1119.65
  4936.1 1117.25  4956.9 1118.40  4958.8 1117.90  4965.1 1113.68  4978.1 1113.50
  4980.4 1107.68  5019.7 1107.68  5021.9 1113.50  5038.9 1120.51  5044.5 1123.41
  5048.7 1123.82  5068.7 1130.77  5084.2 1140.15  5112.5 1152.34  5119.8 1156.43
#Mann=5,-1,0
  4282.8    0.15       0  4585.2    0.08       0  4762.9    0.15       0
  4978.1    0.05       0  5021.9    0.15       0
#XS Ineff=2,0
    0.00 4750.00 1122.00               0
Permanent Ineff=
       F       F
Bank Sta=4978.1,5021.9
XS Rating Curve= 0
Exp/Cntr=0.3,0.1