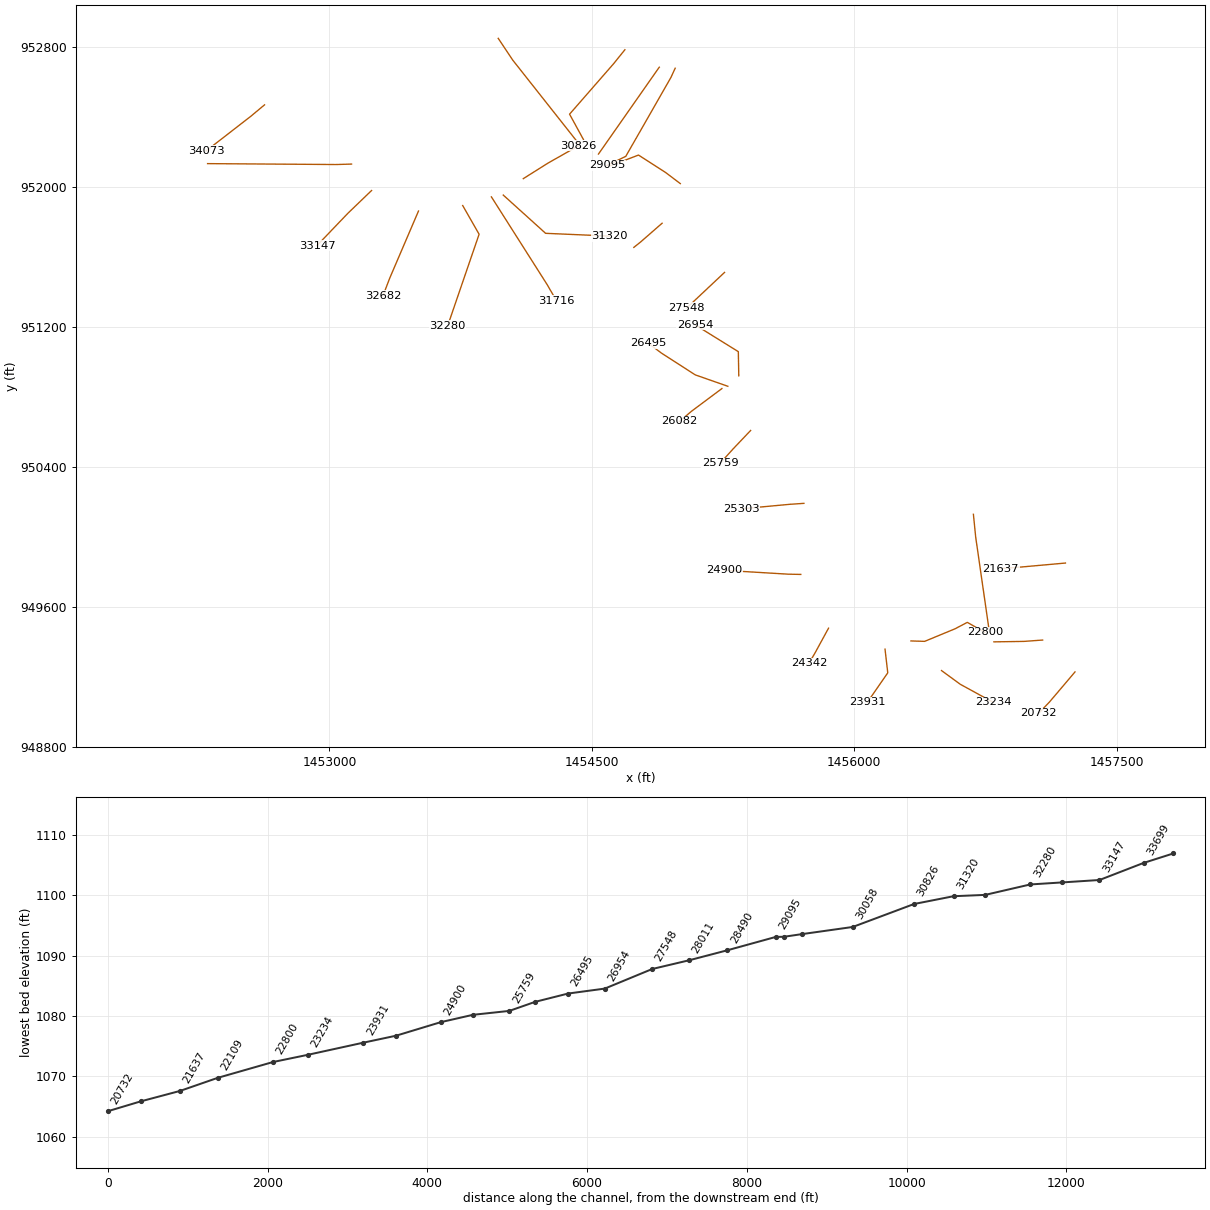
HEC-RAS study South Fork.prj: South Fork Limited Detail Study

--- South Fork.g01 (geometry) --- (continued)

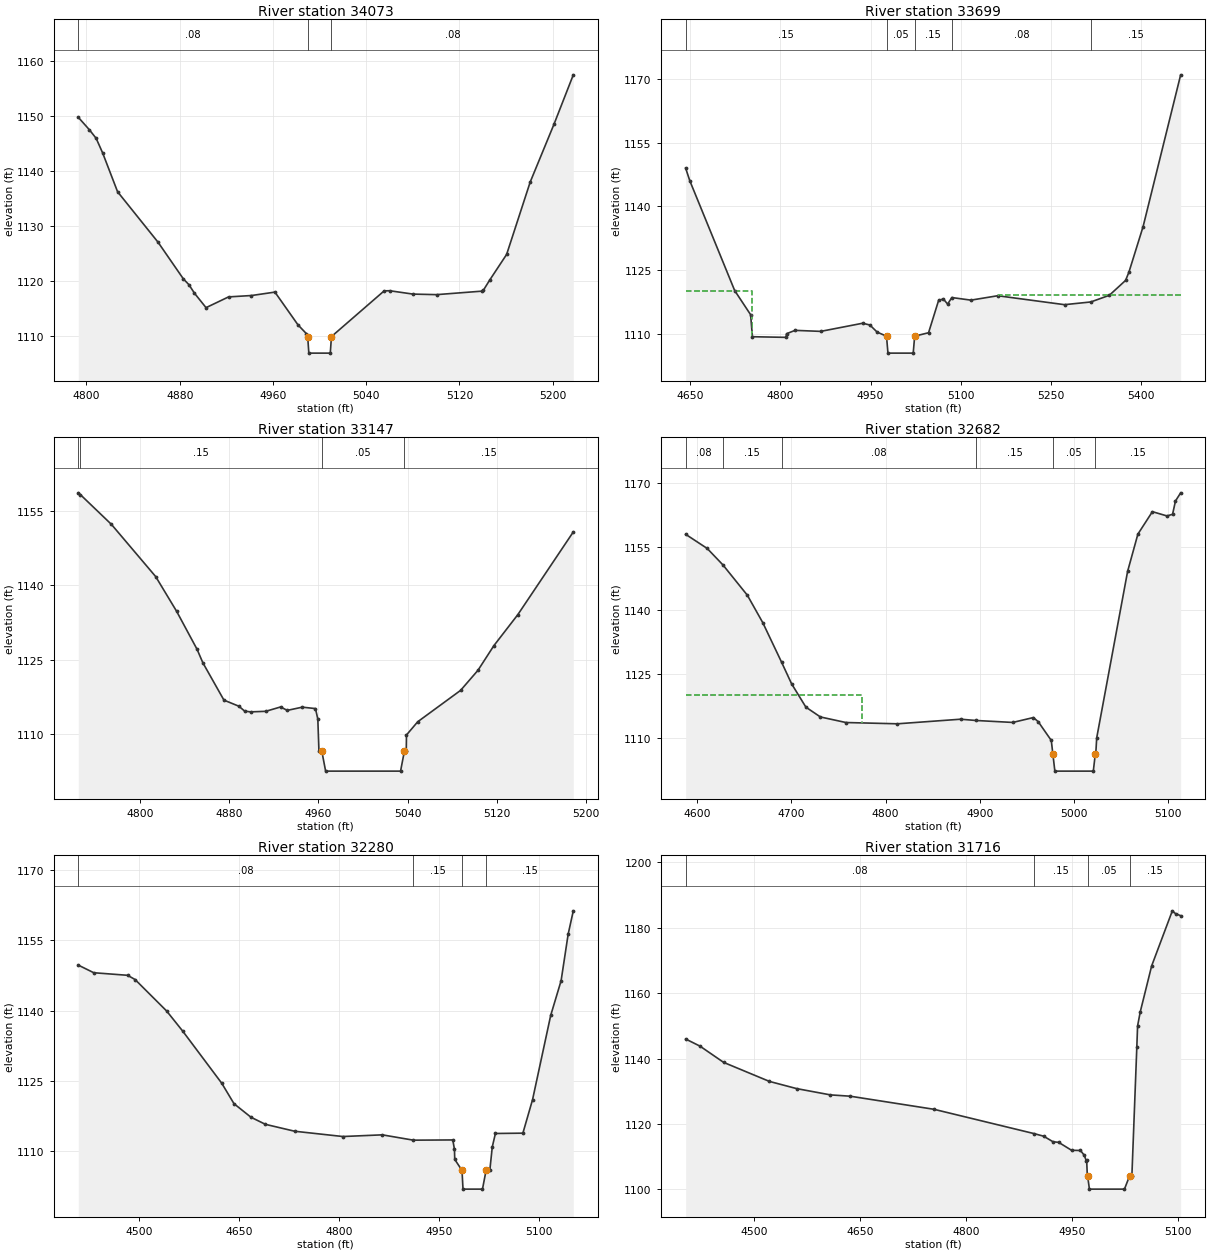
Type RM Length L Ch R = 1,34073,374,374,374
BEGIN DESCRIPTION:
South Fork 114.0
END DESCRIPTION:
XS GIS Cut Line= 3
      1452629.16       952468.24      1452551.01       952403.12
      1452295.79       952205.19
#Sta/Elev= 30
  4793.0 1149.71  4802.4 1147.48  4808.3 1145.91  4813.9 1143.25  4826.7 1136.22
  4861.4 1127.08  4883.2 1120.41  4887.9 1119.38  4892.7 1117.82  4902.6 1115.21
  4921.9 1117.16  4941.6 1117.41  4961.7 1118.03  4981.5 1112.09  4988.6 1110.52
  4989.8 1109.97  4990.8 1106.97  5009.2 1106.97  5010.2 1109.97  5055.4 1118.25
  5060.1 1118.28  5080.1 1117.67  5100.4 1117.57  5139.1 1118.20  5140.5 1118.35
  5145.9 1120.19  5160.5 1124.86  5180.7 1137.97  5201.1 1148.44  5217.7 1157.41
#Mann=3,-1,0
  4793.0    0.08       0  4989.8   0.048       0  5010.2    0.08       0
Bank Sta=4989.8,5010.2
XS Rating Curve= 0
Exp/Cntr=0.3,0.1

Type RM Length L Ch R = 1,33699,552,552,552
BEGIN DESCRIPTION:
South Fork 112.0
END DESCRIPTION:
XS GIS Cut Line= 3
      1453126.50       952129.68      1453037.99       952127.07
      1452303.65       952132.28
#Sta/Elev= 30
  4642.7 1149.02  4649.6 1146.05  4724.2 1120.15  4750.7 1114.45  4753.7 1109.26
  4809.6 1109.11  4810.4 1109.97  4824.6 1110.76  4867.2 1110.52  4936.9 1112.44
  4948.9 1112.03  4961.1 1110.34  4976.6 1109.39  4979.0 1105.39  5021.0 1105.39
  5023.4 1109.39  5046.5 1110.20  5063.2 1117.82  5071.1 1118.17  5078.2 1116.95
  5085.2 1118.50  5117.0 1117.89  5161.5 1118.93  5272.5 1116.82  5316.2 1117.46
  5347.0 1119.03  5374.0 1122.54  5379.6 1124.50  5403.1 1135.21  5465.6 1171.04
#Mann=5,-1,0
  4642.7    0.15       0  4976.6    0.05       0  5023.4    0.15       0
  5085.2    0.08       0  5316.2    0.15       0
#XS Ineff=2,0
    0.00 4753.70 1120.00 5161.50    0.00 1119.00
Permanent Ineff=
       F       F
Bank Sta=4976.6,5023.4
XS Rating Curve= 0
Exp/Cntr=0.3,0.1

Type RM Length L Ch R = 1,33147,465,465,465
BEGIN DESCRIPTION:
South Fork 111.0
END DESCRIPTION:
XS GIS Cut Line= 3
      1453241.12       951978.64      1453105.70       951848.43
      1452928.60       951663.52
#Sta/Elev= 30
  4744.6 1158.68  4746.4 1158.33  4774.3 1152.32  4814.0 1141.79  4832.7 1134.82
  4851.1 1127.13  4856.3 1124.41  4875.2 1116.88  4888.6 1115.65  4893.8 1114.66
  4899.1 1114.51  4912.7 1114.62  4926.0 1115.50  4932.0 1114.81  4945.5 1115.46
  4957.3 1115.17  4959.4 1113.04  4960.4 1106.64  4963.0 1106.56  4966.4 1102.56
  5033.6 1102.56  5037.0 1106.56  5038.7 1106.56  5038.9 1109.85  5049.0 1112.52
  5087.4 1118.84  5103.0 1122.89  5117.3 1127.87  5138.7 1134.10  5188.5 1150.80
#Mann=4,-1,0
  4744.6    0.08       0  4746.4    0.15       0  4963.0    0.05       0
  5037.0    0.15       0
Bank Sta=4963,5037
XS Rating Curve= 0
Exp/Cntr=0.3,0.1

Type RM Length L Ch R = 1,32682,402,402,402
BEGIN DESCRIPTION:
South Fork 109.0
END DESCRIPTION:
XS GIS Cut Line= 3
      1453509.34       951861.44      1453345.28       951478.64
      1453306.21       951377.07
#Sta/Elev= 30
  4587.8 1157.95  4610.7 1154.61  4627.4 1150.73  4653.3 1143.59  4669.7 1137.11
  4689.6 1127.82  4700.2 1122.74  4715.4 1117.23  4730.8 1114.92  4757.9 1113.61
  4812.6 1113.31  4879.5 1114.39  4895.9 1114.09  4934.9 1113.63  4956.8 1114.78
  4961.9 1113.82  4975.8 1109.39  4977.5 1106.16  4979.6 1102.16  5020.4 1102.16
  5022.5 1106.16  5023.0 1106.17  5024.0 1109.99  5056.8 1149.22  5067.7 1157.99
  5083.1 1163.28  5098.5 1162.28  5104.5 1162.66  5107.6 1165.80  5113.1 1167.72
#Mann=6,-1,0
  4587.8    0.08       0  4627.4    0.15       0  4689.6    0.08       0
  4895.9    0.15       0  4977.5    0.05       0  5022.5    0.15       0
#XS Ineff=2,0
    0.00 4775.00 1120.00               0
Permanent Ineff=
       F       F
Bank Sta=4977.5,5022.5
XS Rating Curve= 0
Exp/Cntr=0.3,0.1

Type RM Length L Ch R = 1,32280,564,564,564
BEGIN DESCRIPTION:
South Fork 108.0
END DESCRIPTION:
XS GIS Cut Line= 3
      1453761.97       951892.66      1453855.70       951728.64
      1453676.02       951205.23
#Sta/Elev= 30
  4408.5 1149.73  4431.7 1148.10  4482.5 1147.55  4493.7 1146.64  4540.9 1139.93
  4565.0 1135.63  4623.6 1124.47  4642.0 1120.09  4667.5 1117.19  4689.1 1115.68
  4733.0 1114.20  4805.3 1113.07  4864.4 1113.43  4911.0 1112.29  4970.1 1112.34
  4972.6 1110.32  4973.0 1108.18  4983.9 1105.82  4985.4 1101.82  5014.6 1101.82
  5020.0 1105.82  5025.6 1105.82  5029.3 1110.85  5034.0 1113.72  5075.2 1113.79
  5089.7 1120.96  5116.9 1138.97  5132.5 1146.39  5143.1 1156.36  5150.8 1161.34
#Mann=4,-1,0
  4408.5    0.08       0  4911.0    0.15       0  4983.9    0.05       0
  5020.0    0.15       0
Bank Sta=4983.9,5020
XS Rating Curve= 0
Exp/Cntr=0.3,0.1

Type RM Length L Ch R = 1,31716,396,396,396
BEGIN DESCRIPTION:
South Fork 106.0
END DESCRIPTION:
XS GIS Cut Line= 3
      1453926.00       951942.19      1454243.72       951442.18
      1454298.43       951348.39
#Sta/Elev= 30
  4403.4 1145.97  4423.7 1143.79  4457.2 1138.82  4522.0 1133.01  4560.6 1130.81
  4608.4 1128.89  4636.4 1128.49  4755.0 1124.49  4896.8 1117.06  4910.4 1116.26
  4923.6 1114.57  4931.6 1114.39  4949.9 1111.96  4962.5 1111.90  4967.9 1110.44
  4970.7 1108.77  4971.3 1108.97  4972.2 1104.11  4972.6 1104.09  4975.2 1100.09
  5024.8 1100.09  5032.0 1104.09  5035.3 1104.09  5042.3 1143.41  5043.4 1149.98
  5047.2 1154.29  5063.3 1168.30  5092.6 1185.14  5097.1 1184.28  5104.4 1183.65
#Mann=4,-1,0
  4403.4    0.08       0  4896.8    0.15       0  4972.6    0.05       0
  5032.0    0.15       0
Bank Sta=4972.6,5032
XS Rating Curve= 0
Exp/Cntr=0.3,0.1

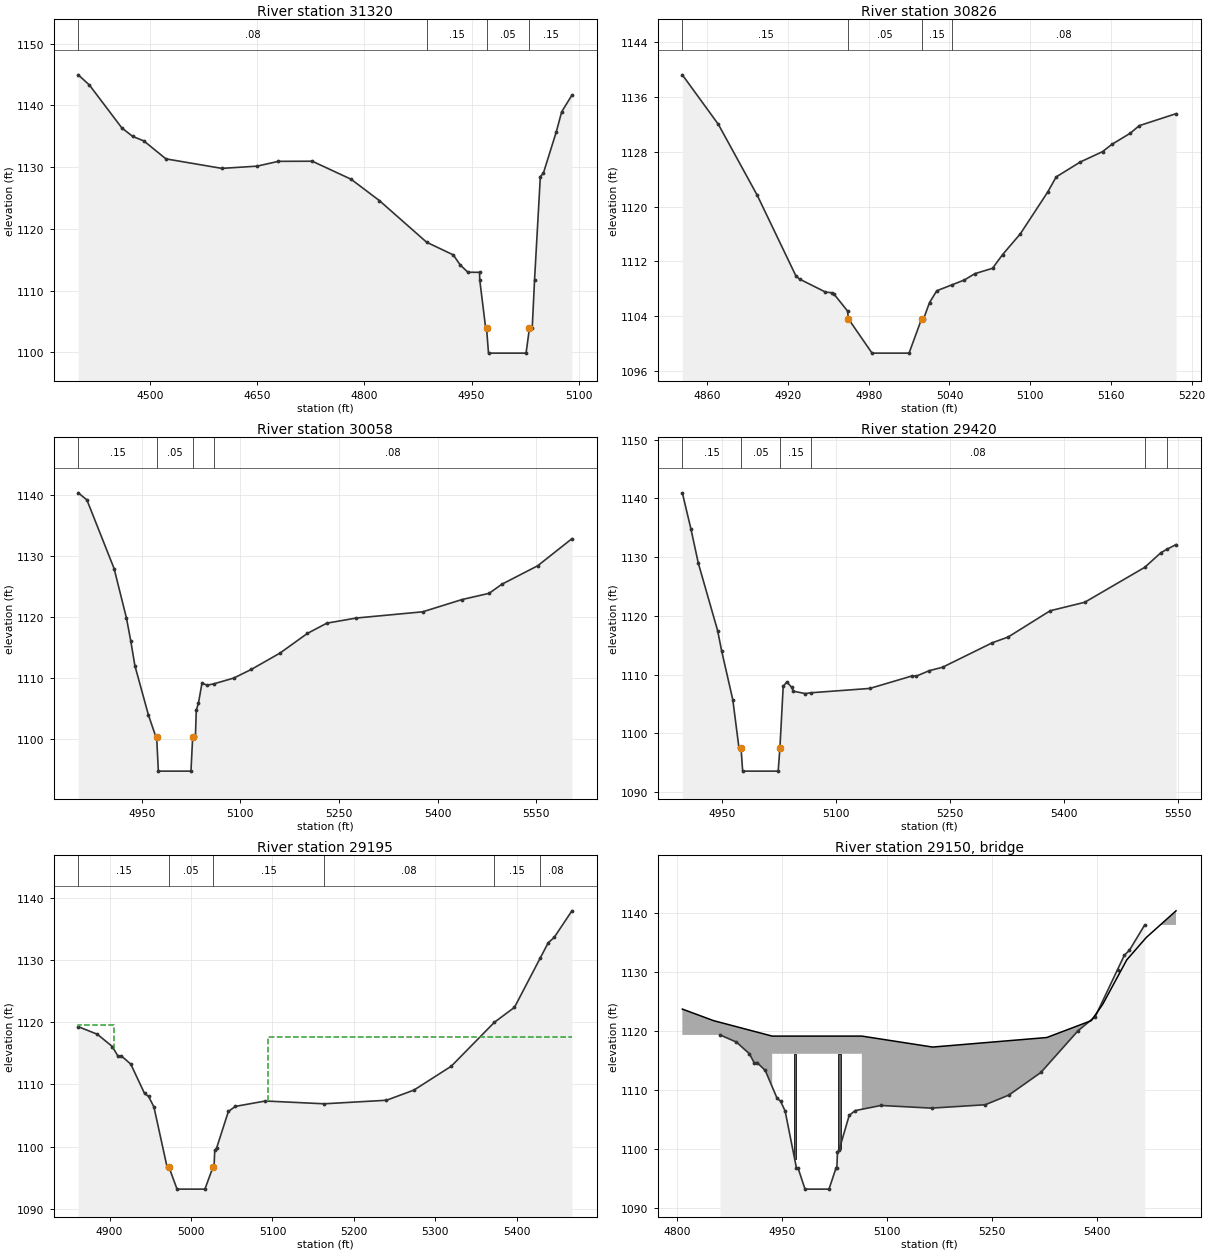
Type RM Length L Ch R = 1,31320,494,494,494
BEGIN DESCRIPTION:
South Fork 105.0
END DESCRIPTION:
XS GIS Cut Line= 3
      1453993.69       951952.62      1454235.90       951733.84
      1454600.48       951718.22
#Sta/Elev= 30
  4399.2 1144.97  4414.9 1143.31  4460.4 1136.35  4475.6 1134.98  4491.1 1134.26
  4522.0 1131.35  4600.3 1129.81  4649.5 1130.17  4679.6 1130.95  4726.9 1130.97
  4781.3 1128.05  4820.8 1124.60  4887.1 1117.84  4924.4 1115.79  4933.9 1114.19
  4944.8 1112.98  4961.1 1112.96  4961.5 1111.68  4969.8 1103.87  4971.0 1103.88
  4973.7 1099.87  5026.3 1099.87  5031.0 1103.88  5034.9 1103.87  5038.2 1111.79
  5046.3 1128.49  5050.5 1129.02  5068.7 1135.76  5076.2 1138.99  5090.5 1141.67
#Mann=4,-1,0
  4399.2    0.08       0  4887.1    0.15       0  4971.0    0.05       0
  5031.0    0.15       0
Bank Sta=4971,5031
XS Rating Curve= 0
Exp/Cntr=0.3,0.1

Type RM Length L Ch R = 1,30826,768,768,768
BEGIN DESCRIPTION:
South Fork 103.0
END DESCRIPTION:
XS GIS Cut Line= 3
      1454108.33       952046.36      1454248.93       952134.89
      1454423.37       952233.83
#Sta/Elev= 30
  4841.6 1139.26  4868.4 1132.01  4897.3 1121.63  4925.9 1109.89  4928.7 1109.40
  4947.9 1107.51  4952.4 1107.41  4954.5 1107.15  4964.3 1104.74  4965.0 1103.58
  4982.5 1098.58  5010.0 1098.58  5019.3 1103.58  5020.8 1103.59  5025.2 1105.97
  5030.6 1107.70  5041.6 1108.54  5051.1 1109.27  5058.8 1110.19  5072.0 1110.98
  5079.5 1112.99  5092.7 1116.03  5112.9 1122.10  5119.3 1124.34  5137.2 1126.52
  5153.7 1128.03  5160.6 1129.09  5174.2 1130.71  5181.0 1131.83  5208.3 1133.58
#Mann=4,-1,0
  4841.6    0.15       0  4965.0    0.05       0  5019.3    0.15       0
  5041.6    0.08       0
Bank Sta=4965,5019.3
XS Rating Curve= 0
Exp/Cntr=0.3,0.1

Type RM Length L Ch R = 1,30058,638,638,638
BEGIN DESCRIPTION:
South Fork 100.0
END DESCRIPTION:
XS GIS Cut Line= 3
      1453965.06       952848.44      1454048.40       952723.43
      1454420.83       952252.04
#Sta/Elev= 30
  4853.3 1140.38  4866.5 1139.22  4907.9 1127.96  4926.7 1119.84  4933.3 1116.05
  4939.5 1112.05  4960.2 1103.93  4971.6 1100.33  4972.6 1100.35  4975.2 1094.77
  5024.8 1094.77  5027.4 1100.35  5031.6 1100.47  5032.9 1104.78  5036.1 1105.86
  5041.5 1109.15  5049.6 1108.87  5059.1 1109.06  5089.8 1110.02  5116.6 1111.44
  5160.0 1114.10  5201.8 1117.33  5231.5 1119.02  5276.2 1119.86  5377.3 1120.88
  5437.1 1122.89  5478.4 1123.91  5497.6 1125.39  5552.3 1128.43  5604.3 1132.86
#Mann=4,-1,0
  4853.3    0.15       0  4972.6    0.05       0  5027.4    0.15       0
  5059.1    0.08       0
Bank Sta=4972.6,5027.4
XS Rating Curve= 0
Exp/Cntr=0.3,0.1

Type RM Length L Ch R = 1,29420,225,225,225
BEGIN DESCRIPTION:
South Fork 98.0
END DESCRIPTION:
XS GIS Cut Line= 4
      1454689.01       952783.30      1454623.93       952702.59
      1454372.77       952414.87      1454452.06       952270.28
#Sta/Elev= 30
  4897.1 1140.96  4908.3 1134.88  4918.2 1128.96  4943.6 1117.50  4948.9 1114.04
  4963.6 1105.73  4971.6 1097.65  4974.4 1097.58  4976.6 1093.58  5023.4 1093.58
  5025.7 1097.58  5030.0 1108.02  5034.8 1108.77  5041.0 1107.87  5043.4 1107.19
  5059.2 1106.78  5066.4 1106.92  5144.1 1107.66  5199.1 1109.76  5205.5 1109.76
  5222.4 1110.68  5239.9 1111.26  5305.6 1115.44  5326.4 1116.41  5381.7 1120.88
  5427.4 1122.33  5506.3 1128.27  5527.8 1130.78  5536.2 1131.39  5547.6 1132.15
#Mann=6,-1,0
  4897.1    0.15       0  4974.4    0.05       0  5025.7    0.15       0
  5066.4    0.08       0  5506.3    0.15       0  5536.2    0.08       0
Bank Sta=4974.4,5025.7
XS Rating Curve= 0
Exp/Cntr=0.5,0.3

Type RM Length L Ch R = 1,29195,100,100,100
BEGIN DESCRIPTION:
Mountain Park Rd US
END DESCRIPTION:
XS GIS Cut Line= 3
      1454885.75       952683.21      1454883.52       952680.68
      1454537.98       952186.95
#Sta/Elev= 30
  4861.6 1119.30  4885.0 1118.08  4903.5 1116.10  4910.6 1114.50  4914.3 1114.62
  4926.1 1113.27  4943.0 1108.55  4948.0 1108.06  4954.5 1106.38  4970.7 1096.68
  4973.0 1096.68  4982.9 1093.14  5017.1 1093.14  5027.0 1096.68  5028.3 1096.75
  5029.2 1099.39  5031.4 1099.73  5045.9 1105.64  5054.4 1106.46  5091.3 1107.33
  5163.4 1106.88  5240.0 1107.45  5273.7 1109.09  5319.5 1112.93  5372.5 1120.01
  5397.1 1122.41  5428.8 1130.37  5438.5 1132.80  5445.9 1133.68  5467.6 1137.95
#Mann=6,-1,0
  4861.6    0.15       0  4973.0    0.05       0  5027.0    0.15       0
  5163.4    0.08       0  5372.5    0.15       0  5428.8    0.08       0
#XS Ineff=2,0
    0.00 4905.50 1119.61 5094.50    0.00 1117.61
Permanent Ineff=
       F       F
Bank Sta=4973,5027
XS Rating Curve= 0
Exp/Cntr=0.5,0.3

Type RM Length L Ch R =3,29150,,,
BEGIN DESCRIPTION:
Mountain Park Rd TOR
Structure ID: LDS_SFMR_02
Approximate Survey Structure
END DESCRIPTION:
Bridge Culvert--1,0,-1,-1,0
Deck Dist Width WeirC Skew NumUp NumDn MinLoCord MaxHiCord MaxSubmerge Is_Ogee
30.5,29,3,,13,13,,,0.95,0,1,1,,,
  4807.8  4852.4  4936.0  4936.0  5064.0  5064.0  5165.0  5327.9  5391.4  5407.8
  5442.0  5469.8  5512.3
 1123.68 1121.72 1119.10 1119.10 1119.10 1119.10 1117.24 1118.86 1121.72 1124.52
 1132.03 1135.82 1140.35
 1073.14 1073.14 1073.14 1116.10 1116.10 1073.14 1073.14 1073.14 1073.14 1073.14
 1073.14 1073.14 1073.14
  4807.8  4852.4  4936.0  4936.0  5064.0  5064.0  5165.0  5327.9  5391.4  5407.8
  5442.0  5469.8  5512.3
 1123.68 1121.72 1119.10 1119.10 1119.10 1119.10 1117.24 1118.86 1121.72 1124.52
 1132.03 1135.82 1140.35
 1073.14 1073.14 1073.14 1116.10 1116.10 1073.14 1073.14 1073.14 1073.14 1073.14
 1073.14 1073.14 1073.14
Pier Skew, UpSta & Num, DnSta & Num=,4968,2,4968,2,0,0,0,0,0
       3       3
 1096.00 1116.10
       3       3
 1096.00 1116.10
Pier Skew, UpSta & Num, DnSta & Num=,5032,2,5032,2,0,0,0,0,0
       3       3
 1099.97 1116.10
       3       3
 1096.00 1116.10
Abutment Skew #Up #Dn=,2,2
  4936.0  4957.6
 1116.10 1104.98
  4936.0  4957.6
 1116.10 1105.03
Abutment Skew #Up #Dn=,2,2
  5042.5  5064.0
 1104.25 1116.10
  5042.5  5064.0
 1103.33 1116.10
BR Coef=1,1,0,1.25,0,,,0.8,0,2,0,
WSPro=,,,, 1 ,,,, 0 ,,,, 0 ,,,,-1 ,-1 ,-1 , 0 , 0 , 0 , 0 , 0
BC Design=,,0,,0,,,,,,

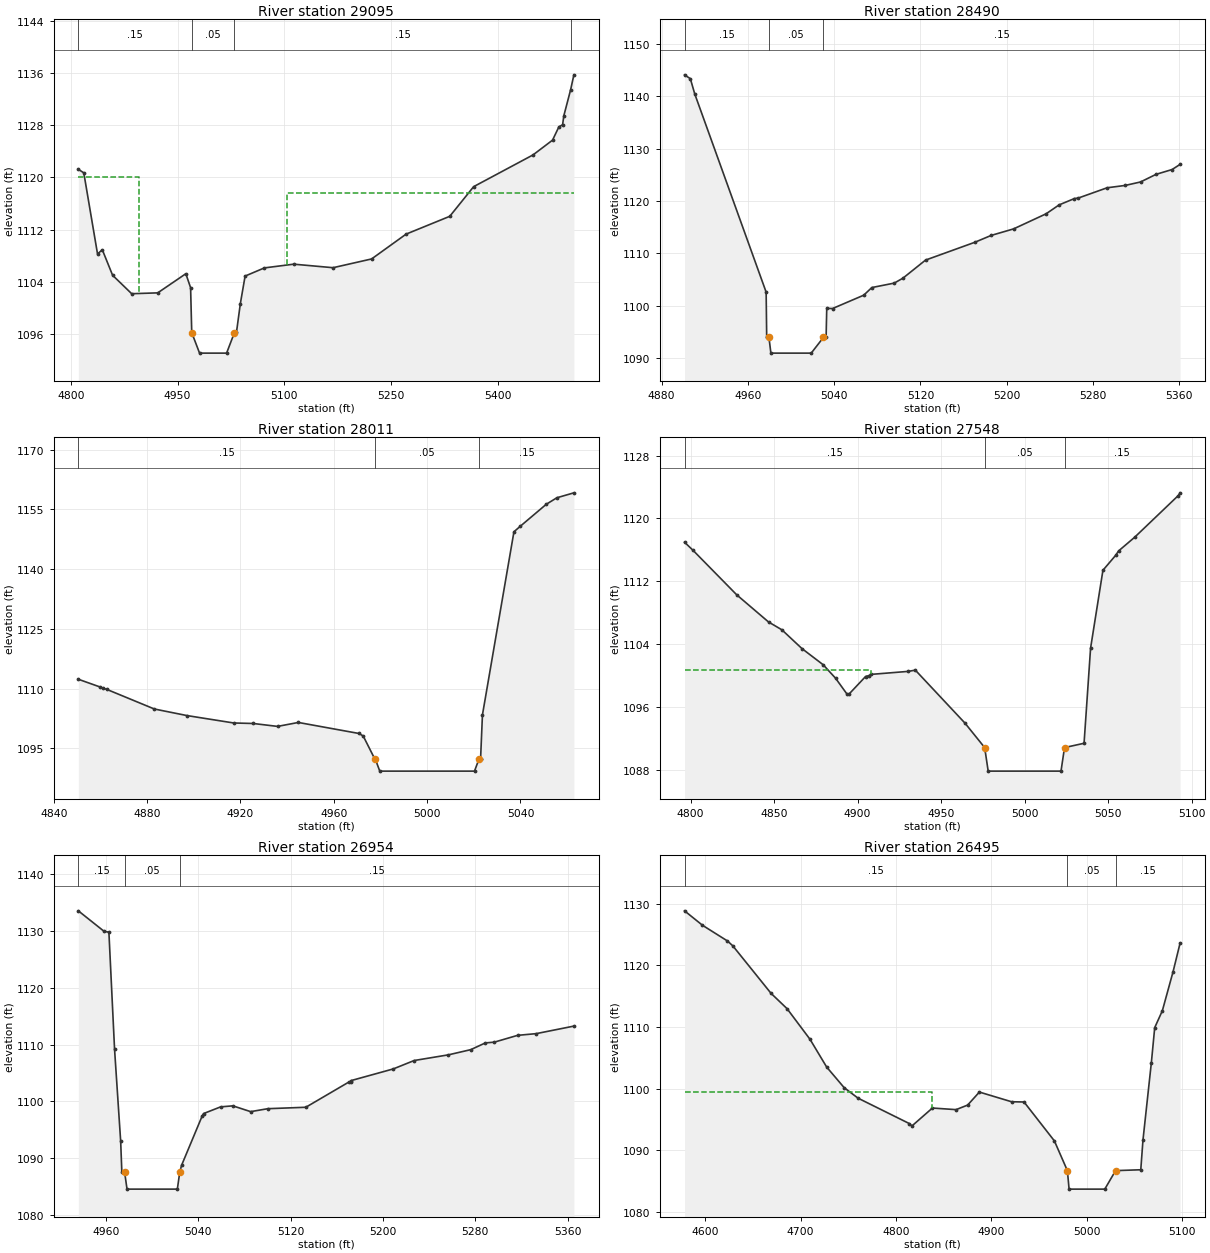
Type RM Length L Ch R = 1,29095,605,605,605
BEGIN DESCRIPTION:
Mountain Park Rd DS
END DESCRIPTION:
XS GIS Cut Line= 4
      1454976.63       952677.73      1454952.05       952624.47
      1454694.24       952173.95      1454587.49       952121.88
#Sta/Elev= 30
  4810.6 1121.25  4818.3 1120.70  4837.6 1108.29  4844.3 1108.94  4858.8 1105.03
  4885.6 1102.21  4922.2 1102.34  4961.7 1105.27  4968.4 1103.13  4970.0 1096.26
  4981.0 1093.12  5019.0 1093.12  5030.0 1096.26  5032.9 1096.33  5038.3 1100.68
  5045.0 1104.91  5072.1 1106.16  5113.3 1106.73  5168.6 1106.19  5222.8 1107.53
  5271.3 1111.33  5332.6 1114.05  5366.2 1118.59  5449.7 1123.45  5477.1 1125.71
  5485.9 1127.72  5491.2 1128.07  5493.0 1129.46  5502.4 1133.38  5507.1 1135.70
#Mann=4,-1,0
  4810.6    0.15       0  4970.0    0.05       0  5030.0    0.15       0
  5502.4    0.08       0
#XS Ineff=2,0
    0.00 4895.50 1120.05 5104.50    0.00 1117.64
Permanent Ineff=
       F       F
Bank Sta=4970,5030
XS Rating Curve= 0
Exp/Cntr=0.5,0.3

Type RM Length L Ch R = 1,28490,479,479,479
BEGIN DESCRIPTION:
South Fork 95.0
END DESCRIPTION:
XS GIS Cut Line= 4
      1455005.85       952018.06      1454921.72       952081.63
      1454766.78       952181.24      1454608.11       952120.36
#Sta/Elev= 30
  4901.2 1144.13  4906.6 1143.39  4910.7 1140.47  4976.9 1102.57  4977.4 1093.94
  4979.5 1093.91  4981.3 1090.91  5018.7 1090.91  5030.0 1093.91  5032.5 1093.92
  5033.1 1099.47  5038.5 1099.44  5067.4 1101.99  5074.9 1103.45  5095.7 1104.30
  5103.8 1105.25  5124.7 1108.70  5170.2 1112.09  5185.6 1113.42  5206.4 1114.67
  5236.5 1117.55  5248.6 1119.26  5262.8 1120.47  5266.3 1120.56  5293.1 1122.53
  5309.9 1122.98  5324.1 1123.64  5338.5 1125.10  5353.4 1126.02  5360.8 1127.01
#Mann=3,-1,0
  4901.2    0.15       0  4979.5    0.05       0  5030.0    0.15       0
Bank Sta=4979.5,5030
XS Rating Curve= 0
Exp/Cntr=0.3,0.1

Type RM Length L Ch R = 1,28011,463,463,463
BEGIN DESCRIPTION:
South Fork 93.0
END DESCRIPTION:
XS GIS Cut Line= 3
      1454901.69       951791.47      1454779.31       951684.71
      1454740.27       951653.48
#Sta/Elev= 24
  4850.5 1112.34  4859.8 1110.40  4861.2 1110.08  4862.8 1109.77  4883.1 1104.86
  4897.1 1103.21  4917.1 1101.35  4925.5 1101.22  4935.9 1100.49  4944.8 1101.48
  4970.8 1098.71  4972.6 1098.08  4977.6 1092.26  4977.8 1092.25  4979.7 1089.25
  5020.3 1089.25  5022.2 1092.25  5022.9 1092.29  5023.7 1103.38  5037.2 1149.40
  5039.8 1150.73  5051.1 1156.33  5055.6 1157.95  5062.9 1159.19
#Mann=3,-1,0
  4850.5    0.15       0  4977.8    0.05       0  5022.2    0.15       0
Bank Sta=4977.8,5022.2
XS Rating Curve= 0
Exp/Cntr=0.3,0.1

Type RM Length L Ch R = 1,27548,594,594,594
BEGIN DESCRIPTION:
South Fork 92.0
END DESCRIPTION:
XS GIS Cut Line= 3
      1455258.50       951510.26      1455128.27       951387.84
      1455042.29       951307.08
#Sta/Elev= 28
  4796.4 1116.98  4801.6 1115.92  4827.7 1110.26  4846.7 1106.81  4854.7 1105.81
  4866.7 1103.42  4879.4 1101.36  4886.8 1099.65  4893.5 1097.67  4894.8 1097.60
  4904.8 1099.86  4906.8 1099.97  4908.1 1100.13  4930.2 1100.51  4934.6 1100.67
  4964.3 1093.92  4976.1 1090.80  4978.2 1087.80  5021.8 1087.80  5023.9 1090.80
  5035.6 1091.35  5039.5 1103.47  5046.9 1113.40  5054.5 1115.30  5056.3 1115.87
  5065.9 1117.61  5092.0 1122.92  5093.1 1123.27
#Mann=3,-1,0
  4796.4    0.15       0  4976.1    0.05       0  5023.9    0.15       0
#XS Ineff=2,0
    0.00 4908.10 1100.67               0
Permanent Ineff=
       F       F
Bank Sta=4976.1,5023.9
XS Rating Curve= 0
Exp/Cntr=0.3,0.1

Type RM Length L Ch R = 1,26954,459,459,459
BEGIN DESCRIPTION:
South Fork 90.0
END DESCRIPTION:
XS GIS Cut Line= 3
      1455340.09       950919.47      1455337.48       951057.48
      1455089.87       951211.04
#Sta/Elev= 30
  4936.0 1133.54  4958.2 1129.95  4962.5 1129.77  4967.4 1109.17  4972.7 1092.95
  4973.7 1087.58  4976.1 1087.55  4978.2 1084.55  5021.8 1084.55  5023.9 1087.55
  5025.5 1088.76  5043.2 1097.37  5044.5 1097.85  5059.3 1099.03  5069.9 1099.21
  5085.3 1098.19  5100.2 1098.71  5133.1 1098.96  5170.5 1103.41  5171.9 1103.41
  5172.4 1103.66  5208.9 1105.71  5227.0 1107.19  5256.7 1108.19  5276.0 1109.10
  5288.7 1110.29  5296.4 1110.42  5316.6 1111.62  5332.7 1111.92  5365.4 1113.25
#Mann=3,-1,0
  4936.0    0.15       0  4976.1    0.05       0  5023.9    0.15       0
Bank Sta=4976.1,5023.9
XS Rating Curve= 0
Exp/Cntr=0.3,0.1

Type RM Length L Ch R = 1,26495,413,413,413
BEGIN DESCRIPTION:
South Fork 89.0
END DESCRIPTION:
XS GIS Cut Line= 4
      1455277.62       950859.55      1455091.10       950924.79
      1454897.38       951049.66      1454824.48       951104.34
#Sta/Elev= 30
  4578.4 1128.86  4597.2 1126.52  4623.4 1123.97  4629.0 1123.18  4669.1 1115.47
  4685.8 1113.00  4709.9 1108.02  4727.3 1103.53  4745.6 1100.19  4760.2 1098.48
  4813.8 1094.37  4816.7 1093.98  4838.1 1096.88  4862.9 1096.62  4875.0 1097.36
  4887.3 1099.47  4921.0 1097.90  4934.1 1097.86  4965.9 1091.55  4979.5 1086.73
  4981.3 1083.73  5018.7 1083.73  5030.0 1086.73  5056.4 1086.87  5058.7 1091.69
  5067.5 1104.26  5071.0 1109.92  5079.0 1112.66  5090.2 1118.97  5097.6 1123.64
#Mann=3,-1,0
  4578.4    0.15       0  4979.5    0.05       0  5030.0    0.15       0
#XS Ineff=2,0
    0.00 4838.10 1099.44               0
Permanent Ineff=
       F       F
Bank Sta=4979.5,5030
XS Rating Curve= 0
Exp/Cntr=0.3,0.1

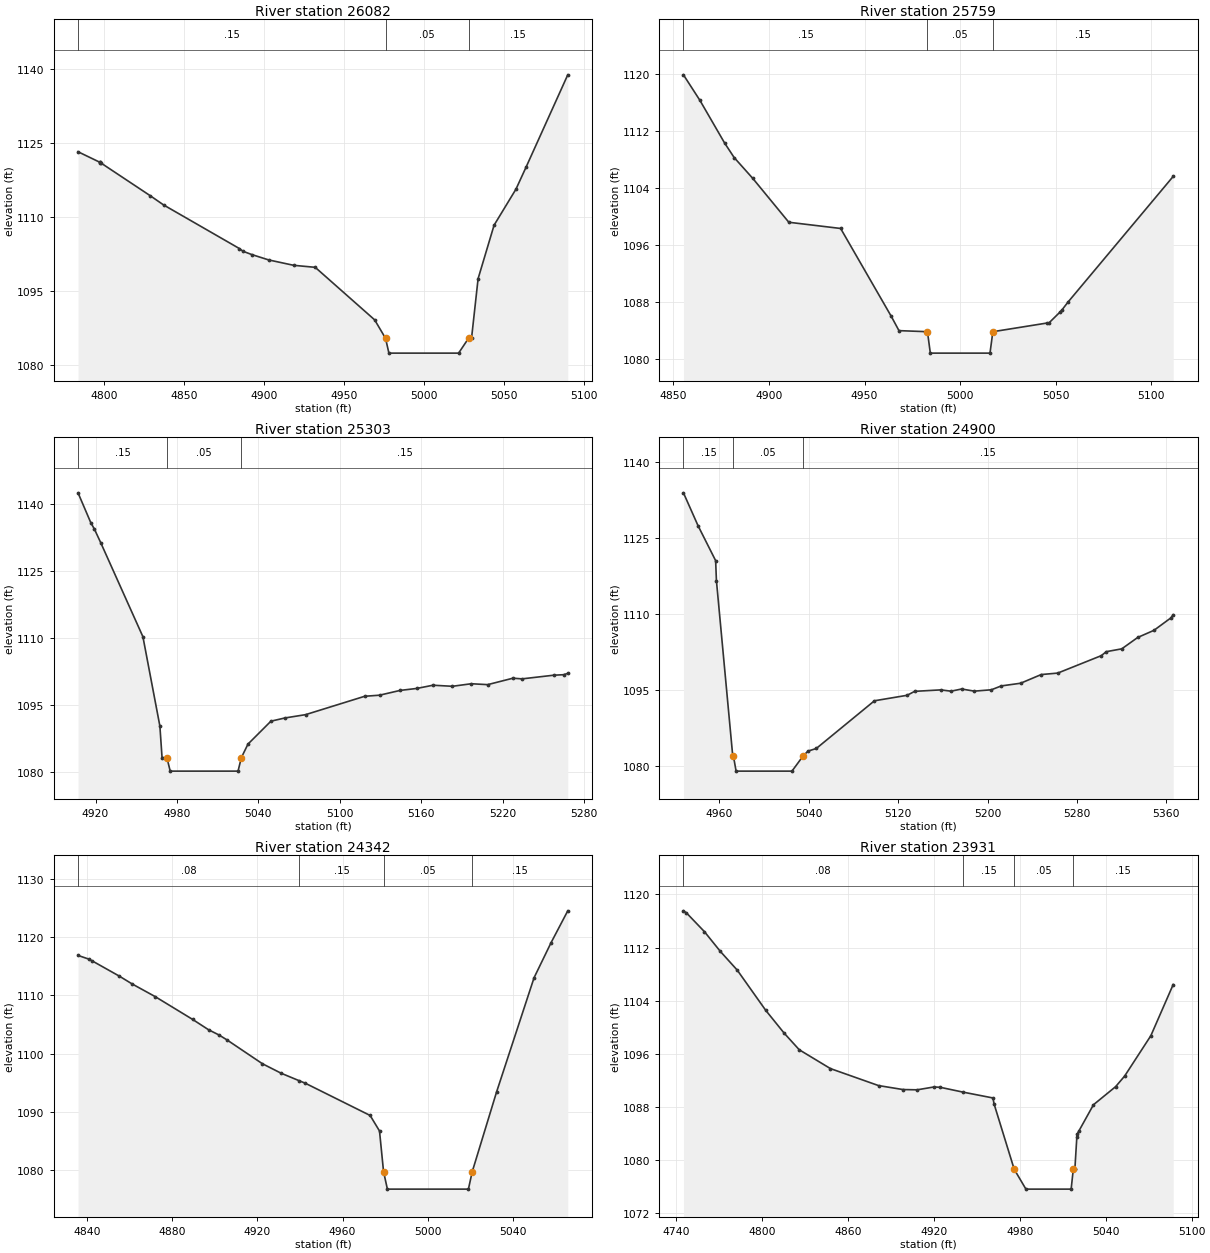
Type RM Length L Ch R = 1,26082,323,323,323
BEGIN DESCRIPTION:
South Fork 87.0
END DESCRIPTION:
XS GIS Cut Line= 3
      1455243.72       950846.53      1455069.26       950716.33
      1455001.54       950659.03
#Sta/Elev= 24
  4783.7 1123.19  4797.2 1121.08  4797.5 1121.03  4797.6 1121.00  4797.9 1120.94
  4828.8 1114.29  4837.2 1112.41  4884.7 1103.55  4886.9 1103.01  4892.4 1102.34
  4903.0 1101.25  4918.6 1100.16  4932.1 1099.75  4969.3 1089.09  4976.1 1085.35
  4978.2 1082.35  5021.8 1082.35  5028.0 1085.35  5029.9 1085.38  5034.0 1097.45
  5044.0 1108.30  5057.7 1115.61  5064.1 1120.13  5090.1 1138.79
#Mann=3,-1,0
  4783.7    0.15       0  4976.1    0.05       0  5028.0    0.15       0
Bank Sta=4976.1,5028
XS Rating Curve= 0
Exp/Cntr=0.3,0.1

Type RM Length L Ch R = 1,25759,456,456,456
BEGIN DESCRIPTION:
South Fork 86.0
END DESCRIPTION:
XS GIS Cut Line= 3
      1455407.77       950606.93      1455308.84       950502.79
      1455233.32       950419.46
#Sta/Elev= 19
  4855.3 1119.83  4863.9 1116.26  4876.8 1110.29  4881.8 1108.25  4891.6 1105.31
  4910.4 1099.18  4937.5 1098.31  4964.0 1085.99  4968.0 1084.00  4982.9 1083.85
  4984.4 1080.85  5015.6 1080.85  5017.1 1083.85  5045.3 1085.06  5046.4 1085.07
  5052.1 1086.57  5053.2 1086.89  5056.4 1088.00  5111.4 1105.60
#Mann=3,-1,0
  4855.3    0.15       0  4982.9    0.05       0  5017.1    0.15       0
Bank Sta=4982.9,5017.1
XS Rating Curve= 0
Exp/Cntr=0.3,0.1

Type RM Length L Ch R = 1,25303,403,403,403
BEGIN DESCRIPTION:
South Fork 85.0
END DESCRIPTION:
XS GIS Cut Line= 3
      1455712.52       950190.29      1455634.36       950185.08
      1455353.09       950159.04
#Sta/Elev= 28
  4907.1 1142.40  4916.5 1135.73  4919.1 1134.33  4923.8 1131.27  4954.9 1110.24
  4967.4 1090.28  4969.0 1083.24  4972.6 1083.20  4975.0 1080.20  5025.0 1080.20
  5027.4 1083.20  5032.3 1086.24  5049.2 1091.36  5059.5 1092.08  5074.7 1092.82
  5118.3 1096.93  5129.2 1097.17  5144.4 1098.24  5156.7 1098.68  5168.6 1099.40
  5182.9 1099.16  5196.8 1099.73  5208.9 1099.53  5227.5 1100.97  5234.2 1100.82
  5257.6 1101.64  5264.8 1101.75  5267.9 1102.04
#Mann=3,-1,0
  4907.1    0.15       0  4972.6    0.05       0  5027.4    0.15       0
Bank Sta=4972.6,5027.4
XS Rating Curve= 0
Exp/Cntr=0.3,0.1

Type RM Length L Ch R = 1,24900,558,558,558
BEGIN DESCRIPTION:
South Fork 83.0
END DESCRIPTION:
XS GIS Cut Line= 3
      1455694.30       949784.04      1455622.21       949785.49
      1455256.77       949807.47
#Sta/Elev= 30
  4927.9 1133.85  4941.0 1127.35  4956.7 1120.48  4957.4 1116.56  4971.9 1082.22
  4972.6 1081.98  4975.0 1078.98  5025.0 1078.98  5035.0 1081.98  5039.3 1082.92
  5046.8 1083.45  5098.8 1092.85  5128.0 1093.93  5134.8 1094.71  5158.2 1095.00
  5167.3 1094.74  5176.8 1095.17  5188.2 1094.75  5203.4 1095.02  5212.3 1095.78
  5229.6 1096.31  5248.0 1098.02  5262.8 1098.31  5301.8 1101.75  5306.2 1102.53
  5320.1 1103.09  5334.4 1105.34  5348.9 1106.74  5363.9 1109.17  5366.1 1109.81
#Mann=3,-1,0
  4927.9    0.15       0  4972.6    0.05       0  5035.0    0.15       0
Bank Sta=4972.6,5035
XS Rating Curve= 0
Exp/Cntr=0.3,0.1

Type RM Length L Ch R = 1,24342,411,411,411
BEGIN DESCRIPTION:
South Fork 81.0
END DESCRIPTION:
XS GIS Cut Line= 3
      1455853.13       949476.79      1455774.98       949333.52
      1455741.15       949276.26
#Sta/Elev= 24
  4835.9 1116.84  4841.0 1116.20  4842.3 1115.95  4855.2 1113.30  4861.3 1111.94
  4872.0 1109.79  4889.6 1105.87  4897.1 1104.09  4902.0 1103.19  4905.7 1102.36
  4922.4 1098.25  4931.2 1096.62  4939.7 1095.33  4942.5 1094.91  4972.9 1089.38
  4977.3 1086.72  4979.2 1079.74  4981.0 1076.74  5019.0 1076.74  5020.8 1079.74
  5032.2 1093.40  5049.8 1113.02  5057.8 1119.05  5065.6 1124.49
#Mann=4,-1,0
  4835.9    0.08       0  4939.7    0.15       0  4979.2    0.05       0
  5020.8    0.15       0
Bank Sta=4979.2,5020.8
XS Rating Curve= 0
Exp/Cntr=0.3,0.1

Type RM Length L Ch R = 1,23931,697,697,697
BEGIN DESCRIPTION:
South Fork 80.0
END DESCRIPTION:
XS GIS Cut Line= 3
      1456176.03       949356.92      1456191.65       949221.54
      1456074.44       949052.23
#Sta/Elev= 30
  4744.9 1117.53  4747.0 1117.22  4759.6 1114.38  4770.7 1111.41  4782.5 1108.59
  4802.4 1102.53  4815.2 1099.11  4825.8 1096.59  4847.6 1093.75  4881.2 1091.19
  4898.3 1090.59  4908.2 1090.55  4920.0 1090.98  4924.3 1090.93  4940.3 1090.20
  4961.2 1089.32  4961.9 1088.45  4976.0 1078.58  4984.2 1075.58  5015.8 1075.58
  5017.3 1078.58  5018.4 1078.60  5019.8 1083.49  5020.0 1083.86  5021.3 1084.38
  5031.4 1088.30  5046.9 1091.03  5053.2 1092.63  5071.5 1098.71  5087.1 1106.42
#Mann=4,-1,0
  4744.9    0.08       0  4940.3    0.15       0  4976.0    0.05       0
  5017.3    0.15       0
Bank Sta=4976,5017.3
XS Rating Curve= 0
Exp/Cntr=0.3,0.1

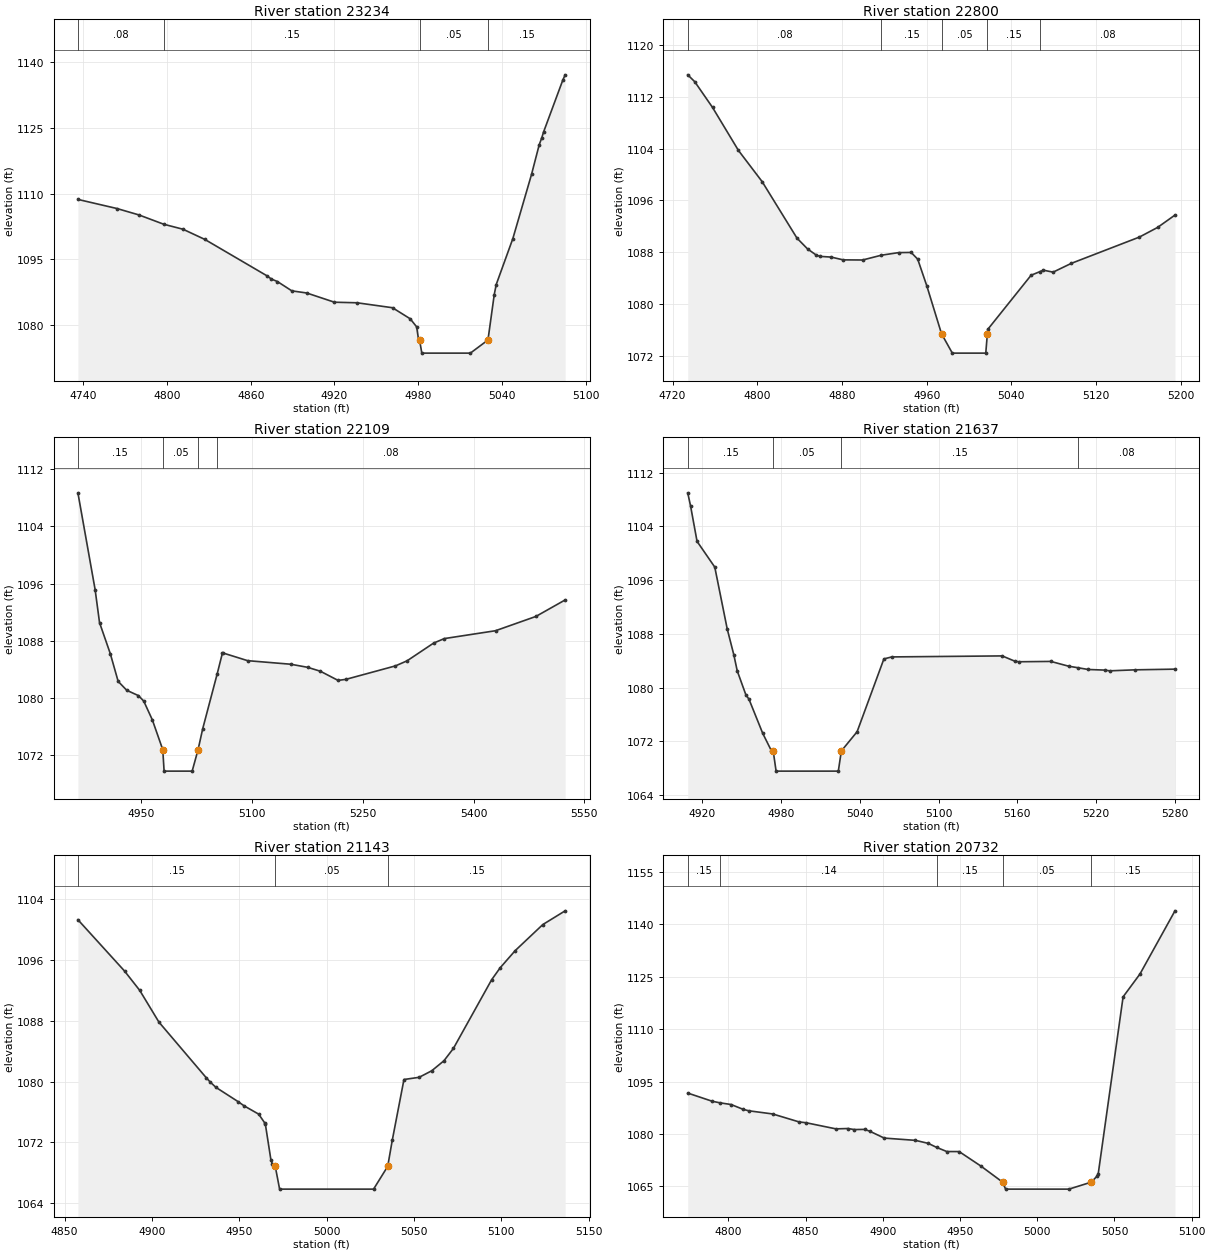
Type RM Length L Ch R = 1,23234,434,434,434
BEGIN DESCRIPTION:
South Fork 78.0
END DESCRIPTION:
XS GIS Cut Line= 3
      1456498.92       949234.58      1456605.71       949156.43
      1456795.81       949052.27
#Sta/Elev= 30
  4736.2 1108.67  4764.2 1106.59  4779.9 1105.13  4797.8 1102.99  4811.5 1101.86
  4827.1 1099.54  4871.4 1091.27  4874.9 1090.47  4879.1 1089.92  4889.5 1087.78
  4900.1 1087.30  4920.0 1085.19  4936.2 1085.06  4961.6 1083.93  4974.3 1081.40
  4978.9 1079.56  4980.3 1076.56  4981.0 1076.56  4982.6 1073.56  5017.4 1073.56
  5030.0 1076.56  5034.5 1086.93  5035.9 1089.22  5047.8 1099.70  5061.2 1114.37
  5066.7 1121.14  5068.6 1122.79  5069.8 1124.04  5083.6 1135.91  5085.3 1137.13
#Mann=4,-1,0
  4736.2    0.08       0  4797.8    0.15       0  4981.0    0.05       0
  5030.0    0.15       0
Bank Sta=4981,5030
XS Rating Curve= 0
Exp/Cntr=0.3,0.1

Type RM Length L Ch R = 1,22800,691,691,691
BEGIN DESCRIPTION:
South Fork 76.0
END DESCRIPTION:
XS GIS Cut Line= 5
      1456324.43       949403.83      1456402.50       949401.43
      1456575.87       949473.07      1456646.44       949510.04
      1456746.30       949453.33
#Sta/Elev= 30
  4734.3 1115.43  4740.9 1114.37  4757.7 1110.39  4782.2 1103.73  4804.6 1098.90
  4837.5 1090.16  4847.5 1088.49  4855.6 1087.55  4859.3 1087.34  4869.8 1087.23
  4881.1 1086.80  4899.5 1086.78  4917.2 1087.52  4933.4 1087.92  4945.3 1087.95
  4951.5 1086.91  4960.1 1082.78  4974.0 1075.37  4984.2 1072.37  5015.8 1072.37
  5017.3 1075.37  5017.6 1076.03  5058.6 1084.42  5067.1 1084.99  5070.3 1085.20
  5079.4 1084.90  5096.6 1086.26  5160.8 1090.32  5178.0 1091.81  5194.5 1093.73
#Mann=5,-1,0
  4734.3    0.08       0  4917.2    0.15       0  4974.0    0.05       0
  5017.3    0.15       0  5067.1    0.08       0
Bank Sta=4974,5017.3
XS Rating Curve= 0
Exp/Cntr=0.3,0.1

Type RM Length L Ch R = 1,22109,472,472,472
BEGIN DESCRIPTION:
South Fork 74.0
END DESCRIPTION:
XS GIS Cut Line= 3
      1456681.23       950127.82      1456694.26       949997.58
      1456769.77       949474.19
#Sta/Elev= 30
  4864.3 1108.70  4887.6 1095.16  4893.6 1090.53  4908.2 1086.18  4918.8 1082.31
  4930.5 1081.06  4946.2 1080.32  4953.4 1079.56  4965.1 1076.92  4979.2 1072.75
  4981.0 1069.75  5019.0 1069.75  5027.0 1072.75  5033.3 1075.69  5052.7 1083.29
  5060.0 1086.29  5060.6 1086.29  5094.1 1085.21  5152.5 1084.71  5175.3 1084.28
  5192.6 1083.73  5216.5 1082.45  5227.0 1082.59  5294.3 1084.48  5310.0 1085.19
  5345.9 1087.67  5360.4 1088.30  5429.7 1089.40  5484.4 1091.40  5524.0 1093.71
#Mann=4,-1,0
  4864.3    0.15       0  4979.2    0.05       0  5027.0    0.15       0
  5052.7    0.08       0
Bank Sta=4979.2,5027
XS Rating Curve= 0
Exp/Cntr=0.3,0.1

Type RM Length L Ch R = 1,21637,494,494,494
BEGIN DESCRIPTION:
South Fork 72.0
END DESCRIPTION:
XS GIS Cut Line= 3
      1457207.30       949849.14      1456946.86       949825.70
      1456837.53       949817.89
#Sta/Elev= 29
  4909.0 1108.98  4911.2 1106.99  4916.1 1101.76  4929.6 1097.93  4939.1 1088.71
  4944.1 1084.89  4946.7 1082.50  4953.3 1078.92  4955.6 1078.30  4966.1 1073.21
  4972.8 1070.58  4974.1 1070.58  4976.3 1067.58  5023.7 1067.58  5026.0 1070.58
  5038.0 1073.44  5058.4 1084.27  5064.4 1084.57  5148.5 1084.72  5158.3 1083.92
  5161.1 1083.85  5185.5 1083.90  5199.1 1083.19  5206.2 1082.96  5214.0 1082.70
  5226.5 1082.61  5230.4 1082.50  5249.9 1082.65  5280.1 1082.75
#Mann=4,-1,0
  4909.0    0.15       0  4974.1    0.05       0  5026.0    0.15       0
  5206.2    0.08       0
Bank Sta=4974.1,5026
XS Rating Curve= 0
Exp/Cntr=0.3,0.1

Type RM Length L Ch R = 1,21143,411,411,411
BEGIN DESCRIPTION:
South Fork 71.0
END DESCRIPTION:
XS GIS Cut Line= 3
      1457077.08       949409.04      1456970.30       949401.23
      1456798.38       949398.62
#Sta/Elev= 30
  4857.6 1101.33  4884.3 1094.57  4893.0 1092.02  4904.0 1087.84  4931.1 1080.51
  4933.4 1079.94  4936.6 1079.25  4949.5 1077.34  4952.7 1076.82  4961.1 1075.72
  4964.7 1074.52  4964.9 1074.45  4968.1 1069.72  4968.9 1069.17  4970.0 1068.85
  4970.6 1068.84  4973.1 1065.84  5026.9 1065.84  5035.0 1068.84  5037.6 1072.27
  5044.3 1080.28  5053.0 1080.57  5060.2 1081.43  5067.2 1082.75  5072.6 1084.37
  5094.5 1093.42  5099.4 1095.00  5108.0 1097.26  5123.8 1100.69  5136.6 1102.50
#Mann=3,-1,0
  4857.6    0.15       0  4970.6    0.05       0  5035.0    0.15       0
Bank Sta=4970.6,5035
XS Rating Curve= 0
Exp/Cntr=0.3,0.1

Type RM Length L Ch R = 1,20732,161,161,161
BEGIN DESCRIPTION:
South Fork 69.0
END DESCRIPTION:
XS GIS Cut Line= 3
      1457261.96       949226.74      1457116.13       949054.87
      1457053.66       948989.80
#Sta/Elev= 30
  4773.6 1091.71  4789.5 1089.36  4794.6 1088.91  4801.7 1088.43  4809.5 1087.05
  4813.1 1086.64  4828.6 1085.73  4845.8 1083.44  4850.2 1083.22  4869.6 1081.46
  4877.4 1081.56  4881.5 1081.26  4888.1 1081.31  4891.4 1080.81  4900.9 1078.82
  4921.1 1078.17  4929.4 1077.31  4934.8 1076.16  4941.4 1074.97  4949.4 1074.96
  4963.5 1070.81  4977.5 1066.23  4979.5 1064.21  5020.5 1064.21  5035.0 1066.21
  5038.7 1067.92  5039.5 1068.63  5055.6 1119.26  5066.5 1125.78  5089.2 1143.88
#Mann=5,-1,0
  4773.6    0.15       0  4794.6    0.14       0  4934.8    0.15       0
  4977.5    0.05       0  5035.0    0.15       0
Bank Sta=4977.5,5035
XS Rating Curve= 0
Exp/Cntr=0.3,0.1