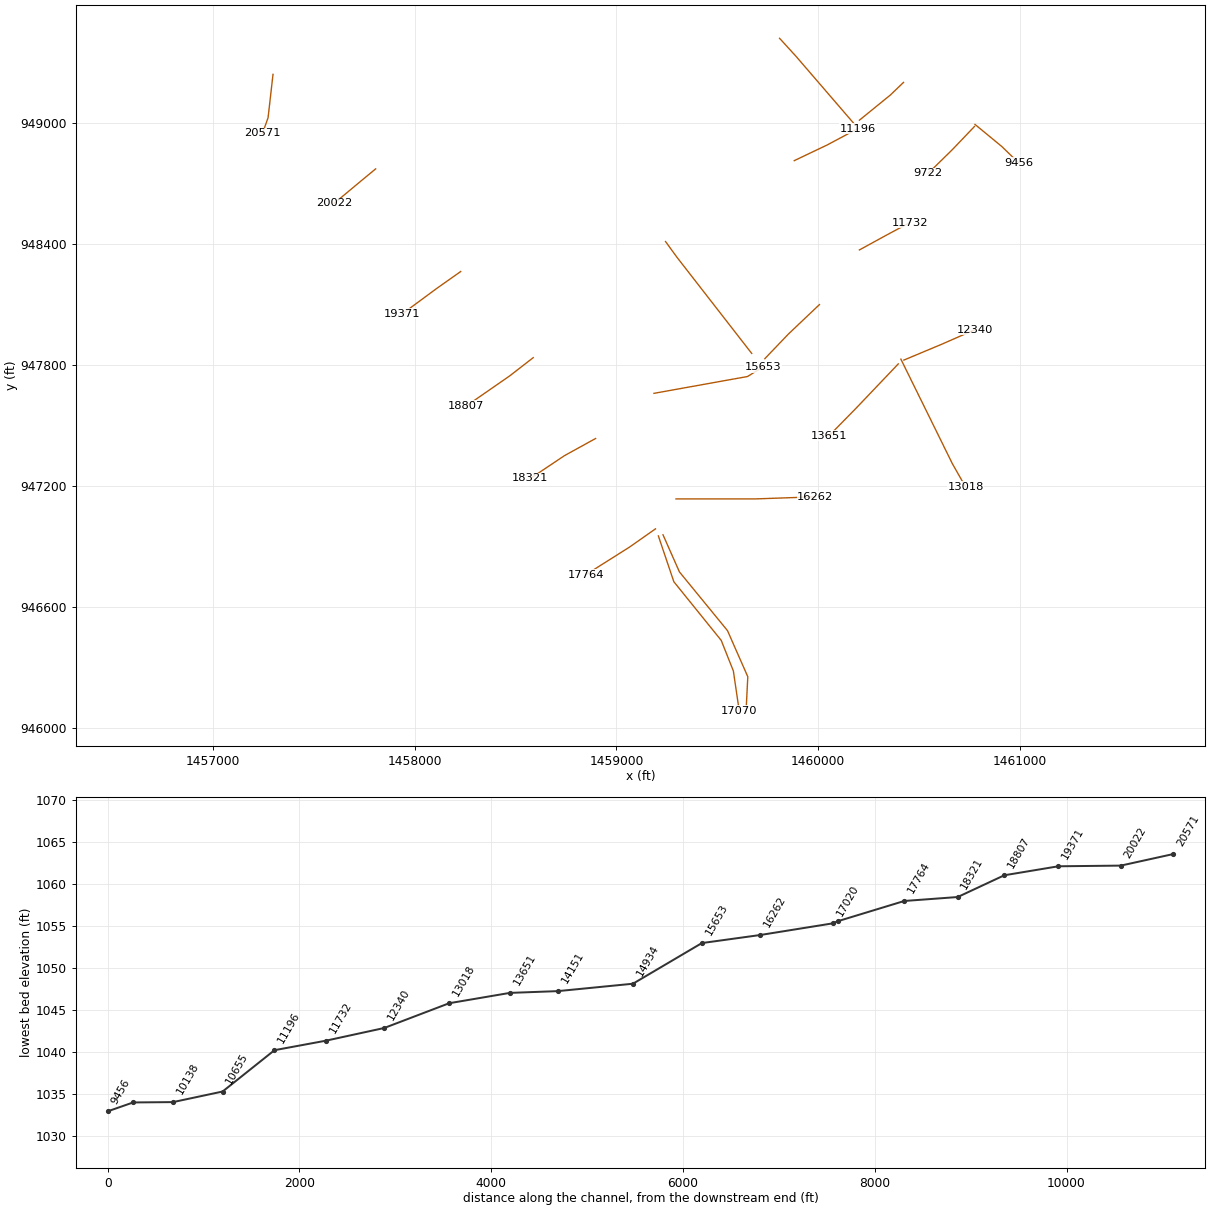
HEC-RAS study South Fork.prj: South Fork Limited Detail Study

--- South Fork.g01 (geometry) --- (continued)

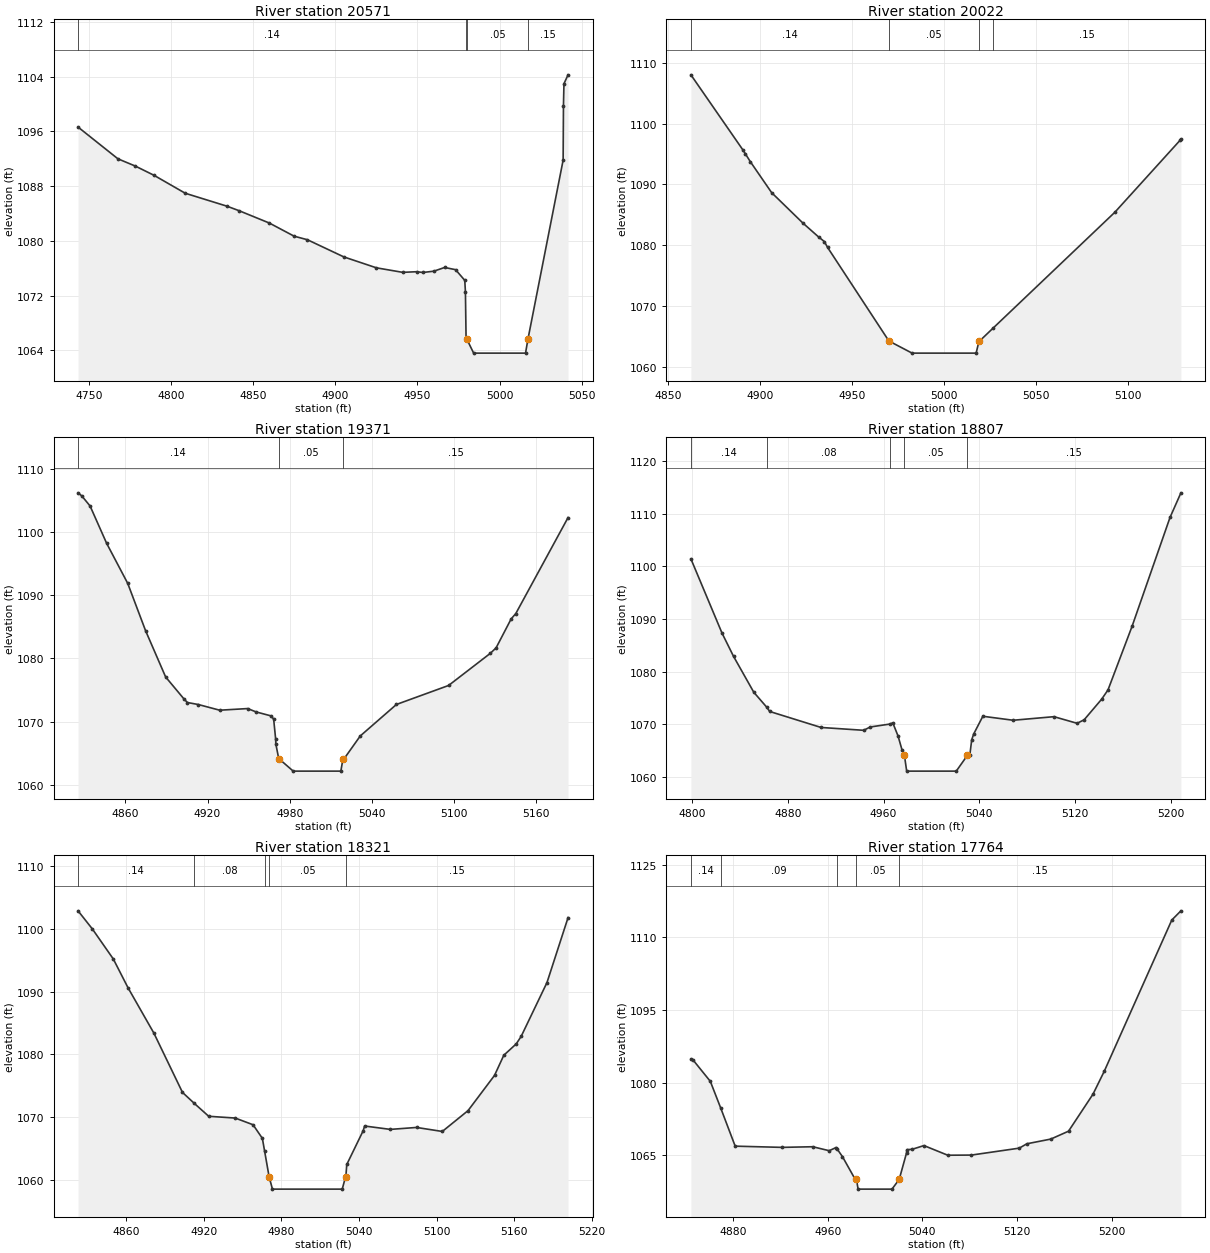
Type RM Length L Ch R = 1,20571,549,549,549
BEGIN DESCRIPTION:
South Fork 68.0
END DESCRIPTION:
XS GIS Cut Line= 3
      1457297.87       949241.73      1457273.31       949026.33
      1457245.77       948949.52
#Sta/Elev= 30
  4743.3 1096.62  4767.6 1091.98  4778.2 1090.92  4789.6 1089.57  4808.6 1086.95
  4833.9 1085.07  4841.3 1084.41  4859.8 1082.60  4874.9 1080.68  4883.0 1080.16
  4905.2 1077.65  4925.0 1076.06  4941.0 1075.40  4949.5 1075.49  4953.3 1075.38
  4960.0 1075.57  4966.5 1076.11  4973.2 1075.79  4978.8 1074.23  4979.2 1072.56
  4979.6 1065.68  4979.8 1065.68  4980.0 1065.67  4984.2 1063.60  5015.8 1063.60
  5017.3 1065.67  5038.7 1091.79  5038.9 1099.72  5039.2 1102.95  5041.7 1104.25
#Mann=4,-1,0
  4743.3    0.14       0  4979.8    0.15       0  4980.0    0.05       0
  5017.3    0.15       0
Bank Sta=4980,5017.3
XS Rating Curve= 0
Exp/Cntr=0.3,0.1

Type RM Length L Ch R = 1,20022,651,651,651
BEGIN DESCRIPTION:
South Fork 67.0
END DESCRIPTION:
XS GIS Cut Line= 3
      1457806.57       948773.00      1457737.11       948715.69
      1457601.71       948602.86
#Sta/Elev= 18
  4862.4 1108.05  4890.8 1095.62  4891.9 1095.09  4894.7 1093.75  4906.3 1088.64
  4923.3 1083.63  4931.8 1081.35  4934.9 1080.60  4936.7 1079.62  4970.0 1064.22
  4982.6 1062.22  5017.4 1062.22  5019.0 1064.22  5019.3 1064.22  5026.6 1066.33
  5092.8 1085.42  5128.3 1097.29  5128.7 1097.46
#Mann=4,-1,0
  4862.4    0.14       0  4970.0    0.05       0  5019.0    0.14       0
  5026.6    0.15       0
Bank Sta=4970,5019
XS Rating Curve= 0
Exp/Cntr=0.3,0.1

Type RM Length L Ch R = 1,19371,564,564,564
BEGIN DESCRIPTION:
South Fork 65.0
END DESCRIPTION:
XS GIS Cut Line= 3
      1458228.41       948264.29      1458110.37       948180.97
      1457938.52       948054.25
#Sta/Elev= 30
  4825.4 1106.27  4828.1 1105.79  4834.2 1104.18  4846.3 1098.26  4861.7 1091.91
  4874.7 1084.43  4889.4 1077.07  4903.0 1073.53  4905.3 1073.02  4913.3 1072.70
  4928.9 1071.80  4949.3 1072.06  4955.6 1071.52  4966.2 1070.91  4968.3 1070.41
  4969.8 1067.16  4969.9 1066.45  4972.0 1064.14  4982.6 1062.14  5017.4 1062.14
  5019.0 1064.14  5019.9 1064.14  5031.6 1067.72  5058.0 1072.71  5096.1 1075.72
  5126.5 1080.80  5130.8 1081.68  5141.8 1086.27  5145.2 1087.12  5183.4 1102.35
#Mann=3,-1,0
  4825.4    0.14       0  4972.0    0.05       0  5019.0    0.15       0
Bank Sta=4972,5019
XS Rating Curve= 0
Exp/Cntr=0.3,0.1

Type RM Length L Ch R = 1,18807,486,486,486
BEGIN DESCRIPTION:
South Fork 63.0
END DESCRIPTION:
XS GIS Cut Line= 3
      1458587.77       947837.20      1458471.48       947746.94
      1458256.20       947597.63
#Sta/Elev= 30
  4799.1 1101.42  4825.1 1087.30  4834.7 1082.89  4851.6 1076.07  4862.5 1073.20
  4864.9 1072.41  4907.8 1069.37  4943.4 1068.83  4948.8 1069.46  4965.4 1070.02
  4967.7 1070.25  4972.1 1067.74  4975.4 1065.11  4977.4 1064.07  4979.3 1061.07
  5020.7 1061.07  5030.0 1064.07  5032.0 1064.07  5033.6 1067.03  5035.3 1068.15
  5042.9 1071.50  5068.2 1070.74  5102.3 1071.42  5121.6 1070.16  5127.5 1070.83
  5142.1 1074.74  5147.4 1076.50  5167.5 1088.59  5199.2 1109.29  5208.3 1113.97
#Mann=5,-1,0
  4799.1    0.14       0  4862.5    0.08       0  4965.4    0.15       0
  4977.4    0.05       0  5030.0    0.15       0
Bank Sta=4977.4,5030
XS Rating Curve= 0
Exp/Cntr=0.3,0.1

Type RM Length L Ch R = 1,18321,557,557,557
BEGIN DESCRIPTION:
South Fork 61.0
END DESCRIPTION:
XS GIS Cut Line= 3
      1458896.86       947436.20      1458742.32       947351.11
      1458573.94       947238.28
#Sta/Elev= 30
  4822.6 1102.88  4833.7 1099.98  4849.9 1095.19  4861.3 1090.59  4881.3 1083.36
  4903.4 1073.91  4912.6 1072.15  4923.7 1070.10  4944.2 1069.82  4958.0 1068.75
  4965.2 1066.58  4966.9 1064.59  4970.4 1060.48  4973.0 1058.48  5027.0 1058.48
  5029.6 1060.48  5029.8 1060.48  5030.5 1062.41  5043.2 1067.80  5044.3 1068.55
  5064.2 1068.01  5084.5 1068.32  5104.4 1067.68  5124.3 1071.00  5144.8 1076.62
  5152.0 1079.84  5161.6 1081.65  5165.4 1082.84  5185.4 1091.44  5201.7 1101.80
#Mann=5,-1,0
  4822.6    0.14       0  4912.6    0.08       0  4966.9    0.15       0
  4970.4    0.05       0  5029.6    0.15       0
Bank Sta=4970.4,5029.6
XS Rating Curve= 0
Exp/Cntr=0.3,0.1

Type RM Length L Ch R = 1,17764,694,694,694
BEGIN DESCRIPTION:
South Fork 59.0
END DESCRIPTION:
XS GIS Cut Line= 3
      1459193.73       946988.28      1459065.23       946897.99
      1458848.19       946760.82
#Sta/Elev= 30
  4844.5 1084.79  4846.3 1084.68  4860.9 1080.26  4869.6 1074.80  4881.9 1066.88
  4921.5 1066.63  4947.4 1066.76  4961.3 1065.94  4967.1 1066.60  4967.8 1066.36
  4972.5 1064.71  4983.2 1060.05  4984.3 1060.01  4985.7 1058.01  5014.3 1058.01
  5020.4 1060.01  5026.6 1065.48  5026.8 1066.15  5031.3 1066.23  5041.3 1067.00
  5061.4 1065.01  5081.4 1065.04  5121.8 1066.47  5128.2 1067.37  5148.4 1068.34
  5163.4 1069.97  5184.1 1077.63  5193.6 1082.36  5250.6 1113.56  5258.3 1115.46
#Mann=5,-1,0
  4844.5    0.14       0  4869.6    0.09       0  4967.8    0.15       0
  4984.3    0.05       0  5020.4    0.15       0
Bank Sta=4984.3,5020.4
XS Rating Curve= 0
Exp/Cntr=0.5,0.3

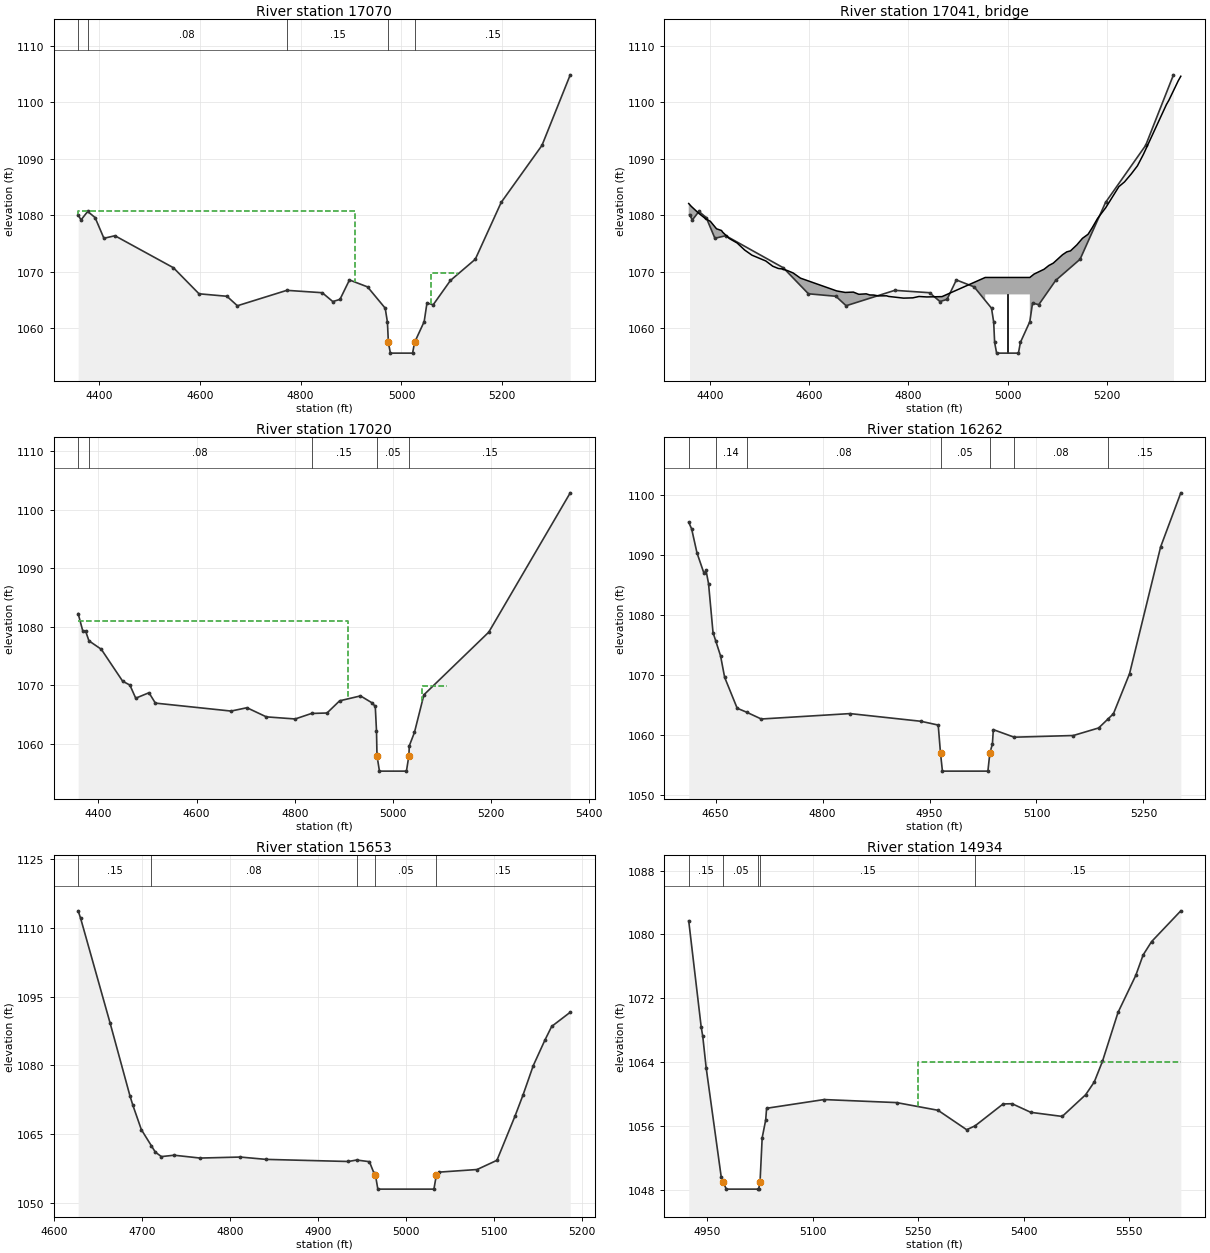
Type RM Length L Ch R = 1,17070,50,50,50
BEGIN DESCRIPTION:
Noah Hayes Rd US
END DESCRIPTION:
XS GIS Cut Line= 5
      1459208.09       946953.22      1459284.85       946726.11
      1459519.65       946435.40      1459579.75       946284.18
      1459608.83       946086.45
#Sta/Elev= 30
  4358.7 1080.11  4364.3 1079.18  4377.6 1080.69  4392.3 1079.61  4409.8 1075.94
  4431.7 1076.39  4547.7 1070.72  4598.4 1066.11  4653.8 1065.67  4674.5 1063.99
  4772.6 1066.72  4842.8 1066.30  4863.8 1064.73  4878.0 1065.12  4896.8 1068.56
  4932.7 1067.33  4967.7 1063.56  4972.1 1061.09  4974.0 1057.50  4978.0 1055.60
  5022.0 1055.60  5026.0 1057.50  5045.0 1061.18  5050.5 1064.46  5063.0 1064.18
  5097.1 1068.47  5146.4 1072.23  5197.7 1082.29  5278.6 1092.39  5334.7 1104.89
#Mann=5,-1,0
  4358.7    0.14       0  4377.6    0.08       0  4772.6    0.15       0
  4974.0    0.05       0  5026.0    0.15       0
#XS Ineff=3,-1
 4908.20 4940.50 1065.40 5059.50 5109.50 1069.87 4356.40 4908.10 1080.84
Permanent Ineff=
       F       F       F
Bank Sta=4974,5026
XS Rating Curve= 0
Exp/Cntr=0.5,0.3

Type RM Length L Ch R =3,17041,,,
BEGIN DESCRIPTION:
Noah Hayes Rd TOR
Structure ID: LDS_SFMR_01
Approximate Survey Structure
END DESCRIPTION:
Bridge Culvert--1,0,-1,-1,0
Deck Dist Width WeirC Skew NumUp NumDn MinLoCord MaxHiCord MaxSubmerge Is_Ogee
14.5,29,3,, 60, 60,,,0.95,0,1,1,,,
  4357.0  4362.1  4376.9  4391.0  4400.7  4413.1  4423.1  4425.7  4438.8  4454.6
  4469.8  4484.5  4512.5  4526.5  4537.8  4545.0  4556.4  4567.6  4582.4  4655.4
  4672.6  4689.1  4700.1  4715.0  4722.3  4730.0  4739.2  4756.1  4760.2  4790.5
  4809.0  4821.5  4837.2  4867.9  4955.0  4955.0  5045.0  5045.0  5053.5  5073.8
  5083.3  5092.3  5110.8  5119.6  5127.0  5139.8  5151.1  5162.4  5170.9  5181.6
  5198.1  5224.6  5236.0  5249.5  5262.0  5274.2  5320.6  5325.4  5344.3  5349.5
 1082.10 1081.60 1080.39 1079.41 1078.94 1077.62 1077.32 1077.00 1075.90 1075.11
 1073.86 1072.95 1071.92 1070.99 1070.59 1070.52 1070.21 1069.80 1068.88 1066.62
 1066.35 1066.41 1066.02 1066.10 1065.90 1065.89 1065.74 1065.75 1065.64 1065.34
 1065.39 1065.63 1065.55 1065.61 1069.00 1069.00 1069.00 1069.00 1069.60 1070.46
 1071.12 1071.54 1073.02 1073.54 1073.71 1074.77 1075.93 1076.65 1077.82 1079.45
 1081.36 1085.09 1085.93 1087.33 1088.77 1090.83 1099.65 1100.38 1103.83 1104.64
 1035.60 1035.60 1035.60 1035.60 1035.60 1035.60 1035.60 1035.60 1035.60 1035.60
 1035.60 1035.60 1035.60 1035.60 1035.60 1035.60 1035.60 1035.60 1035.60 1035.60
 1035.60 1035.60 1035.60 1035.60 1035.60 1035.60 1035.60 1035.60 1035.60 1035.60
 1035.60 1035.60 1035.60 1035.60 1035.60 1066.00 1066.00 1035.60 1035.60 1035.60
 1035.60 1035.60 1035.60 1035.60 1035.60 1035.60 1035.60 1035.60 1035.60 1035.60
 1035.60 1035.60 1035.60 1035.60 1035.60 1035.60 1035.60 1035.60 1035.60 1035.60
  4357.0  4362.1  4376.9  4391.0  4400.7  4413.1  4423.1  4425.7  4438.8  4454.6
  4469.8  4484.5  4512.5  4526.5  4537.8  4545.0  4556.4  4567.6  4582.4  4655.4
  4672.6  4689.1  4700.1  4715.0  4722.3  4730.0  4739.2  4756.1  4760.2  4790.5
  4809.0  4821.5  4837.2  4867.9  4955.0  4955.0  5045.0  5045.0  5053.5  5073.8
  5083.3  5092.3  5110.8  5119.6  5127.0  5139.8  5151.1  5162.4  5170.9  5181.6
  5198.1  5224.6  5236.0  5249.5  5262.0  5274.2  5320.6  5325.4  5344.3  5349.5
 1082.10 1081.60 1080.39 1079.41 1078.94 1077.62 1077.32 1077.00 1075.90 1075.11
 1073.86 1072.95 1071.92 1070.99 1070.59 1070.52 1070.21 1069.80 1068.88 1066.62
 1066.35 1066.41 1066.02 1066.10 1065.90 1065.89 1065.74 1065.75 1065.64 1065.34
 1065.39 1065.63 1065.55 1065.61 1069.00 1069.00 1069.00 1069.00 1069.60 1070.46
 1071.12 1071.54 1073.02 1073.54 1073.71 1074.77 1075.93 1076.65 1077.82 1079.45
 1081.36 1085.09 1085.93 1087.33 1088.77 1090.83 1099.65 1100.38 1103.83 1104.64
 1035.60 1035.60 1035.60 1035.60 1035.60 1035.60 1035.60 1035.60 1035.60 1035.60
 1035.60 1035.60 1035.60 1035.60 1035.60 1035.60 1035.60 1035.60 1035.60 1035.60
 1035.60 1035.60 1035.60 1035.60 1035.60 1035.60 1035.60 1035.60 1035.60 1035.60
 1035.60 1035.60 1035.60 1035.60 1035.60 1066.00 1066.00 1035.60 1035.60 1035.60
 1035.60 1035.60 1035.60 1035.60 1035.60 1035.60 1035.60 1035.60 1035.60 1035.60
 1035.60 1035.60 1035.60 1035.60 1035.60 1035.60 1035.60 1035.60 1035.60 1035.60
Pier Skew, UpSta & Num, DnSta & Num=,5000,2,5000,2,0,0,0,0,0
       3       3
 1055.60 1066.00
       3       3
 1055.35 1066.00
Abutment Skew #Up #Dn=,2,2
  4955.0  4961.0
 1066.00 1063.92
  4955.0  4961.0
 1066.00 1066.68
Abutment Skew #Up #Dn=,2,2
  5039.1  5045.0
 1062.15 1066.00
  5039.1  5045.0
 1060.91 1066.00
BR Coef=1,1,0,1.25,0,,,0.8,0,2,0,
WSPro=,,,, 1 ,,,, 0 ,,,, 0 ,,,,-1 ,-1 ,-1 , 0 , 0 , 0 , 0 , 0
BC Design=,,0,,0,,,,,,

Type RM Length L Ch R = 1,17020,758,758,758
BEGIN DESCRIPTION:
Noah Hayes Rd DS
END DESCRIPTION:
XS GIS Cut Line= 5
      1459230.93       946959.04      1459312.63       946774.72
      1459550.67       946483.87      1459651.48       946255.10
      1459642.49       946080.28
#Sta/Elev= 30
  4358.7 1082.26  4368.2 1079.28  4374.1 1079.21  4380.7 1077.61  4405.9 1076.16
  4449.4 1070.71  4464.1 1070.05  4476.0 1067.81  4503.0 1068.74  4516.0 1066.97
  4670.2 1065.61  4702.6 1066.18  4742.1 1064.62  4800.8 1064.26  4834.1 1065.20
  4865.7 1065.28  4891.4 1067.36  4933.9 1068.20  4957.5 1067.01  4964.0 1066.40
  4966.5 1062.23  4967.5 1058.00  4972.5 1055.35  5027.5 1055.35  5032.5 1058.00
  5033.3 1059.67  5043.8 1061.96  5063.1 1068.39  5195.2 1079.09  5361.2 1102.89
#Mann=5,-1,0
  4358.7    0.14       0  4380.7    0.08       0  4834.1    0.15       0
  4967.5    0.05       0  5032.5    0.15       0
#XS Ineff=3,-1
 4908.20 4950.00 1064.81 5059.50 5109.50 1069.87 4355.00 4908.10 1081.03
Permanent Ineff=
       F       F       F
Bank Sta=4967.5,5032.5
XS Rating Curve= 0
Exp/Cntr=0.5,0.3

Type RM Length L Ch R = 1,16262,609,609,609
BEGIN DESCRIPTION:
South Fork 54.0
END DESCRIPTION:
XS GIS Cut Line= 3
      1459295.75       947136.79      1459688.99       947136.79
      1459985.87       947147.20
#Sta/Elev= 30
  4612.2 1095.40  4616.3 1094.30  4623.8 1090.30  4633.7 1086.87  4636.5 1087.37
  4640.0 1085.20  4646.3 1077.04  4650.0 1075.68  4656.9 1073.14  4662.6 1069.58
  4680.2 1064.43  4693.3 1063.78  4714.0 1062.64  4838.5 1063.54  4938.0 1062.26
  4962.2 1061.63  4965.4 1056.96  4968.1 1053.96  5031.9 1053.96  5034.6 1056.96
  5038.2 1058.46  5039.5 1060.87  5068.7 1059.61  5151.7 1059.89  5187.3 1061.15
  5200.6 1062.67  5208.0 1063.52  5230.6 1070.19  5274.2 1091.30  5302.5 1100.30
#Mann=7,-1,0
  4612.2    0.14       0  4650.0    0.14       0  4693.3    0.08       0
  4965.4    0.05       0  5034.6    0.08       0  5068.7    0.08       0
  5200.6    0.15       0
Bank Sta=4965.4,5034.6
XS Rating Curve= 0
Exp/Cntr=0.3,0.1

Type RM Length L Ch R = 1,15653,719,719,719
BEGIN DESCRIPTION:
South Fork 52.0
END DESCRIPTION:
XS GIS Cut Line= 3
      1459186.35       947660.22      1459649.93       947743.56
      1459725.45       947790.43
#Sta/Elev= 30
  4627.1 1113.73  4629.9 1112.11  4663.4 1089.28  4686.1 1073.32  4689.4 1071.28
  4699.0 1065.99  4710.5 1062.44  4714.9 1061.08  4721.8 1060.10  4736.3 1060.40
  4765.8 1059.78  4811.6 1060.00  4841.0 1059.49  4934.4 1059.03  4944.0 1059.35
  4958.5 1058.99  4963.7 1056.48  4965.4 1056.00  4968.1 1053.00  5031.9 1053.00
  5034.6 1056.00  5037.8 1056.71  5081.0 1057.28  5103.6 1059.29  5124.3 1069.01
  5133.3 1073.56  5144.9 1079.94  5158.1 1085.49  5165.9 1088.51  5187.0 1091.60
#Mann=5,-1,0
  4627.1    0.15       0  4710.5    0.08       0  4944.0    0.15       0
  4965.4    0.05       0  5034.6    0.15       0
Bank Sta=4965.4,5034.6
XS Rating Curve= 0
Exp/Cntr=0.3,0.1

Type RM Length L Ch R = 1,14934,783,783,783
BEGIN DESCRIPTION:
South Fork 50.0
END DESCRIPTION:
XS GIS Cut Line= 3
      1459243.68       948412.82      1459298.37       948337.31
      1459670.70       947858.22
#Sta/Elev= 30
  4923.5 1081.72  4941.2 1068.47  4943.5 1067.25  4948.3 1063.35  4969.8 1049.64
  4972.1 1049.10  4977.0 1048.16  5021.8 1048.16  5023.0 1048.16  5025.0 1049.10
  5028.0 1054.58  5033.0 1056.80  5034.3 1058.27  5116.0 1059.36  5219.3 1058.98
  5278.1 1058.02  5318.9 1055.59  5330.8 1056.07  5370.7 1058.81  5383.5 1058.84
  5410.2 1057.76  5454.8 1057.25  5488.1 1059.96  5500.4 1061.56  5512.0 1064.13
  5534.2 1070.26  5559.4 1074.88  5569.9 1077.44  5581.9 1079.11  5623.5 1082.96
#Mann=5,-1,0
  4923.5    0.15       0  4972.1    0.05       0  5021.8    0.08       0
  5025.0    0.15       0  5330.8    0.15       0
#XS Ineff=2,0
       0                 5250.00    0.00 1064.00
Permanent Ineff=
       F       F
Bank Sta=4972.1,5025
XS Rating Curve= 0
Exp/Cntr=0.3,0.1

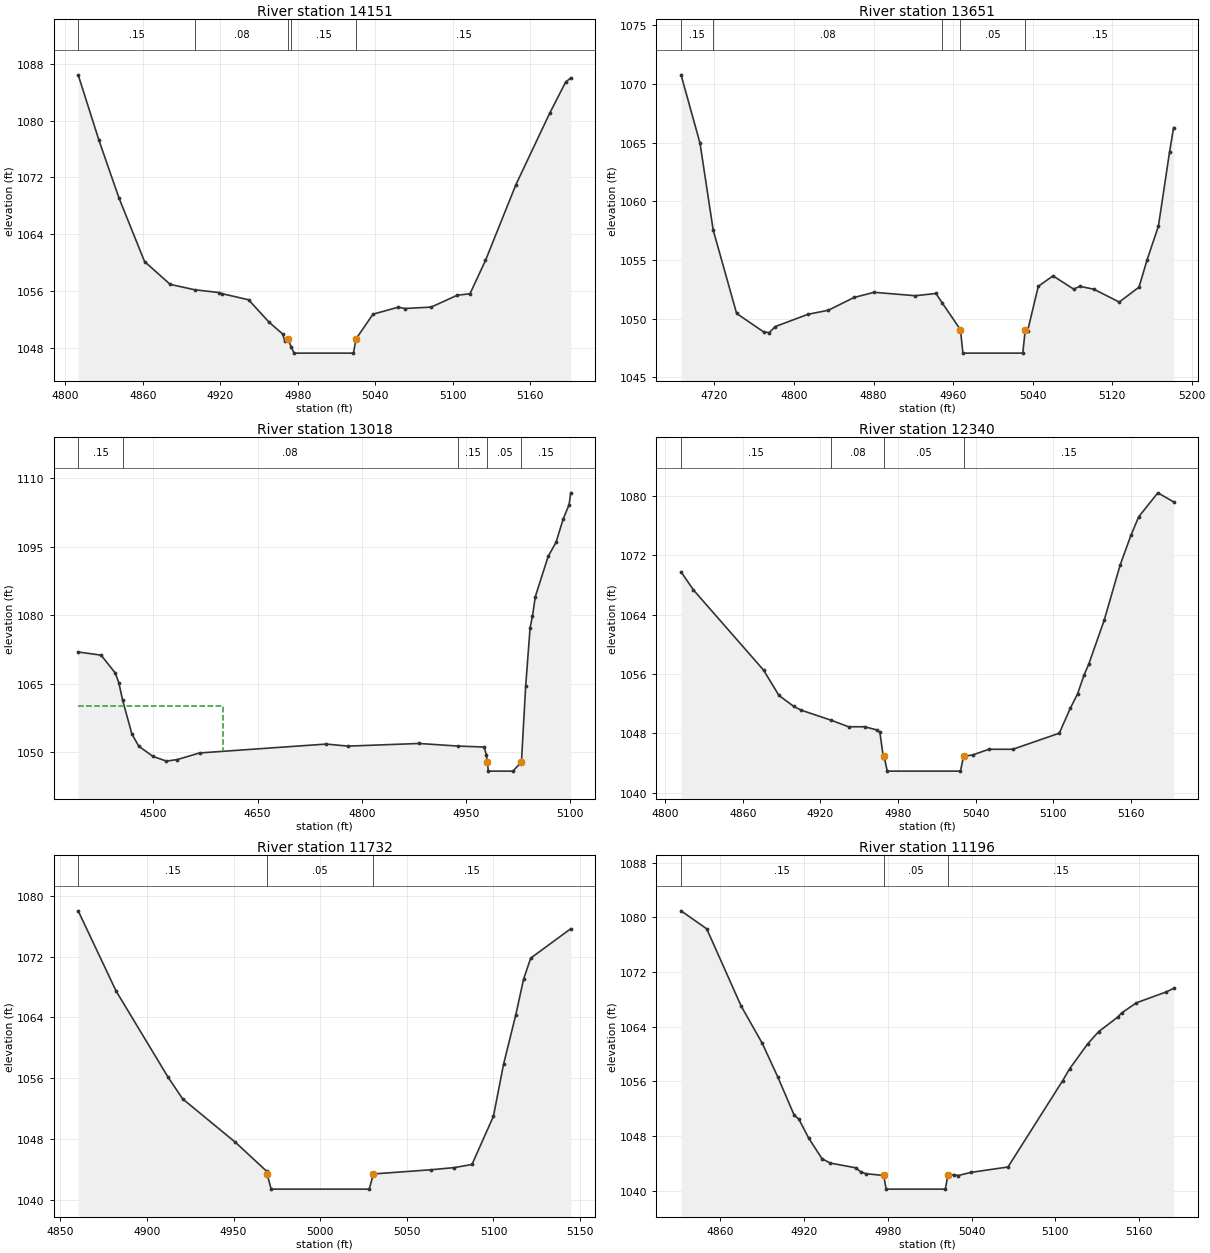
Type RM Length L Ch R = 1,14151,500,500,500
BEGIN DESCRIPTION:
South Fork 47.0
END DESCRIPTION:
XS GIS Cut Line= 3
      1460006.68       948100.31      1459853.05       947954.50
      1459735.84       947832.07
#Sta/Elev= 28
  4809.9 1086.45  4826.0 1077.23  4841.6 1069.06  4861.3 1060.17  4881.1 1056.96
  4900.3 1056.19  4918.8 1055.81  4921.2 1055.65  4941.8 1054.79  4957.8 1051.61
  4968.1 1049.99  4969.8 1049.03  4972.1 1049.28  4974.8 1048.18  4977.0 1047.28
  5023.0 1047.28  5025.0 1049.28  5038.1 1052.76  5057.8 1053.75  5062.7 1053.56
  5083.2 1053.76  5103.2 1055.42  5113.2 1055.64  5125.2 1060.32  5148.8 1071.01
  5174.9 1081.04  5187.2 1085.41  5191.2 1086.02
#Mann=5,-1,0
  4809.9    0.15       0  4900.3    0.08       0  4972.1    0.05       0
  4974.8    0.15       0  5025.0    0.15       0
Bank Sta=4972.1,5025
XS Rating Curve= 0
Exp/Cntr=0.3,0.1

Type RM Length L Ch R = 1,13651,633,633,633
BEGIN DESCRIPTION:
South Fork 46.0
END DESCRIPTION:
XS GIS Cut Line= 3
      1460397.32       947806.05      1460188.99       947587.31
      1460053.59       947449.31
#Sta/Elev= 30
  4686.4 1070.77  4705.5 1064.94  4718.7 1057.56  4742.3 1050.45  4769.6 1048.87
  4775.2 1048.82  4781.1 1049.33  4814.2 1050.38  4834.5 1050.72  4860.4 1051.81
  4880.6 1052.25  4921.9 1051.96  4942.8 1052.15  4948.8 1051.38  4967.4 1049.07
  4969.9 1047.07  5030.1 1047.07  5032.6 1049.07  5035.0 1048.98  5045.7 1052.76
  5060.5 1053.65  5081.3 1052.52  5087.4 1052.76  5101.7 1052.51  5127.1 1051.42
  5147.0 1052.69  5155.0 1054.98  5166.5 1057.88  5177.7 1064.19  5181.8 1066.28
#Mann=5,-1,0
  4686.4    0.15       0  4718.7    0.08       0  4948.8    0.15       0
  4967.4    0.05       0  5032.6    0.15       0
Bank Sta=4967.4,5032.6
XS Rating Curve= 0
Exp/Cntr=0.3,0.1

Type RM Length L Ch R = 1,13018,678,678,678
BEGIN DESCRIPTION:
South Fork 44.0
END DESCRIPTION:
XS GIS Cut Line= 3
      1460410.35       947829.48      1460665.55       947311.27
      1460730.64       947196.71
#Sta/Elev= 30
  4391.6 1071.94  4424.6 1071.25  4444.9 1067.36  4450.1 1065.25  4455.6 1061.39
  4469.0 1053.97  4478.9 1051.30  4499.5 1049.05  4518.6 1048.04  4534.0 1048.36
  4566.4 1049.82  4748.8 1051.77  4780.2 1051.32  4882.6 1051.90  4938.5 1051.33
  4976.2 1051.12  4979.5 1049.42  4980.8 1047.84  4982.3 1045.84  5017.7 1045.84
  5030.0 1047.84  5036.1 1064.46  5042.5 1077.30  5045.9 1079.77  5050.0 1084.07
  5068.6 1092.92  5079.8 1095.96  5090.3 1101.15  5098.6 1104.20  5101.0 1106.81
#Mann=5,-1,0
  4391.6    0.15       0  4455.6    0.08       0  4938.5    0.15       0
  4980.8    0.05       0  5030.0    0.15       0
#XS Ineff=2,0
    0.00 4600.00 1060.00               0
Permanent Ineff=
       F       F
Bank Sta=4980.8,5030
XS Rating Curve= 0
Exp/Cntr=0.3,0.1

Type RM Length L Ch R = 1,12340,608,608,608
BEGIN DESCRIPTION:
South Fork 41.0
END DESCRIPTION:
XS GIS Cut Line= 3
      1460425.04       947825.02      1460616.07       947905.02
      1460775.03       947975.01
#Sta/Elev= 30
  4812.3 1069.79  4821.8 1067.36  4876.1 1056.52  4888.0 1053.10  4899.4 1051.63
  4905.1 1051.12  4928.2 1049.77  4941.8 1048.88  4954.2 1048.88  4963.7 1048.45
  4966.0 1048.15  4968.8 1044.65  4969.3 1044.89  4971.7 1042.89  5028.3 1042.89
  5030.7 1044.89  5037.7 1045.07  5050.3 1045.84  5068.8 1045.84  5104.7 1048.01
  5113.2 1051.36  5118.8 1053.30  5124.0 1055.93  5127.4 1057.29  5139.4 1063.24
  5151.8 1070.73  5160.1 1074.71  5166.1 1077.21  5180.9 1080.45  5193.1 1079.23
#Mann=4,-1,0
  4812.3    0.15       0  4928.2    0.08       0  4969.3    0.05       0
  5030.7    0.15       0
Bank Sta=4969.3,5030.7
XS Rating Curve= 0
Exp/Cntr=0.3,0.1

Type RM Length L Ch R = 1,11732,536,536,536
BEGIN DESCRIPTION:
South Fork 39.0
END DESCRIPTION:
XS GIS Cut Line= 3
      1460204.62       948371.17      1460342.64       948446.68
      1460454.60       948506.57
#Sta/Elev= 19
  4860.3 1078.04  4882.2 1067.47  4912.1 1056.16  4920.6 1053.27  4951.1 1047.54
  4969.2 1043.71  4969.3 1043.38  4971.7 1041.38  5028.3 1041.38  5030.7 1043.38
  5063.9 1043.93  5077.5 1044.22  5087.6 1044.63  5100.0 1050.99  5105.8 1057.80
  5112.9 1064.36  5117.4 1069.05  5121.5 1071.81  5144.6 1075.68
#Mann=3,-1,0
  4860.3    0.15       0  4969.3    0.05       0  5030.7    0.15       0
Bank Sta=4969.3,5030.7
XS Rating Curve= 0
Exp/Cntr=0.3,0.1

Type RM Length L Ch R = 1,11196,541,541,541
BEGIN DESCRIPTION:
South Fork 37.0
END DESCRIPTION:
XS GIS Cut Line= 3
      1459881.69       948813.87      1460045.76       948892.00
      1460196.82       948972.73
#Sta/Elev= 30
  4831.8 1080.96  4850.2 1078.33  4874.8 1067.06  4890.0 1061.58  4901.0 1056.72
  4912.9 1051.06  4916.2 1050.50  4923.3 1047.70  4932.8 1044.71  4938.6 1044.07
  4957.2 1043.36  4960.5 1042.78  4964.2 1042.51  4977.0 1042.25  4978.8 1040.25
  5021.2 1040.25  5023.0 1042.25  5027.1 1042.38  5030.3 1042.23  5039.3 1042.69
  5066.1 1043.49  5105.3 1056.12  5110.3 1057.86  5123.2 1061.50  5131.1 1063.29
  5144.8 1065.42  5147.5 1066.01  5158.1 1067.50  5179.5 1069.10  5184.8 1069.61
#Mann=3,-1,0
  4831.8    0.15       0  4977.0    0.05       0  5023.0    0.15       0
Bank Sta=4977,5023
XS Rating Curve= 0
Exp/Cntr=0.3,0.1

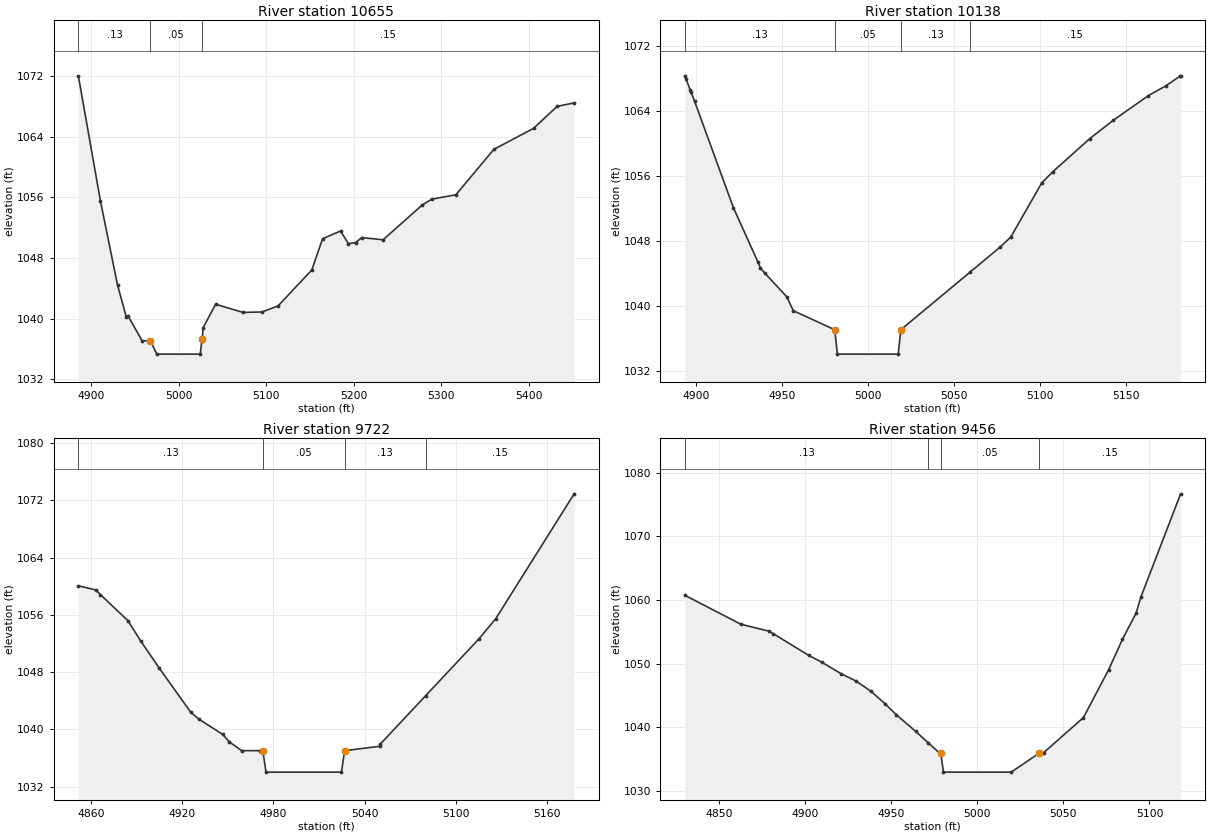
Type RM Length L Ch R = 1,10655,517,517,517
BEGIN DESCRIPTION:
South Fork 36.0
END DESCRIPTION:
XS GIS Cut Line= 3
      1459808.81       949420.61      1459889.51       949332.10
      1460181.16       948993.59
#Sta/Elev= 30
  4885.5 1072.03  4910.8 1055.51  4930.3 1044.43  4940.2 1040.28  4942.6 1040.31
  4958.4 1037.08  4967.9 1037.10  4975.2 1035.33  5024.8 1035.33  5026.9 1037.33
  5027.2 1037.10  5028.0 1038.78  5042.4 1041.91  5073.7 1040.83  5095.4 1040.89
  5113.7 1041.68  5152.3 1046.43  5164.6 1050.55  5185.2 1051.57  5194.0 1049.91
  5202.4 1050.02  5209.2 1050.70  5233.8 1050.41  5278.5 1055.00  5289.4 1055.77
  5316.9 1056.34  5360.3 1062.33  5405.8 1065.11  5432.6 1068.00  5452.1 1068.46
#Mann=3,-1,0
  4885.5    0.13       0  4967.9    0.05       0  5026.9    0.15       0
Bank Sta=4967.9,5026.9
XS Rating Curve= 0
Exp/Cntr=0.3,0.1

Type RM Length L Ch R = 1,10138,416,416,416
BEGIN DESCRIPTION:
South Fork 34.0
END DESCRIPTION:
XS GIS Cut Line= 3
      1460423.39       949201.91      1460358.26       949139.39
      1460204.65       949014.42
#Sta/Elev= 26
  4893.6 1068.30  4894.3 1067.95  4896.8 1066.52  4897.3 1066.28  4899.3 1065.16
  4921.9 1052.06  4936.0 1045.46  4937.6 1044.67  4940.0 1044.06  4952.9 1041.12
  4956.7 1039.41  4980.8 1037.07  4982.3 1034.07  5017.7 1034.07  5019.2 1037.07
  5059.5 1044.16  5076.8 1047.21  5083.1 1048.45  5101.2 1055.15  5107.7 1056.53
  5129.1 1060.58  5142.8 1062.84  5163.2 1065.87  5173.3 1067.07  5181.4 1068.24
  5181.9 1068.29
#Mann=4,-1,0
  4893.6    0.13       0  4980.8    0.05       0  5019.2    0.13       0
  5059.5    0.15       0
Bank Sta=4980.8,5019.2
XS Rating Curve= 0
Exp/Cntr=0.3,0.1

Type RM Length L Ch R = 1,9722,266,266,266
BEGIN DESCRIPTION:
South Fork 32.0
END DESCRIPTION:
XS GIS Cut Line= 3
      1460774.93       948983.14      1460662.95       948865.96
      1460545.75       948751.36
#Sta/Elev= 22
  4851.8 1060.07  4863.4 1059.48  4866.3 1058.84  4884.4 1055.20  4892.7 1052.39
  4905.0 1048.57  4925.7 1042.40  4931.0 1041.44  4946.7 1039.31  4951.0 1038.27
  4959.2 1037.03  4971.4 1037.03  4973.1 1037.03  4975.2 1034.03  5024.8 1034.03
  5026.9 1037.03  5050.0 1037.64  5050.3 1037.94  5080.2 1044.72  5115.4 1052.70
  5126.3 1055.49  5177.8 1072.92
#Mann=4,-1,0
  4851.8    0.13       0  4973.1    0.05       0  5026.9    0.13       0
  5080.2    0.15       0
Bank Sta=4973.1,5026.9
XS Rating Curve= 0
Exp/Cntr=0.3,0.1

Type RM Length L Ch R = 1,9456,416,416,416
BEGIN DESCRIPTION:
South Fork 31.0
END DESCRIPTION:
XS GIS Cut Line= 3
      1460777.52       948993.57      1460910.34       948884.18
      1460993.68       948803.45
#Sta/Elev= 25
  4830.0 1060.76  4862.6 1056.20  4878.7 1055.13  4881.5 1054.70  4901.9 1051.33
  4909.5 1050.25  4921.0 1048.41  4929.4 1047.29  4938.1 1045.69  4946.2 1043.75
  4952.8 1042.01  4964.2 1039.36  4971.4 1037.59  4978.0 1035.97  4978.7 1035.97
  4980.3 1032.97  5019.7 1032.97  5036.0 1035.97  5038.6 1036.05  5061.6 1041.53
  5076.2 1049.02  5084.3 1053.84  5092.2 1057.92  5095.0 1060.46  5118.1 1076.69
#Mann=4,-1,0
  4830.0    0.13       0  4971.4    0.15       0  4978.7    0.05       0
  5036.0    0.15       0
Bank Sta=4978.7,5036
XS Rating Curve= 0
Exp/Cntr=0.3,0.1