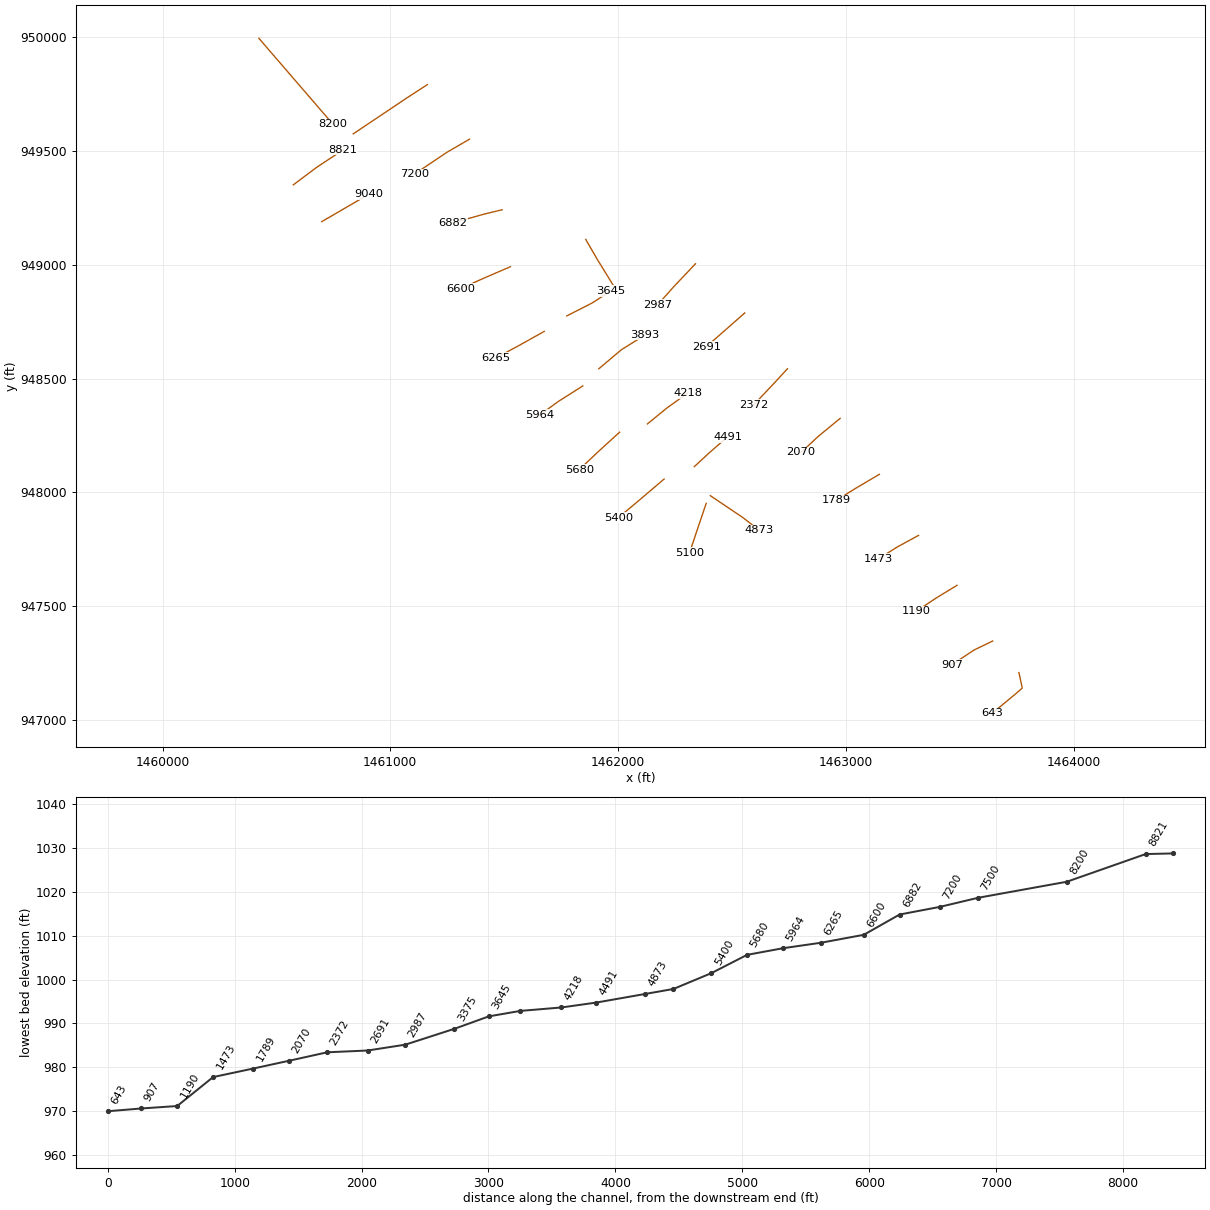
HEC-RAS study South Fork.prj: South Fork Limited Detail Study

--- South Fork.g01 (geometry) --- (continued)

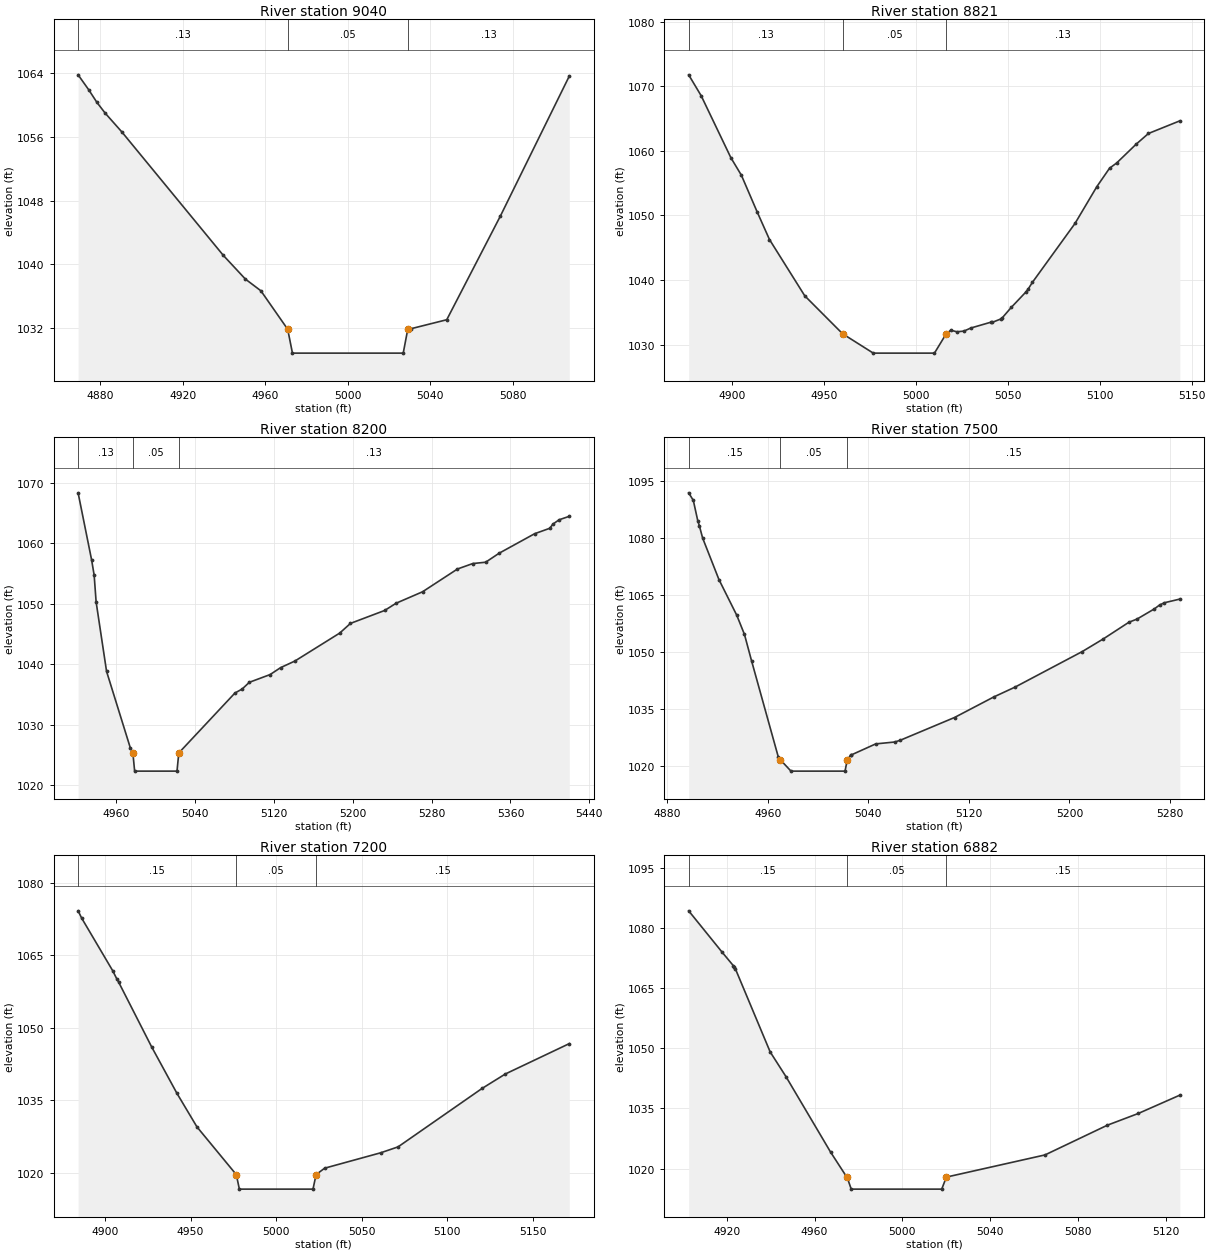
Type RM Length L Ch R = 1,9040,219,219,219
BEGIN DESCRIPTION:
South Fork 29.5
END DESCRIPTION:
XS GIS Cut Line= 2
      1460699.42       949188.88      1460905.18       949308.69
#Sta/Elev= 17
  4869.3 1063.82  4874.5 1061.92  4878.4 1060.36  4882.4 1059.01  4890.5 1056.64
  4939.7 1041.11  4950.4 1038.13  4957.9 1036.66  4970.9 1031.82  4973.2 1028.82
  5026.9 1028.82  5029.1 1031.82  5029.7 1031.87  5030.5 1031.88  5048.0 1033.02
  5073.9 1046.01  5107.4 1063.66
#Mann=3,-1,0
  4869.3    0.13       0  4970.9    0.05       0  5029.1    0.13       0
Bank Sta=4970.9,5029.1
XS Rating Curve= 0
Exp/Cntr=0.3,0.1

Type RM Length L Ch R = 1,8821,621,621,621
BEGIN DESCRIPTION:
South Fork 29.0
END DESCRIPTION:
XS GIS Cut Line= 3
      1460574.43       949350.35      1460678.57       949428.46
      1460793.15       949503.97
#Sta/Elev= 30
  4876.2 1071.80  4883.0 1068.56  4899.2 1058.94  4904.9 1056.24  4913.4 1050.61
  4920.2 1046.27  4939.4 1037.55  4960.0 1031.67  4976.7 1028.67  5010.0 1028.67
  5016.4 1031.67  5018.9 1032.22  5022.2 1031.98  5026.0 1032.08  5029.8 1032.56
  5040.8 1033.47  5041.4 1033.43  5046.0 1033.95  5047.0 1034.17  5051.8 1035.75
  5059.6 1038.09  5061.0 1038.59  5063.3 1039.63  5086.5 1048.76  5098.4 1054.47
  5105.3 1057.32  5109.2 1058.14  5119.8 1061.05  5126.5 1062.71  5143.6 1064.67
#Mann=3,-1,0
  4876.2    0.13       0  4960.0    0.05       0  5016.4    0.13       0
Bank Sta=4960,5016.4
XS Rating Curve= 0
Exp/Cntr=0.3,0.1

Type RM Length L Ch R = 1,8200,700,700,700
BEGIN DESCRIPTION:
South Fork 28.0
END DESCRIPTION:
XS GIS Cut Line= 3
      1460423.36       949993.57      1460519.72       949881.58
      1460748.91       949615.92
#Sta/Elev= 30
  4921.1 1068.35  4934.8 1057.27  4937.4 1054.74  4939.4 1050.31  4950.0 1038.83
  4974.0 1026.25  4976.7 1025.35  4978.5 1022.35  5021.5 1022.35  5023.3 1025.35
  5080.3 1035.26  5087.7 1035.93  5094.9 1037.03  5116.0 1038.31  5126.6 1039.45
  5141.2 1040.55  5186.6 1045.16  5197.6 1046.77  5232.2 1048.90  5244.0 1050.11
  5270.7 1051.99  5306.2 1055.76  5321.7 1056.66  5334.8 1056.88  5348.5 1058.37
  5384.5 1061.59  5399.9 1062.49  5403.0 1063.17  5409.3 1063.89  5419.7 1064.47
#Mann=3,-1,0
  4921.1    0.13       0  4976.7    0.05       0  5023.3    0.13       0
Bank Sta=4976.7,5023.3
XS Rating Curve= 0
Exp/Cntr=0.3,0.1

Type RM Length L Ch R = 1,7500,300,300,300
BEGIN DESCRIPTION:
South Fork 25.0
END DESCRIPTION:
XS GIS Cut Line= 3
      1461162.98       949790.46      1461076.66       949734.45
      1460837.42       949574.29
#Sta/Elev= 30
  4897.1 1091.86  4900.8 1089.86  4904.3 1084.58  4905.6 1083.19  4908.2 1079.98
  4921.2 1069.04  4935.4 1059.64  4941.5 1054.61  4947.1 1047.72  4968.5 1022.29
  4970.0 1021.68  4978.5 1018.68  5021.5 1018.68  5023.3 1021.68  5025.9 1022.82
  5026.5 1022.94  5045.9 1025.84  5061.1 1026.34  5065.6 1026.82  5108.6 1032.78
  5139.7 1038.16  5156.8 1040.78  5210.3 1050.13  5227.1 1053.47  5247.4 1057.84
  5253.8 1058.66  5267.7 1061.36  5271.7 1062.35  5275.6 1062.96  5287.9 1063.92
#Mann=3,-1,0
  4897.1    0.15       0  4970.0    0.05       0  5023.3    0.15       0
Bank Sta=4970,5023.3
XS Rating Curve= 0
Exp/Cntr=0.3,0.1

Type RM Length L Ch R = 1,7200,318,318,318
BEGIN DESCRIPTION:
South Fork 24.0
END DESCRIPTION:
XS GIS Cut Line= 3
      1461347.83       949550.85      1461247.81       949492.69
      1461105.70       949397.23
#Sta/Elev= 18
  4884.3 1074.16  4886.4 1072.64  4904.5 1061.78  4906.9 1060.09  4908.0 1059.40
  4927.2 1046.06  4942.0 1036.44  4953.7 1029.49  4976.7 1019.61  4978.5 1016.61
  5021.5 1016.61  5023.3 1019.61  5028.3 1020.94  5061.1 1024.13  5071.2 1025.35
  5120.2 1037.42  5133.9 1040.43  5171.2 1046.70
#Mann=3,-1,0
  4884.3    0.15       0  4976.7    0.05       0  5023.3    0.15       0
Bank Sta=4976.7,5023.3
XS Rating Curve= 0
Exp/Cntr=0.3,0.1

Type RM Length L Ch R = 1,6882,282,282,282
BEGIN DESCRIPTION:
South Fork 23.0
END DESCRIPTION:
XS GIS Cut Line= 3
      1461491.07       949240.95      1461415.55       949222.73
      1461274.96       949183.67
#Sta/Elev= 17
  4902.7 1084.29  4918.0 1073.92  4923.1 1070.56  4923.5 1070.32  4924.0 1069.77
  4939.8 1049.09  4947.0 1042.92  4967.3 1024.10  4974.6 1017.92  4974.8 1017.86
  4976.7 1014.86  5017.9 1014.86  5020.0 1017.86  5064.9 1023.39  5093.3 1030.81
  5107.4 1033.74  5126.3 1038.31
#Mann=3,-1,0
  4902.7    0.15       0  4974.8    0.05       0  5020.0    0.15       0
Bank Sta=4974.8,5020
XS Rating Curve= 0
Exp/Cntr=0.3,0.1

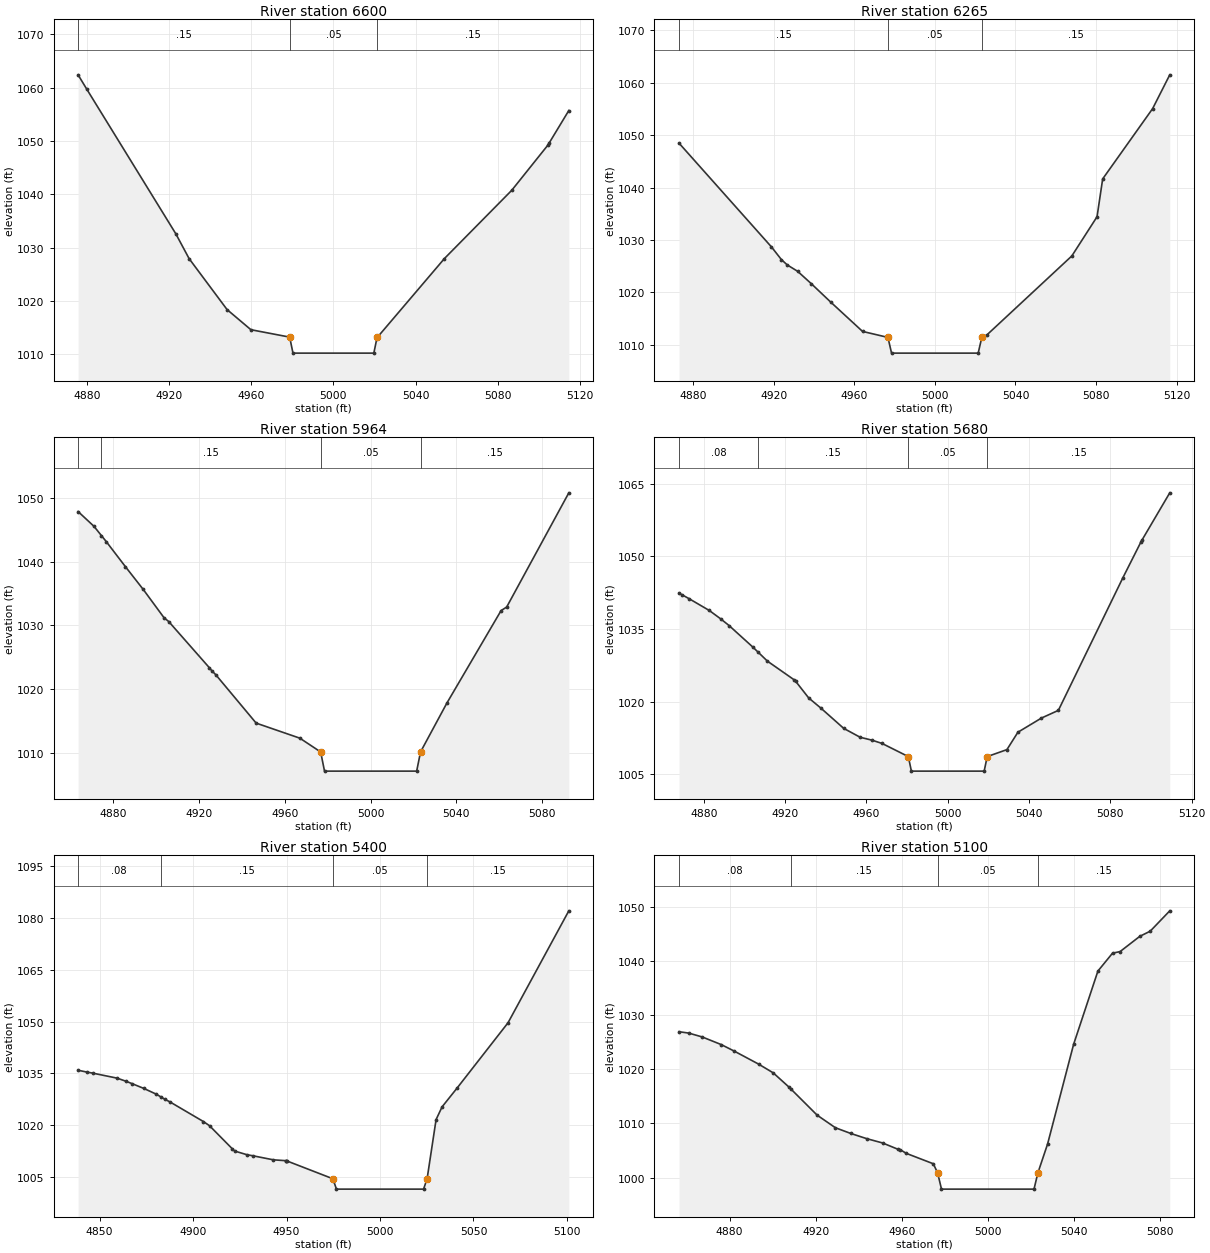
Type RM Length L Ch R = 1,6600,335,335,335
BEGIN DESCRIPTION:
South Fork 22.0
END DESCRIPTION:
XS GIS Cut Line= 3
      1461527.56       948990.97      1461413.30       948941.76
      1461308.75       948894.59
#Sta/Elev= 16
  4875.6 1062.39  4879.9 1059.66  4923.2 1032.61  4929.7 1027.94  4948.2 1018.39
  4959.8 1014.62  4978.7 1013.23  4980.3 1010.23  5019.7 1010.23  5021.3 1013.23
  5021.5 1013.23  5054.1 1027.96  5086.9 1040.75  5104.7 1049.31  5105.2 1049.66
  5114.7 1055.70
#Mann=3,-1,0
  4875.6    0.15       0  4978.7    0.05       0  5021.3    0.15       0
Bank Sta=4978.7,5021.3
XS Rating Curve= 0
Exp/Cntr=0.3,0.1

Type RM Length L Ch R = 1,6265,301,301,301
BEGIN DESCRIPTION:
South Fork 21.0
END DESCRIPTION:
XS GIS Cut Line= 3
      1461675.94       948707.08      1461569.20       948647.21
      1461462.39       948589.89
#Sta/Elev= 18
  4873.0 1048.48  4918.9 1028.68  4923.8 1026.28  4926.7 1025.26  4931.9 1024.03
  4938.7 1021.66  4948.2 1018.20  4964.1 1012.57  4976.7 1011.43  4978.5 1008.43
  5021.5 1008.43  5023.3 1011.43  5025.9 1011.93  5068.0 1026.97  5080.5 1034.44
  5083.3 1041.66  5108.1 1055.07  5116.6 1061.51
#Mann=3,-1,0
  4873.0    0.15       0  4976.7    0.05       0  5023.3    0.15       0
Bank Sta=4976.7,5023.3
XS Rating Curve= 0
Exp/Cntr=0.3,0.1

Type RM Length L Ch R = 1,5964,284,284,284
BEGIN DESCRIPTION:
South Fork 20.0
END DESCRIPTION:
XS GIS Cut Line= 3
      1461845.23       948467.51      1461738.47       948399.81
      1461655.17       948339.94
#Sta/Elev= 21
  4863.5 1047.83  4870.9 1045.52  4874.4 1044.06  4876.7 1043.10  4885.6 1039.19
  4893.9 1035.63  4903.6 1031.20  4905.8 1030.60  4924.8 1023.35  4926.0 1022.86
  4927.7 1022.29  4946.6 1014.69  4967.0 1012.33  4976.7 1010.17  4978.5 1007.17
  5021.5 1007.17  5023.3 1010.17  5035.6 1017.83  5060.9 1032.32  5063.5 1032.87
  5092.5 1050.76
#Mann=4,-1,0
  4863.5    0.08       0  4874.4    0.15       0  4976.7    0.05       0
  5023.3    0.15       0
Bank Sta=4976.7,5023.3
XS Rating Curve= 0
Exp/Cntr=0.3,0.1

Type RM Length L Ch R = 1,5680,280,280,280
BEGIN DESCRIPTION:
South Fork 19.0
END DESCRIPTION:
XS GIS Cut Line= 3
      1462006.72       948264.41      1461918.16       948183.66
      1461829.65       948100.36
#Sta/Elev= 29
  4867.8 1042.41  4869.1 1042.10  4872.7 1041.26  4882.7 1038.81  4888.3 1037.08
  4892.4 1035.71  4904.1 1031.26  4906.8 1030.17  4911.3 1028.35  4924.5 1024.48
  4925.2 1024.18  4931.6 1020.75  4937.5 1018.69  4948.8 1014.48  4956.9 1012.64
  4962.9 1012.02  4967.7 1011.36  4980.6 1008.65  4982.1 1005.65  5017.9 1005.65
  5019.4 1008.65  5029.1 1010.09  5034.5 1013.68  5046.1 1016.61  5054.4 1018.19
  5086.2 1045.62  5095.0 1052.94  5095.5 1053.32  5109.2 1063.10
#Mann=4,-1,0
  4867.8    0.08       0  4906.8    0.15       0  4980.6    0.05       0
  5019.4    0.15       0
Bank Sta=4980.6,5019.4
XS Rating Curve= 0
Exp/Cntr=0.3,0.1

Type RM Length L Ch R = 1,5400,300,300,300
BEGIN DESCRIPTION:
South Fork 18.0
END DESCRIPTION:
XS GIS Cut Line= 3
      1462202.04       948058.69      1462079.04       947954.02
      1462001.45       947889.36
#Sta/Elev= 30
  4838.5 1035.91  4843.3 1035.37  4846.3 1035.08  4859.4 1033.62  4864.1 1032.73
  4867.2 1032.07  4873.7 1030.64  4880.3 1028.99  4882.6 1028.25  4884.8 1027.54
  4887.6 1026.76  4905.5 1021.07  4908.8 1019.85  4921.1 1013.11  4922.3 1012.51
  4928.9 1011.44  4931.8 1011.17  4943.0 1009.97  4949.6 1009.73  4949.9 1009.72
  4950.2 1009.65  4974.8 1004.49  4976.7 1001.49  5023.3 1001.49  5025.2 1004.49
  5030.0 1021.63  5033.2 1025.31  5041.3 1030.80  5068.5 1049.67  5101.0 1082.07
#Mann=4,-1,0
  4838.5    0.08       0  4882.6    0.15       0  4974.8    0.05       0
  5025.2    0.15       0
Bank Sta=4974.8,5025.2
XS Rating Curve= 0
Exp/Cntr=0.3,0.1

Type RM Length L Ch R = 1,5100,227,227,227
BEGIN DESCRIPTION:
South Fork 17.0
END DESCRIPTION:
XS GIS Cut Line= 3
      1462386.90       947951.86      1462340.92       947815.92
      1462313.98       947735.73
#Sta/Elev= 30
  4856.5 1026.97  4861.0 1026.72  4867.3 1026.00  4876.2 1024.58  4882.1 1023.40
  4893.5 1020.98  4900.3 1019.36  4907.7 1016.70  4908.4 1016.42  4920.7 1011.54
  4929.2 1009.21  4936.3 1008.16  4943.7 1007.20  4951.1 1006.40  4958.4 1005.21
  4959.4 1005.14  4962.1 1004.48  4974.7 1002.55  4976.7 1000.86  4978.5  997.86
  5021.5  997.86  5023.3 1000.86  5027.8 1006.19  5039.9 1024.63  5051.2 1038.19
  5058.0 1041.50  5061.5 1041.79  5070.7 1044.62  5075.5 1045.56  5084.6 1049.33
#Mann=4,-1,0
  4856.5    0.08       0  4908.4    0.15       0  4976.7    0.05       0
  5023.3    0.15       0
Bank Sta=4976.7,5023.3
XS Rating Curve= 0
Exp/Cntr=0.3,0.1

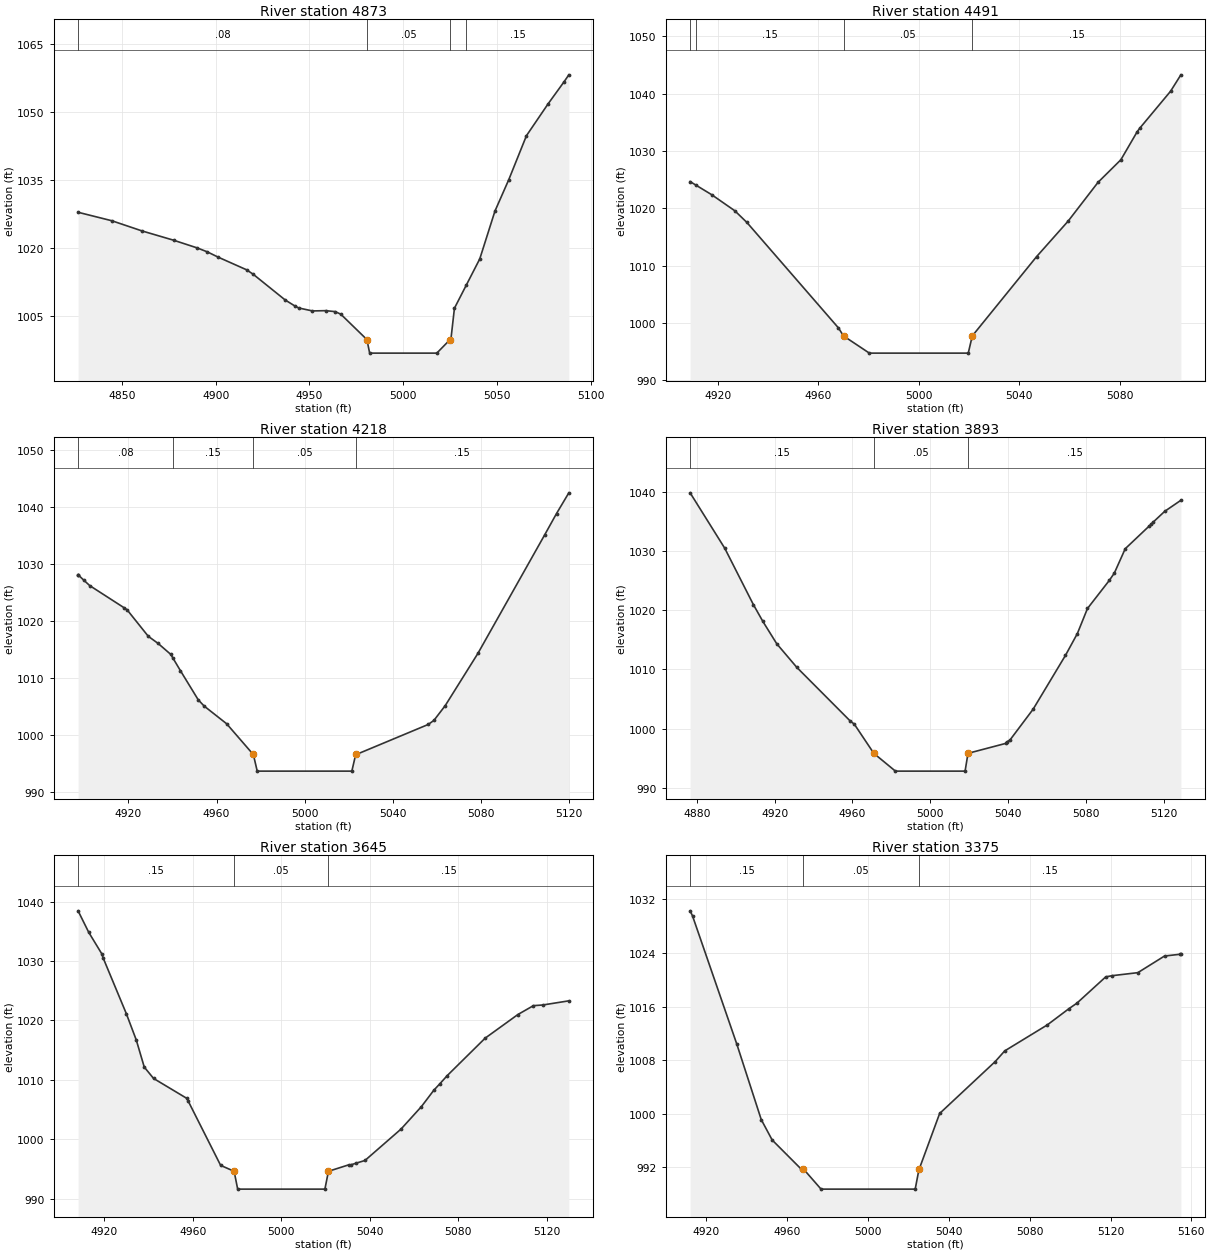
Type RM Length L Ch R = 1,4873,382,382,382
BEGIN DESCRIPTION:
South Fork 16.0
END DESCRIPTION:
XS GIS Cut Line= 3
      1462405.11       947985.76      1462548.37       947889.39
      1462618.66       947834.72
#Sta/Elev= 30
  4826.6 1027.78  4844.6 1025.91  4860.8 1023.65  4877.5 1021.62  4890.1 1019.92
  4895.6 1019.03  4901.4 1017.86  4916.5 1015.08  4920.0 1014.10  4937.0 1008.44
  4942.3 1007.08  4944.3 1006.66  4951.6 1006.01  4958.7 1006.07  4963.7 1005.86
  4966.7 1005.29  4980.6  999.70  4982.1  996.70  5017.9  996.70  5025.0  999.70
  5025.4  999.70  5027.3 1006.61  5033.6 1011.69  5040.8 1017.49  5048.9 1028.04
  5056.3 1035.00  5065.7 1044.68  5077.2 1051.68  5085.8 1056.60  5088.3 1058.11
#Mann=4,-1,0
  4826.6    0.08       0  4980.6    0.05       0  5025.0    0.08       0
  5033.6    0.15       0
Bank Sta=4980.6,5025
XS Rating Curve= 0
Exp/Cntr=0.3,0.1

Type RM Length L Ch R = 1,4491,273,273,273
BEGIN DESCRIPTION:
South Fork 15.0
END DESCRIPTION:
XS GIS Cut Line= 3
      1462334.85       948113.38      1462402.53       948175.85
      1462480.67       948243.57
#Sta/Elev= 18
  4908.9 1024.67  4911.4 1024.00  4917.5 1022.38  4926.7 1019.58  4931.5 1017.55
  4968.0  999.14  4970.0  997.75  4980.3  994.75  5019.7  994.75  5021.3  997.75
  5046.9 1011.57  5059.5 1017.78  5071.4 1024.54  5080.5 1028.48  5087.0 1033.37
  5088.0 1033.97  5100.3 1040.43  5104.4 1043.29
#Mann=4,-1,0
  4908.9    0.08       0  4911.4    0.15       0  4970.0    0.05       0
  5021.3    0.15       0
Bank Sta=4970,5021.3
XS Rating Curve= 0
Exp/Cntr=0.3,0.1

Type RM Length L Ch R = 1,4218,325,325,325
BEGIN DESCRIPTION:
South Fork 14.0
END DESCRIPTION:
XS GIS Cut Line= 3
      1462129.12       948300.87      1462215.03       948371.16
      1462306.17       948436.26
#Sta/Elev= 27
  4897.1 1028.12  4897.2 1028.08  4899.6 1027.20  4902.4 1026.21  4917.9 1022.35
  4919.4 1021.95  4929.0 1017.31  4933.5 1016.05  4939.2 1014.14  4940.2 1013.49
  4943.6 1011.28  4951.7 1006.16  4954.4 1005.06  4964.6 1001.96  4976.5  996.65
  4976.7  996.64  4978.5  993.64  5021.5  993.64  5023.3  996.64  5024.0  996.64
  5056.2 1001.83  5058.8 1002.55  5063.9 1005.12  5078.8 1014.32  5109.2 1035.17
  5114.5 1038.86  5120.1 1042.50
#Mann=4,-1,0
  4897.1    0.08       0  4940.2    0.15       0  4976.7    0.05       0
  5023.3    0.15       0
Bank Sta=4976.7,5023.3
XS Rating Curve= 0
Exp/Cntr=0.3,0.1

Type RM Length L Ch R = 1,3893,248,248,248
BEGIN DESCRIPTION:
South Fork 13.0
END DESCRIPTION:
XS GIS Cut Line= 3
      1461915.56       948543.04      1462014.51       948626.37
      1462118.67       948691.47
#Sta/Elev= 27
  4876.6 1039.79  4894.4 1030.44  4909.1 1020.94  4914.0 1018.09  4921.1 1014.34
  4931.4 1010.36  4958.8 1001.33  4961.0 1000.76  4971.0  995.85  4982.1  992.85
  5017.9  992.85  5019.4  995.85  5038.7  997.52  5039.3  997.75  5041.0  998.11
  5052.9 1003.31  5069.5 1012.38  5075.6 1016.05  5080.8 1020.28  5092.0 1025.01
  5094.6 1026.25  5100.2 1030.36  5112.5 1034.18  5113.5 1034.46  5114.4 1034.80
  5120.5 1036.67  5128.8 1038.53
#Mann=3,-1,0
  4876.6    0.15       0  4971.0    0.05       0  5019.4    0.15       0
Bank Sta=4971,5019.4
XS Rating Curve= 0
Exp/Cntr=0.3,0.1

Type RM Length L Ch R = 1,3645,270,270,270
BEGIN DESCRIPTION:
South Fork 12.0
END DESCRIPTION:
XS GIS Cut Line= 3
      1461775.00       948775.00      1461886.91       948832.10
      1461967.63       948884.18
#Sta/Elev= 29
  4908.2 1038.44  4913.0 1034.83  4918.9 1031.21  4919.6 1030.44  4930.0 1021.13
  4934.5 1016.69  4938.1 1012.14  4942.3 1010.23  4957.3 1006.88  4958.0 1006.38
  4972.6  995.60  4978.7  994.60  4980.3  991.60  5019.7  991.60  5021.3  994.60
  5030.4  995.68  5031.5  995.69  5033.8  995.97  5037.8  996.42  5054.1 1001.71
  5063.3 1005.49  5068.9 1008.24  5071.6 1009.32  5075.0 1010.72  5092.1 1017.01
  5106.9 1020.99  5113.9 1022.48  5118.1 1022.59  5129.9 1023.29
#Mann=3,-1,0
  4908.2    0.15       0  4978.7    0.05       0  5021.3    0.15       0
Bank Sta=4978.7,5021.3
XS Rating Curve= 0
Exp/Cntr=0.3,0.1

Type RM Length L Ch R = 1,3375,388,388,388
BEGIN DESCRIPTION:
South Fork 11.0
END DESCRIPTION:
XS GIS Cut Line= 3
      1461858.28       949110.72      1461907.74       949024.81
      1461983.24       948902.45
#Sta/Elev= 23
  4911.9 1030.27  4913.1 1029.50  4935.0 1010.40  4947.1  999.14  4952.5  996.10
  4966.6  991.84  4968.0  991.77  4976.7  988.77  5023.3  988.77  5025.2  991.77
  5025.3  991.77  5035.4 1000.05  5062.9 1007.79  5067.6 1009.38  5088.7 1013.26
  5099.3 1015.66  5103.3 1016.49  5117.6 1020.42  5120.8 1020.60  5133.5 1021.05
  5146.7 1023.53  5154.3 1023.79  5154.8 1023.87
#Mann=3,-1,0
  4911.9    0.15       0  4968.0    0.05       0  5025.2    0.15       0
Bank Sta=4968,5025.2
XS Rating Curve= 0
Exp/Cntr=0.3,0.1

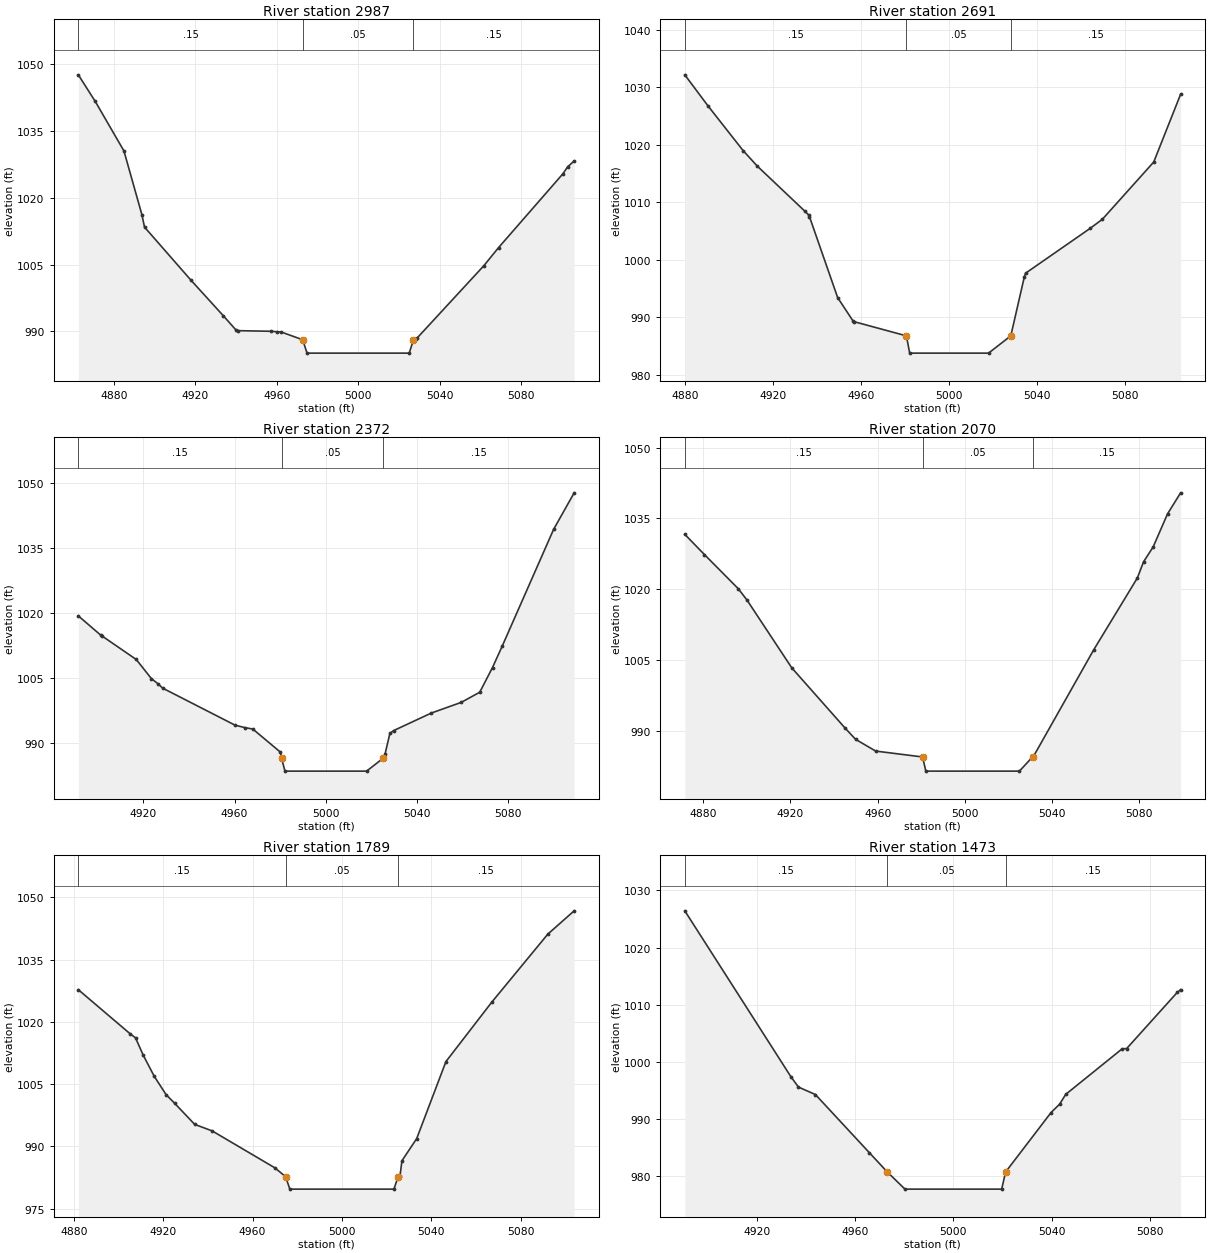
Type RM Length L Ch R = 1,2987,296,296,296
BEGIN DESCRIPTION:
South Fork 10.0
END DESCRIPTION:
XS GIS Cut Line= 3
      1462340.06       949004.01      1462243.68       948902.41
      1462175.02       948825.02
#Sta/Elev= 24
  4862.6 1047.58  4870.9 1041.62  4885.0 1030.50  4893.8 1016.23  4895.1 1013.42
  4917.8 1001.56  4933.8  993.53  4940.0  990.34  4941.0  990.18  4957.4  990.04
  4960.2  989.93  4962.1  989.90  4972.8  988.14  4974.9  985.14  5025.1  985.14
  5027.2  988.14  5027.6  988.14  5028.4  988.41  5029.0  988.54  5061.8 1004.78
  5069.0 1008.83  5100.6 1025.39  5102.9 1026.94  5106.1 1028.25
#Mann=3,-1,0
  4862.6    0.15       0  4972.8    0.05       0  5027.2    0.15       0
Bank Sta=4972.8,5027.2
XS Rating Curve= 0
Exp/Cntr=0.3,0.1

Type RM Length L Ch R = 1,2691,319,319,319
BEGIN DESCRIPTION:
South Fork 9.0
END DESCRIPTION:
XS GIS Cut Line= 3
      1462556.15       948787.81      1462470.24       948712.31
      1462386.91       948639.39
#Sta/Elev= 20
  4880.0 1032.15  4890.6 1026.72  4906.5 1018.98  4912.9 1016.30  4934.6 1008.43
  4936.3 1007.78  4936.6 1007.51  4949.4  993.45  4956.3  989.44  4956.7  989.29
  4980.6  986.81  4982.1  983.81  5017.9  983.81  5028.0  986.81  5034.1  996.98
  5034.7  997.69  5064.1 1005.50  5069.6 1007.07  5092.9 1017.01  5105.1 1028.78
#Mann=3,-1,0
  4880.0    0.15       0  4980.6    0.05       0  5028.0    0.15       0
Bank Sta=4980.6,5028
XS Rating Curve= 0
Exp/Cntr=0.3,0.1

Type RM Length L Ch R = 1,2372,302,302,302
BEGIN DESCRIPTION:
South Fork 8.0
END DESCRIPTION:
XS GIS Cut Line= 3
      1462743.67       948543.03      1462681.18       948475.33
      1462595.24       948384.19
#Sta/Elev= 25
  4891.5 1019.25  4901.4 1014.77  4901.7 1014.68  4916.9 1009.18  4923.5 1004.79
  4926.3 1003.62  4928.5 1002.56  4960.2  994.02  4964.5  993.45  4968.0  993.12
  4980.1  987.79  4980.6  986.40  4982.1  983.40  5017.9  983.40  5025.2  986.40
  5026.0  987.38  5028.1  992.10  5029.7  992.75  5046.3  996.82  5059.4  999.28
  5067.5 1001.62  5073.1 1007.33  5077.4 1012.32  5099.9 1039.24  5108.9 1047.67
#Mann=3,-1,0
  4891.5    0.15       0  4980.6    0.05       0  5025.2    0.15       0
Bank Sta=4980.6,5025.2
XS Rating Curve= 0
Exp/Cntr=0.3,0.1

Type RM Length L Ch R = 1,2070,281,281,281
BEGIN DESCRIPTION:
South Fork 7.0
END DESCRIPTION:
XS GIS Cut Line= 3
      1462975.00       948325.00      1462879.09       948246.16
      1462803.60       948175.87
#Sta/Elev= 19
  4871.6 1031.63  4880.6 1027.35  4896.1 1020.12  4900.1 1017.72  4920.6 1003.37
  4945.1  990.57  4949.9  988.20  4959.1  985.71  4980.6  984.46  4982.1  981.46
  5025.0  981.46  5031.0  984.46  5031.3  984.46  5059.0 1007.12  5079.1 1022.42
  5081.9 1025.81  5086.3 1028.96  5092.9 1035.97  5098.9 1040.43
#Mann=3,-1,0
  4871.6    0.15       0  4980.6    0.05       0  5031.0    0.15       0
Bank Sta=4980.6,5031
XS Rating Curve= 0
Exp/Cntr=0.3,0.1

Type RM Length L Ch R = 1,1789,316,316,316
BEGIN DESCRIPTION:
South Fork 6.0
END DESCRIPTION:
XS GIS Cut Line= 3
      1463147.30       948079.48      1463045.76       948019.60
      1462957.18       947964.89
#Sta/Elev= 21
  4882.0 1027.75  4905.3 1017.08  4907.6 1016.16  4911.0 1012.03  4916.0 1006.87
  4921.3 1002.46  4925.2 1000.34  4934.1  995.29  4941.9  993.73  4970.0  984.82
  4974.8  982.69  4976.7  979.69  5023.3  979.69  5025.2  982.69  5026.0  982.77
  5026.9  986.54  5033.5  991.87  5046.6 1010.44  5067.1 1024.74  5092.2 1041.14
  5104.0 1046.76
#Mann=3,-1,0
  4882.0    0.15       0  4974.8    0.05       0  5025.2    0.15       0
Bank Sta=4974.8,5025.2
XS Rating Curve= 0
Exp/Cntr=0.3,0.1

Type RM Length L Ch R = 1,1473,283,283,283
BEGIN DESCRIPTION:
South Fork 5.0
END DESCRIPTION:
XS GIS Cut Line= 3
      1463319.18       947811.26      1463228.05       947761.79
      1463144.69       947709.69
#Sta/Elev= 16
  4890.6 1026.42  4933.8  997.42  4936.9  995.59  4943.8  994.29  4965.8  984.11
  4973.1  980.74  4980.3  977.74  5019.7  977.74  5021.3  980.74  5039.8  991.13
  5043.3  992.60  5045.8  994.32  5068.8 1002.29  5070.6 1002.32  5091.2 1012.14
  5092.6 1012.64
#Mann=3,-1,0
  4890.6    0.15       0  4973.1    0.05       0  5021.3    0.15       0
Bank Sta=4973.1,5021.3
XS Rating Curve= 0
Exp/Cntr=0.3,0.1

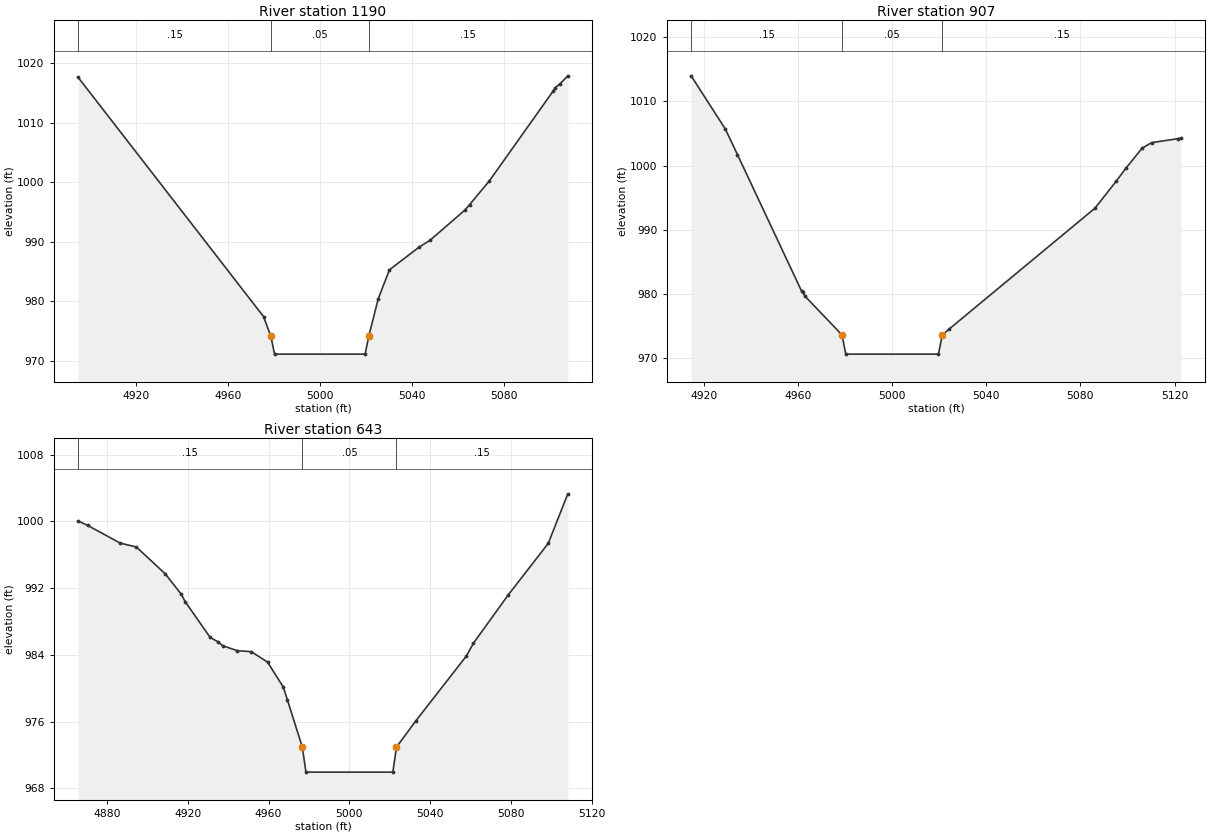
Type RM Length L Ch R = 1,1190,283,283,283
BEGIN DESCRIPTION:
South Fork 4.0
END DESCRIPTION:
XS GIS Cut Line= 3
      1463488.47       947592.51      1463394.72       947535.23
      1463308.82       947477.96
#Sta/Elev= 17
  4894.8 1017.63  4975.5  977.44  4978.7  974.13  4980.3  971.13  5019.7  971.13
  5021.3  974.13  5025.4  980.42  5030.3  985.29  5043.1  989.07  5048.0  990.27
  5063.1  995.31  5065.2  996.25  5073.8 1000.24  5101.6 1015.35  5102.4 1015.85
  5104.6 1016.56  5107.9 1017.86
#Mann=3,-1,0
  4894.8    0.15       0  4978.7    0.05       0  5021.3    0.15       0
Bank Sta=4978.7,5021.3
XS Rating Curve= 0
Exp/Cntr=0.3,0.1

Type RM Length L Ch R = 1,907,264,264,264
BEGIN DESCRIPTION:
South Fork 3.0
END DESCRIPTION:
XS GIS Cut Line= 3
      1463644.71       947347.72      1463563.99       947308.66
      1463465.05       947243.57
#Sta/Elev= 18
  4914.6 1014.00  4929.1 1005.72  4934.3 1001.70  4961.5  980.43  4962.0  980.28
  4962.9  979.64  4978.7  973.57  4980.3  970.57  5019.7  970.57  5021.3  973.57
  5024.3  974.50  5086.2  993.35  5095.2  997.55  5099.3  999.57  5106.2 1002.71
  5110.3 1003.58  5121.6 1004.20  5122.7 1004.30
#Mann=3,-1,0
  4914.6    0.15       0  4978.7    0.05       0  5021.3    0.15       0
Bank Sta=4978.7,5021.3
XS Rating Curve= 0
Exp/Cntr=0.3,0.1

Type RM Length L Ch R = 1,643,0,0,0
BEGIN DESCRIPTION:
South Fork 2.0
END DESCRIPTION:
XS GIS Cut Line= 4
      1463759.88       947209.10      1463774.58       947141.39
      1463748.89       947118.56      1463642.08       947029.99
#Sta/Elev= 25
  4865.7 1000.05  4870.5  999.51  4886.5  997.40  4894.6  996.92  4908.9  993.70
  4916.7  991.29  4918.7  990.39  4931.1  986.08  4935.0  985.56  4937.3  985.09
  4944.5  984.50  4951.4  984.38  4959.5  983.13  4967.3  980.13  4969.3  978.61
  4976.7  972.94  4978.5  969.94  5021.5  969.94  5023.3  972.94  5032.9  976.10
  5057.9  983.86  5061.4  985.40  5078.6  991.18  5098.4  997.36  5108.1 1003.30
#Mann=3,-1,0
  4865.7    0.15       0  4976.7    0.05       0  5023.3    0.15       0
Bank Sta=4976.7,5023.3
XS Rating Curve= 0
Exp/Cntr=0.3,0.1

Chan Stop Cuts=-1