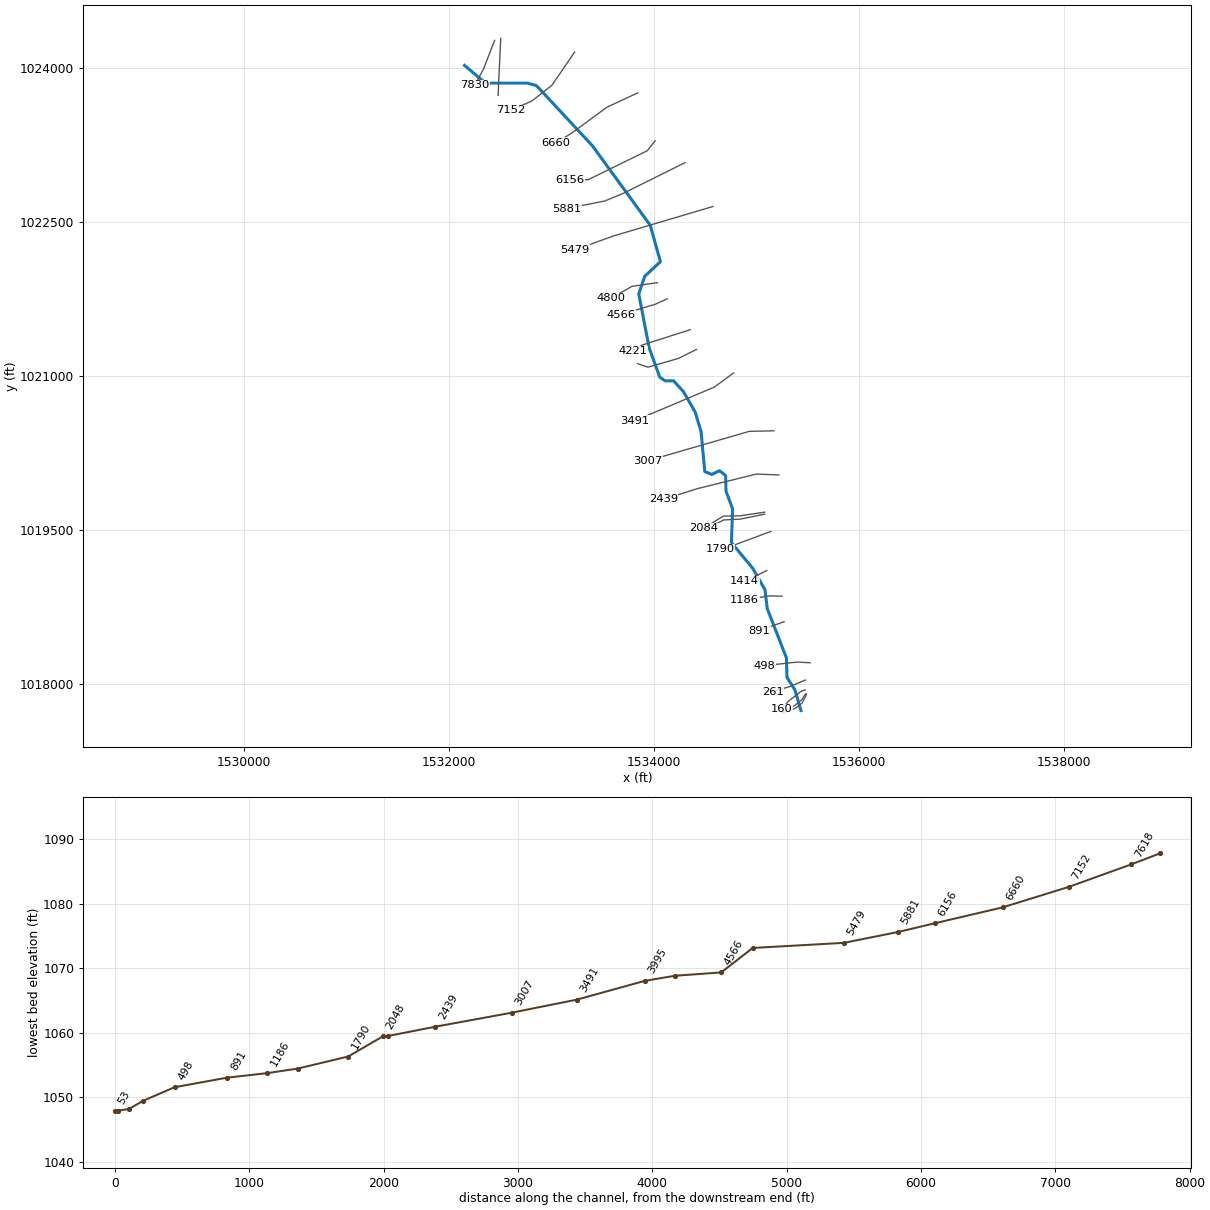
--- Johnson Creek.prj (project) ---

Proj Title=Johnson Creek Limited Detail Study
Current Plan=p01
Default Exp/Contr=0.3,0.1
English Units
Geom File=g01
Flow File=f01
Plan File=p01
Y Axis Title=Elevation
X Axis Title(PF)=Main Channel Distance
X Axis Title(XS)=Station
BEGIN DESCRIPTION:
Johnson Creek
END DESCRIPTION:
DSS Export Rating Curves= 0
DSS Export Rating Curve Sorted= 0
DSS Export Volume Flow Curves= 0
DXF OffsetX= 0
DXF OffsetY= 0
DXF ScaleX= 1
DXF ScaleY= 10

--- Johnson Creek.p01 (plan) ---

Plan Title=Floodway Run
Program Version=3.12
Short Identifier=Floodway
Geom File=g01
Flow File=f01
Subcritical Flow
K Sum by GR= 0
Std Step Tol= 0.01
Critical Tol= 0.01
Num of Std Step Trials= 20
Max Error Tol= 0.3
Flow Tol Ratio= 0.001
Split Flow NTrial= 30
Split Flow Tol= 0.02
Split Flow Ratio= 0.02
Log Output Level= 0
Friction Slope Method= 1
Unsteady Friction Slope Method= 2
Unsteady Bridges Friction Slope Method= 1
Parabolic Critical Depth
Global Vel Dist= 0 , 0 , 0
Global Log Level= 0
CheckData=True
Encroach Param=-1 ,5,5, 2
Encroach River=Johnson Creek
Encroach Reach=Reach-1
Encroach Node=7830
       1  4977.5  5022.5
Encroach Node=7618
       1    4970  5022.5
Encroach Node=7152
       1    4952    5047
Encroach Node=6660
       1 4908.86  5022.8
Encroach Node=6156
       1 4872.13  5022.8
Encroach Node=5881
       1 4891.87  5022.9
Encroach Node=5479
       1 4896.39 5131.16
Encroach Node=4800
       1  4977.1 5168.58
Encroach Node=4566
       1    4930 5031.97
Encroach Node=4221
       1 4903.98  5023.2
Encroach Node=3995
       1  4880.6  5023.2
Encroach Node=3491
       1 4974.63 5134.44
Encroach Node=3007
       1 4824.16  5116.7
Encroach Node=2439
       1  4923.8 5115.43
Encroach Node=2084
       1 4885.25 5074.32
Encroach Node=2048
       1    4865    5095
Encroach Node=1790
       1    4930  5038.4
Encroach Node=1414
       1    4970    5030
Encroach Node=1186
       1    4975    5035
Encroach Node=891
       1    4967    5027
Encroach Node=498
       1    4950    5065
Encroach Node=261
       1    4958    5018
Encroach Node=160
       1    4967    5050
Encroach Node=80
       1    4967    5038
Encroach Node=53
       1  4964.6  5035.4
BEGIN DESCRIPTION:
Floodway Run
END DESCRIPTION:
Computation Interval=1HOUR
Output Interval=1HOUR
Run HTab= 0
Run UNet= 0
Run PostProcess= 0
UNET Theta= 1
UNET Theta Warmup= 1
UNET ZTol= 0.02
UNET ZSATol= 0.05
UNET MxIter= 20
UNET MaxInSteps= 0
UNET DtIC= 0
UNET DtMin= 0
UNET MaxCRTS= 20
UNET WFStab= 2
UNET SFStab= 1
UNET WFX= 1
UNET SFX= 1
UNET DSS MLevel= 4
UNET DZMax Abort= 100
UNET Convert EG Bridges=-1
UNET Use Existing IB Tables=-1
UNET Froude Reduction=False
UNET Froude Limit= 1
UNET Froude Power= 10
Instantaneous Interval=1HOUR
Write IC File= 0
Echo Input=False
Echo Output=False
Write Detailed= 0
Detailed Automatic Start=False, 10

--- Johnson Creek.f01 (steady flow) ---

Flow Title=Floodway
Number of Profiles=2
Profile Names=100-year,100-FW
River Rch & RM= Johnson Creek,Reach-1,7830
    4436    4436
River Rch & RM= Johnson Creek,Reach-1,6660
    4495    4495
River Rch & RM= Johnson Creek,Reach-1,5881
    4511    4511
River Rch & RM= Johnson Creek,Reach-1,4566
    4589    4589
River Rch & RM= Johnson Creek,Reach-1,1186
    4599    4599
Boundary for River Rch & Prof#=Johnson Creek,Reach-1,1
Up Type=0
Dn Type=3
Dn Slope=0.0076
Boundary for River Rch & Prof#=Johnson Creek,Reach-1,2
Up Type=0
Dn Type=3
Dn Slope=0.0076

--- Johnson Creek.g01 (geometry) ---

Geom Title=Existing Conditions

River Reach=Johnson Creek,Reach-1
Reach XY= 30
      1532153.77      1024028.92      1532358.39      1023856.22
      1532765.39      1023856.46      1532854.55      1023832.31
      1533399.74      1023246.25      1533964.44      1022469.80
      1534062.89      1022115.01      1533910.57      1021972.91
      1533852.06      1021802.01      1533953.29      1021275.40
      1534056.38      1020990.27      1534108.40      1020953.12
      1534191.06      1020954.04      1534289.51      1020846.31
      1534401.89      1020648.48      1534459.47      1020459.01
      1534495.69      1020068.92      1534563.49      1020040.13
      1534639.47      1020077.28      1534698.91      1020028.99
      1534702.62      1019877.60      1534766.71      1019706.70
      1534755.56      1019376.06      1534963.61      1019125.29
      1535081.56      1018919.10      1535104.78      1018732.42
      1535291.47      1018252.25      1535297.04      1018061.85
      1535375.06      1017939.25      1535433.25      1017739.06

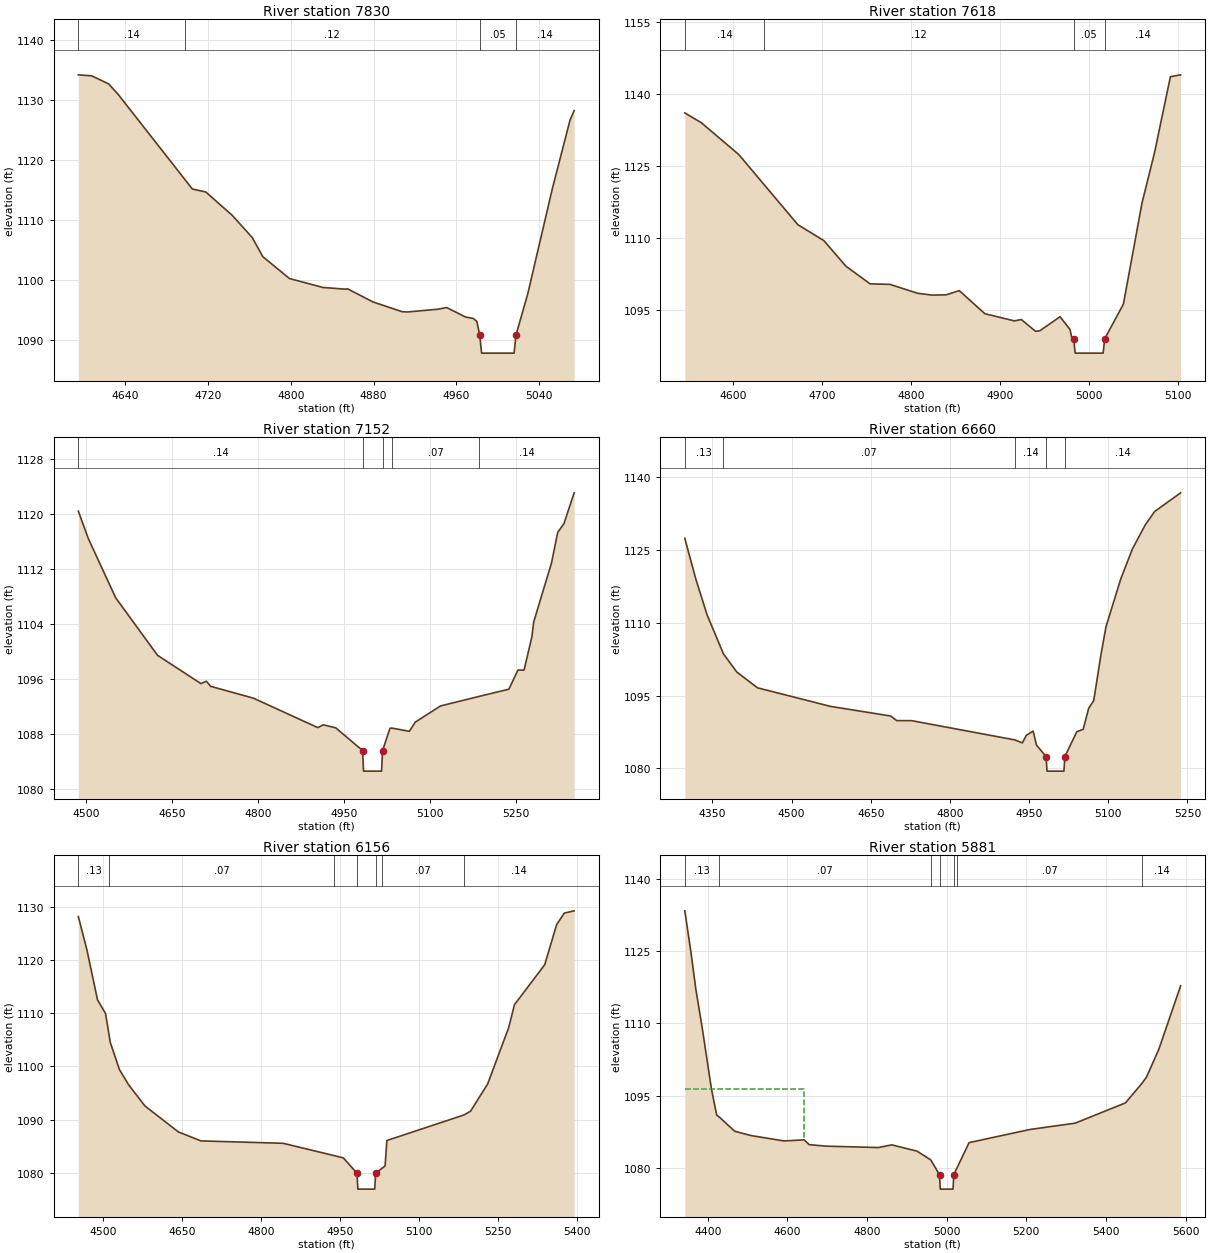
Type RM Length L Ch R = 1,7830,212,212,212
BEGIN DESCRIPTION:
Johnson Creek 26.0
END DESCRIPTION:
XS GIS Cut Line= 3
      1532446.92      1024273.07      1532339.00      1023994.77
      1532253.81      1023835.74
#Sta/Elev= 30
  4594.8 1134.13  4607.8 1133.96  4624.2 1132.61  4633.2 1130.89  4697.6 1116.73
  4704.9 1115.12  4717.9 1114.63  4743.5 1110.73  4762.8 1107.04  4773.0 1103.86
  4798.7 1100.22  4831.1 1098.73  4853.6 1098.44  4854.6 1098.53  4879.4 1096.32
  4907.5 1094.70  4912.7 1094.65  4942.1 1095.11  4950.6 1095.39  4968.5 1093.83
  4976.3 1093.57  4979.7 1093.07  4982.5 1090.80  4984.3 1087.80  5015.7 1087.80
  5017.5 1090.80  5028.8 1097.61  5052.6 1115.15  5069.7 1126.58  5073.7 1128.16
#Mann=4,-1,0
  4594.8    0.14       0  4697.6    0.12       0  4982.5    0.05       0
  5017.5    0.14       0
Bank Sta=4982.5,5017.5
XS Rating Curve= 0
Exp/Cntr=0.3,0.1

Type RM Length L Ch R = 1,7618,466,466,466
BEGIN DESCRIPTION:
Johnson Creek 25.0
END DESCRIPTION:
XS GIS Cut Line= 3
      1532506.58      1024292.99      1532492.38      1023994.77
      1532481.02      1023736.28
#Sta/Elev= 30
  4545.5 1136.15  4564.1 1134.10  4606.2 1127.47  4635.0 1121.13  4672.6 1112.86
  4701.8 1109.55  4726.6 1104.22  4753.8 1100.54  4776.1 1100.43  4807.1 1098.58
  4823.3 1098.20  4839.2 1098.25  4854.0 1099.13  4882.8 1094.32  4915.8 1092.83
  4923.8 1093.11  4939.6 1090.67  4944.3 1090.74  4967.3 1093.69  4978.4 1091.06
  4980.6 1089.23  4982.5 1089.11  4984.3 1086.11  5015.7 1086.11  5017.5 1089.11
  5038.5 1096.32  5059.4 1117.39  5073.6 1127.97  5091.3 1143.68  5102.8 1144.08
#Mann=4,-1,0
  4545.5    0.14       0  4635.0    0.12       0  4982.5    0.05       0
  5017.5    0.14       0
Bank Sta=4982.5,5017.5
XS Rating Curve= 0
Exp/Cntr=0.3,0.1

Type RM Length L Ch R = 1,7152,492,492,492
BEGIN DESCRIPTION:
Johnson Creek 24.0
END DESCRIPTION:
XS GIS Cut Line= 4
      1533227.42      1024159.47      1533005.90      1023835.71
      1532809.75      1023681.83      1532605.78      1023591.18
#Sta/Elev= 30
  4486.8 1120.43  4504.3 1116.42  4551.9 1107.83  4624.9 1099.46  4700.6 1095.34
  4710.1 1095.69  4717.7 1094.94  4792.3 1093.22  4904.4 1088.94  4914.3 1089.35
  4935.9 1088.90  4982.5 1085.61  4984.3 1082.61  5015.7 1082.61  5017.5 1085.61
  5030.4 1088.85  5033.7 1088.87  5064.1 1088.40  5074.7 1089.75  5118.5 1092.09
  5185.9 1093.48  5237.8 1094.53  5253.5 1097.31  5264.2 1097.30  5277.9 1102.15
  5281.0 1104.29  5312.1 1112.89  5322.9 1117.33  5333.9 1118.63  5351.6 1123.09
#Mann=5,-1,0
  4486.8    0.14       0  4982.5    0.05       0  5017.5    0.14       0
  5033.7    0.07       0  5185.9    0.14       0
Bank Sta=4982.5,5017.5
XS Rating Curve= 0
Exp/Cntr=0.3,0.1

Type RM Length L Ch R = 1,6660,504,504,504
BEGIN DESCRIPTION:
Johnson Creek 22.0
END DESCRIPTION:
XS GIS Cut Line= 4
      1533842.01      1023761.13      1533541.30      1023621.16
      1533196.16      1023367.38      1533043.16      1023273.88
#Sta/Elev= 30
  4297.7 1127.43  4318.6 1119.02  4340.0 1111.63  4370.9 1103.62  4396.0 1099.89
  4435.4 1096.61  4573.6 1092.79  4687.7 1090.80  4699.3 1089.85  4727.6 1089.84
  4922.8 1085.88  4937.3 1085.26  4944.8 1086.83  4957.7 1087.70  4964.0 1084.81
  4982.2 1082.44  4984.0 1079.44  5016.0 1079.44  5017.8 1082.44  5040.4 1087.56
  5052.5 1088.06  5063.0 1092.41  5072.5 1093.98  5085.9 1103.27  5095.7 1109.21
  5123.6 1119.02  5145.6 1125.19  5170.0 1130.17  5187.9 1132.95  5237.1 1136.80
#Mann=5,-1,0
  4297.7    0.13       0  4370.9    0.07       0  4922.8    0.14       0
  4982.2    0.05       0  5017.8    0.14       0
Bank Sta=4982.2,5017.8
XS Rating Curve= 0
Exp/Cntr=0.3,0.1

Type RM Length L Ch R = 1,6156,275,275,275
BEGIN DESCRIPTION:
Johnson Creek 21.0
END DESCRIPTION:
XS GIS Cut Line= 4
      1534012.01      1023293.71      1533935.54      1023197.41
      1533357.63      1022914.12      1533182.01      1022914.12
#Sta/Elev= 30
  4452.8 1128.11  4468.8 1122.00  4489.3 1112.48  4504.5 1109.93  4511.5 1105.73
  4513.5 1104.52  4530.9 1099.41  4548.9 1096.48  4579.2 1092.60  4642.9 1087.71
  4685.7 1086.03  4841.8 1085.58  4938.4 1083.28  4956.4 1082.84  4982.2 1079.98
  4984.0 1076.98  5016.0 1076.98  5017.8 1079.98  5028.9 1080.81  5035.7 1081.32
  5039.1 1086.10  5186.1 1090.91  5198.1 1091.60  5230.6 1096.70  5270.8 1107.33
  5281.5 1111.57  5339.0 1119.07  5361.7 1126.60  5376.3 1128.77  5395.0 1129.19
#Mann=7,-1,0
  4452.8    0.13       0  4511.5    0.07       0  4938.4    0.13       0
  4982.2    0.05       0  5017.8    0.13       0  5028.9    0.07       0
  5186.1    0.14       0
Bank Sta=4982.2,5017.8
XS Rating Curve= 0
Exp/Cntr=0.3,0.1

Type RM Length L Ch R = 1,5881,402,402,402
BEGIN DESCRIPTION:
Johnson Creek 19.0
END DESCRIPTION:
XS GIS Cut Line= 4
      1534303.80      1023081.26      1533706.07      1022783.81
      1533521.94      1022707.32      1533150.82      1022633.66
#Sta/Elev= 30
  4342.3 1133.38  4358.0 1124.65  4369.9 1117.18  4386.1 1109.06  4409.3 1096.38
  4422.5 1090.96  4428.4 1090.62  4467.6 1087.64  4507.8 1086.75  4591.5 1085.62
  4642.1 1085.85  4654.9 1084.85  4696.9 1084.54  4828.4 1084.25  4862.1 1084.81
  4925.8 1083.50  4960.0 1081.69  4982.1 1078.62  4983.9 1075.62  5016.1 1075.62
  5017.9 1078.62  5026.3 1080.07  5056.4 1085.27  5209.3 1088.00  5322.9 1089.31
  5449.2 1093.52  5491.5 1097.67  5502.3 1098.92  5532.8 1104.60  5587.7 1117.81
#Mann=7,-1,0
  4342.3    0.13       0  4428.4    0.07       0  4960.0    0.13       0
  4982.1    0.05       0  5017.9    0.13       0  5026.3    0.07       0
  5491.5    0.14       0
#XS Ineff=2,0
    0.00 4642.70 1096.30               0
Permanent Ineff=
       F       F
Bank Sta=4982.1,5017.9
XS Rating Curve= 0
Exp/Cntr=0.3,0.1

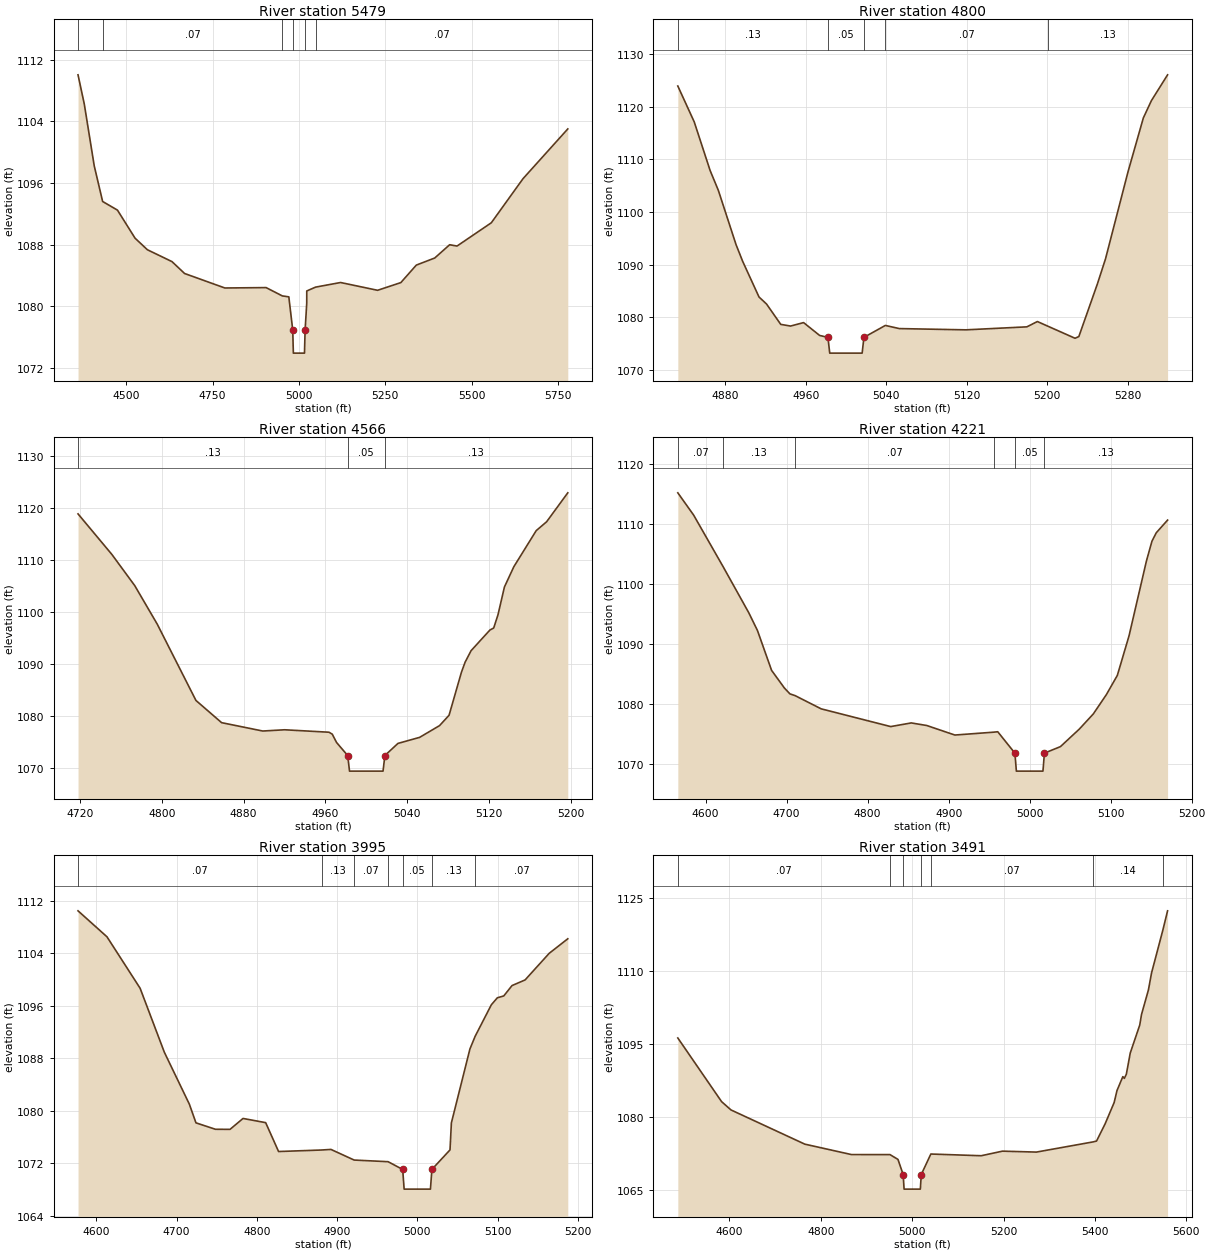
Type RM Length L Ch R = 1,5479,679,679,679
BEGIN DESCRIPTION:
Johnson Creek 18.0
END DESCRIPTION:
XS GIS Cut Line= 3
      1534575.74      1022653.49      1533609.76      1022367.38
      1533224.47      1022228.56
#Sta/Elev= 30
  4360.9 1110.04  4379.0 1106.25  4407.8 1098.23  4432.1 1093.61  4475.0 1092.49
  4525.9 1088.85  4561.6 1087.35  4632.8 1085.81  4669.2 1084.27  4785.7 1082.39
  4905.0 1082.44  4952.1 1081.36  4970.8 1081.24  4982.1 1076.94  4983.9 1073.94
  5016.1 1073.94  5017.9 1076.94  5022.6 1080.38  5022.7 1082.00  5048.0 1082.50
  5120.6 1083.10  5227.7 1082.09  5294.9 1083.09  5339.7 1085.36  5393.0 1086.28
  5436.1 1088.00  5457.5 1087.83  5556.7 1090.85  5648.4 1096.57  5777.9 1103.02
#Mann=6,-1,0
  4360.9    0.15       0  4432.1    0.07       0  4952.1    0.13       0
  4982.1    0.05       0  5017.9    0.13       0  5048.0    0.07       0
Bank Sta=4982.1,5017.9
XS Rating Curve= 0
Exp/Cntr=0.3,0.1

Type RM Length L Ch R = 1,4800,234,234,234
BEGIN DESCRIPTION:
Johnson Creek 16.0
END DESCRIPTION:
XS GIS Cut Line= 3
      1534034.72      1021911.29      1533785.39      1021874.46
      1533581.39      1021758.29
#Sta/Elev= 30
  4832.9 1123.97  4849.2 1117.15  4865.0 1107.90  4873.2 1104.11  4890.8 1093.78
  4897.4 1090.60  4913.6 1083.83  4921.1 1082.49  4935.2 1078.62  4945.0 1078.30
  4957.9 1078.96  4973.9 1076.51  4982.1 1076.15  4983.9 1073.15  5016.1 1073.15
  5017.9 1076.15  5039.2 1078.42  5053.0 1077.82  5119.2 1077.58  5179.8 1078.15
  5190.3 1079.16  5200.4 1078.30  5227.7 1075.98  5231.5 1076.30  5250.0 1086.35
  5258.0 1091.08  5280.4 1107.67  5295.6 1117.89  5303.6 1121.18  5319.7 1126.10
#Mann=5,-1,0
  4832.9    0.13       0  4982.1    0.05       0  5017.9    0.13       0
  5039.2    0.07       0  5200.4    0.13       0
Bank Sta=4982.1,5017.9
XS Rating Curve= 0
Exp/Cntr=0.3,0.1

Type RM Length L Ch R = 1,4566,345,345,345
BEGIN DESCRIPTION:
Johnson Creek 15.0
END DESCRIPTION:
XS GIS Cut Line= 3
      1534128.16      1021752.64      1534009.19      1021698.82
      1533674.87      1021599.66
#Sta/Elev= 30
  4717.9 1118.82  4751.0 1111.03  4773.4 1105.03  4795.4 1097.63  4833.3 1082.95
  4858.4 1078.68  4898.7 1077.07  4920.1 1077.31  4963.5 1076.84  4966.7 1076.47
  4970.9 1074.87  4981.8 1072.36  4983.6 1069.36  5016.4 1069.36  5018.2 1072.36
  5031.0 1074.69  5052.2 1075.85  5071.7 1078.11  5081.0 1080.10  5093.1 1088.36
  5096.7 1090.30  5102.6 1092.53  5121.0 1096.49  5124.7 1096.88  5128.9 1099.43
  5135.2 1104.77  5144.4 1108.66  5166.3 1115.60  5176.5 1117.31  5197.2 1122.87
#Mann=3,-1,0
  4717.9    0.13       0  4981.8    0.05       0  5018.2    0.13       0
Bank Sta=4981.8,5018.2
XS Rating Curve= 0
Exp/Cntr=0.3,0.1

Type RM Length L Ch R = 1,4221,226,226,226
BEGIN DESCRIPTION:
Johnson Creek 14.0
END DESCRIPTION:
XS GIS Cut Line= 3
      1534354.77      1021452.35      1533884.54      1021302.22
      1533791.07      1021242.74
#Sta/Elev= 30
  4565.8 1115.26  4585.3 1111.55  4622.0 1102.87  4653.4 1095.25  4664.1 1092.29
  4681.5 1085.65  4697.3 1082.71  4704.1 1081.73  4710.6 1081.43  4742.7 1079.23
  4828.5 1076.27  4853.9 1076.88  4873.0 1076.45  4907.7 1074.86  4955.9 1075.34
  4960.6 1075.41  4981.8 1071.84  4983.6 1068.84  5016.4 1068.84  5018.2 1071.84
  5038.0 1072.93  5061.2 1075.84  5078.6 1078.39  5094.8 1081.63  5108.2 1084.81
  5122.6 1091.39  5144.1 1103.89  5150.9 1107.18  5156.2 1108.59  5170.2 1110.71
#Mann=6,-1,0
  4565.8    0.07       0  4622.0    0.13       0  4710.6    0.07       0
  4955.9    0.13       0  4981.8    0.05       0  5018.2    0.13       0
Bank Sta=4981.8,5018.2
XS Rating Curve= 0
Exp/Cntr=0.3,0.1

Type RM Length L Ch R = 1,3995,504,504,504
BEGIN DESCRIPTION:
Johnson Creek 13.0
END DESCRIPTION:
XS GIS Cut Line= 4
      1534414.27      1021259.71      1534238.65      1021171.91
      1533941.20      1021086.92      1533842.06      1021120.91
#Sta/Elev= 30
  4577.1 1110.45  4613.2 1106.49  4654.5 1098.65  4684.7 1088.90  4715.9 1080.98
  4724.1 1078.14  4748.4 1077.16  4766.6 1077.15  4782.8 1078.81  4811.0 1078.17
  4827.1 1073.77  4880.6 1074.00  4892.4 1074.09  4921.3 1072.47  4963.6 1072.22
  4981.8 1071.04  4983.6 1068.04  5016.4 1068.04  5018.2 1071.04  5040.8 1074.02
  5042.5 1078.13  5065.6 1089.39  5072.0 1091.30  5092.3 1096.13  5099.8 1097.20
  5107.8 1097.48  5118.1 1099.06  5134.4 1099.92  5164.4 1103.97  5187.6 1106.19
#Mann=7,-1,0
  4577.1    0.07       0  4880.6    0.13       0  4921.3    0.07       0
  4963.6    0.13       0  4981.8    0.05       0  5018.2    0.13       0
  5072.0    0.07       0
Bank Sta=4981.8,5018.2
XS Rating Curve= 0
Exp/Cntr=0.3,0.1

Type RM Length L Ch R = 1,3491,484,484,484
BEGIN DESCRIPTION:
Johnson Creek 12.0
END DESCRIPTION:
XS GIS Cut Line= 3
      1534776.33      1021030.26      1534586.53      1020891.45
      1533816.01      1020565.68
#Sta/Elev= 30
  4487.1 1096.19  4582.9 1083.11  4603.4 1081.41  4765.0 1074.38  4867.0 1072.24
  4951.4 1072.23  4968.8 1071.25  4980.2 1068.14  4982.2 1065.14  5017.8 1065.14
  5019.8 1068.14  5040.8 1072.35  5151.0 1072.00  5197.4 1072.94  5271.8 1072.75
  5396.3 1074.85  5403.4 1075.02  5422.2 1078.57  5441.9 1082.93  5448.1 1085.39
  5460.9 1088.25  5464.2 1087.89  5468.6 1088.76  5477.1 1093.09  5497.9 1098.85
  5501.8 1101.03  5516.9 1106.07  5523.7 1109.54  5548.5 1118.36  5558.8 1122.31
#Mann=7,-1,0
  4487.1    0.07       0  4951.4    0.13       0  4980.2    0.05       0
  5019.8    0.13       0  5040.8    0.07       0  5396.3    0.14       0
  5548.5    0.07       0
Bank Sta=4980.2,5019.8
XS Rating Curve= 0
Exp/Cntr=0.3,0.1

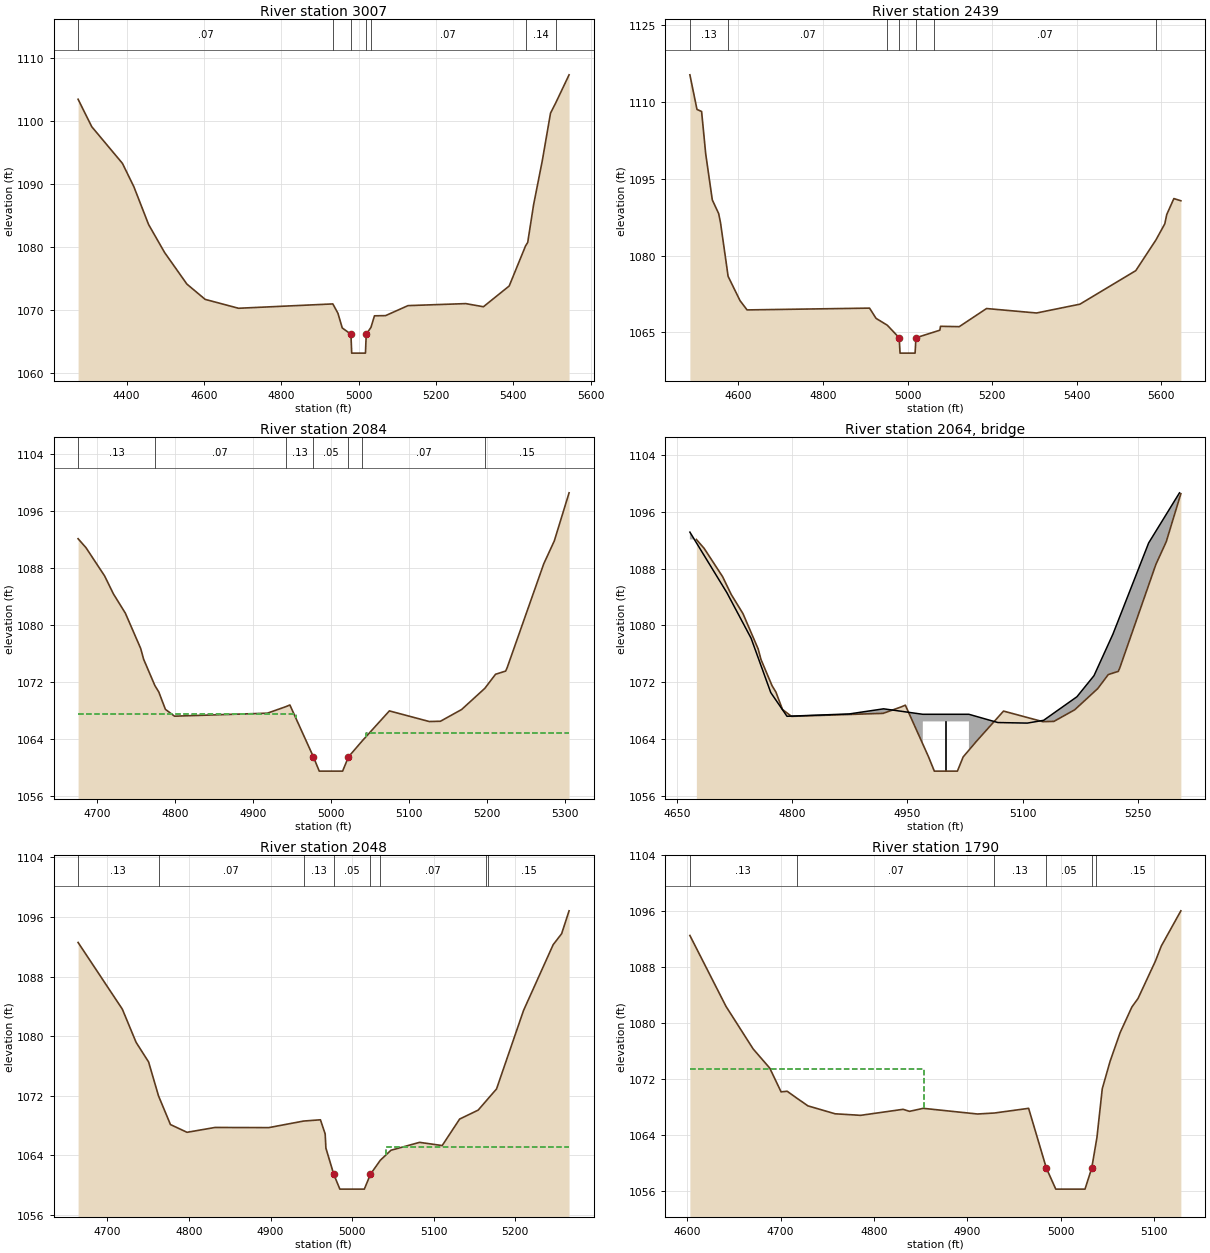
Type RM Length L Ch R = 1,3007,568,568,568
BEGIN DESCRIPTION:
Johnson Creek 10.0
END DESCRIPTION:
XS GIS Cut Line= 3
      1535170.13      1020466.52      1534929.31      1020460.85
      1533940.66      1020174.74
#Sta/Elev= 30
  4274.4 1103.47  4309.8 1099.10  4389.1 1093.28  4418.6 1089.58  4456.8 1083.56
  4498.1 1079.12  4555.9 1074.09  4603.2 1071.66  4689.4 1070.25  4933.4 1070.94
  4946.6 1069.45  4957.8 1067.12  4980.2 1066.12  4982.2 1063.12  5017.8 1063.12
  5019.8 1066.12  5032.0 1067.21  5041.1 1069.05  5069.8 1069.08  5127.8 1070.67
  5277.2 1070.99  5322.9 1070.49  5389.6 1073.79  5432.0 1080.17  5437.5 1080.71
  5452.8 1086.73  5475.2 1093.69  5496.5 1101.26  5510.0 1102.89  5544.5 1107.35
#Mann=7,-1,0
  4274.4    0.07       0  4933.4    0.13       0  4980.2    0.05       0
  5019.8    0.13       0  5032.0    0.07       0  5432.0    0.14       0
  5510.0    0.07       0
Bank Sta=4980.2,5019.8
XS Rating Curve= 0
Exp/Cntr=0.3,0.1

Type RM Length L Ch R = 1,2439,355,355,355
BEGIN DESCRIPTION:
Johnson Creek 8.0
END DESCRIPTION:
XS GIS Cut Line= 4
      1535218.24      1020035.92      1534997.30      1020044.42
      1534425.06      1019902.78      1534090.82      1019797.98
#Sta/Elev= 30
  4485.3 1115.31  4502.1 1108.55  4513.0 1108.15  4522.8 1099.82  4538.3 1090.88
  4553.3 1088.22  4557.7 1086.45  4575.7 1075.95  4603.8 1071.21  4620.5 1069.39
  4910.1 1069.74  4925.5 1067.74  4952.1 1066.40  4980.2 1063.95  4982.2 1060.95
  5017.8 1060.95  5019.8 1063.95  5061.6 1065.04  5076.4 1065.43  5077.9 1066.19
  5122.2 1066.12  5186.7 1069.66  5305.0 1068.79  5407.5 1070.51  5539.6 1077.06
  5587.4 1083.08  5608.2 1086.21  5612.8 1088.02  5629.7 1091.14  5646.2 1090.71
#Mann=7,-1,0
  4485.3    0.13       0  4575.7    0.07       0  4952.1    0.13       0
  4980.2    0.05       0  5019.8    0.13       0  5061.6    0.07       0
  5587.4    0.14       0
Bank Sta=4980.2,5019.8
XS Rating Curve= 0
Exp/Cntr=0.5,0.3

Type RM Length L Ch R = 1,2084,36,36,36
BEGIN DESCRIPTION:
Small Bridge (John) us
END DESCRIPTION:
XS GIS Cut Line= 4
      1535078.35      1019673.02      1534834.13      1019636.92
      1534675.89      1019634.79      1534484.71      1019515.83
#Sta/Elev= 30
  4675.4 1092.11  4685.5 1090.86  4709.5 1086.88  4720.7 1084.38  4736.1 1081.66
  4755.8 1076.70  4759.5 1075.21  4774.0 1071.50  4778.9 1070.63  4787.5 1068.17
  4799.2 1067.21  4918.4 1067.63  4941.7 1068.53  4947.3 1068.78  4977.5 1061.50
  4985.0 1059.50  5015.0 1059.50  5022.5 1061.50  5040.3 1063.76  5075.0 1067.95
  5126.2 1066.46  5140.6 1066.50  5167.7 1068.14  5197.5 1071.11  5211.3 1073.09
  5224.3 1073.54  5226.3 1074.04  5273.2 1088.59  5286.7 1091.79  5305.7 1098.55
#Mann=7,-1,0
  4675.4    0.13       0  4774.0    0.07       0  4941.7    0.13       0
  4977.5    0.05       0  5022.5    0.13       0  5040.3    0.07       0
  5197.5    0.15       0
#XS Ineff=2,0
    0.00 4955.00 1067.50 5045.00    0.00 1064.87
Permanent Ineff=
       F       F
Bank Sta=4977.5,5022.5
XS Rating Curve= 0
Exp/Cntr=0.5,0.3

Type RM Length L Ch R =3,2064,,,
BEGIN DESCRIPTION:
Small Bridge (John) TOR
Structure ID: Johnson_Estimate
Approximate Survey Structure
END DESCRIPTION:
Bridge Culvert--1,0,-1,-1,0
Deck Dist Width WeirC Skew NumUp NumDn MinLoCord MaxHiCord MaxSubmerge Is_Ogee
15,10,3,,19,19,,,0.95,0,1,1,,,
  4667.0  4715.2  4746.6  4772.2  4793.3  4874.3  4919.0  4970.0  4970.0  5030.0
  5030.0  5067.6  5105.9  5127.1  5170.5  5192.7  5217.3  5263.8  5303.9
 1093.14 1084.60 1078.21 1070.56 1067.22 1067.55 1068.27 1067.50 1067.50 1067.50
 1067.50 1066.34 1066.26 1066.65 1069.97 1072.94 1078.78 1091.62 1098.67
 1039.50 1039.50 1039.50 1039.50 1039.50 1039.50 1039.50 1039.50 1066.50 1066.50
 1039.50 1039.50 1039.50 1039.50 1039.50 1039.50 1039.50 1039.50 1039.50
  4667.0  4715.2  4746.6  4772.2  4793.3  4874.3  4919.0  4970.0  4970.0  5030.0
  5030.0  5067.6  5105.9  5127.1  5170.5  5192.7  5217.3  5263.8  5303.9
 1093.14 1084.60 1078.21 1070.56 1067.22 1067.55 1068.27 1067.50 1067.50 1067.50
 1067.50 1066.34 1066.26 1066.65 1069.97 1072.94 1078.78 1091.62 1098.67
 1039.50 1039.50 1039.50 1039.50 1039.50 1039.50 1039.50 1039.50 1066.50 1066.50
 1039.50 1039.50 1039.50 1039.50 1039.50 1039.50 1039.50 1039.50 1039.50
Pier Skew, UpSta & Num, DnSta & Num=,5000,2,5000,2,0,0,0,0,0
       1       1
 1057.50 1067.00
       1       1
 1057.25 1067.00
BR Coef=1,1,0,1.25,0,,,0.8,0,2,0,
WSPro=,,,, 1 ,,,, 0 ,,,, 0 ,,,,-1 ,-1 ,-1 , 0 , 0 , 0 , 0 , 0
BC Design=,,0,,0,,,,,,

Type RM Length L Ch R = 1,2048,258,258,258
BEGIN DESCRIPTION:
Small Bridge (John) ds
END DESCRIPTION:
XS GIS Cut Line= 4
      1535079.43      1019653.91      1534840.50      1019605.06
      1534683.33      1019597.62      1534502.76      1019510.53
#Sta/Elev= 30
  4664.2 1092.57  4718.4 1083.62  4735.3 1079.16  4750.6 1076.53  4762.8 1071.96
  4777.4 1068.12  4797.7 1067.08  4832.0 1067.73  4897.9 1067.71  4940.5 1068.59
  4961.2 1068.76  4967.0 1066.86  4967.9 1064.96  4977.5 1061.45  4985.0 1059.45
  5015.0 1059.45  5022.5 1061.45  5034.6 1063.33  5047.6 1064.67  5082.7 1065.73
  5110.4 1065.30  5131.8 1068.86  5154.5 1070.06  5164.4 1071.31  5166.5 1071.58
  5177.0 1072.90  5210.1 1083.44  5246.4 1092.27  5256.8 1093.75  5265.9 1096.82
#Mann=8,-1,0
  4664.2    0.13       0  4762.8    0.07       0  4940.5    0.13       0
  4977.5    0.05       0  5022.5    0.13       0  5034.6    0.07       0
  5164.4    0.13       0  5166.5    0.15       0
#XS Ineff=2,0
    0.00 4959.00 1067.50 5041.00    0.00 1065.04
Permanent Ineff=
       F       F
Bank Sta=4977.5,5022.5
XS Rating Curve= 0
Exp/Cntr=0.5,0.3

Type RM Length L Ch R = 1,1790,376,376,376
BEGIN DESCRIPTION:
Johnson Creek 6.0
END DESCRIPTION:
XS GIS Cut Line= 3
      1535139.49      1019485.16      1534710.13      1019325.60
      1534643.44      1019312.55
#Sta/Elev= 30
  4602.9 1092.56  4641.6 1082.43  4670.7 1076.35  4688.5 1073.61  4700.6 1070.22
  4707.1 1070.31  4717.3 1069.34  4729.4 1068.22  4758.5 1067.09  4785.8 1066.87
  4831.3 1067.73  4838.2 1067.44  4852.9 1067.87  4911.0 1067.06  4929.1 1067.20
  4965.8 1067.87  4984.8 1059.33  4994.9 1056.33  5026.2 1056.33  5033.4 1059.33
  5037.6 1062.62  5039.0 1063.72  5044.7 1070.67  5053.1 1074.60  5063.8 1078.67
  5076.4 1082.34  5083.0 1083.56  5101.7 1088.92  5107.9 1091.04  5128.9 1096.08
#Mann=6,-1,0
  4602.9    0.13       0  4717.3    0.07       0  4929.1    0.13       0
  4984.8    0.05       0  5033.4    0.13       0  5037.6    0.15       0
#XS Ineff=2,0
    0.00 4853.40 1073.45               0
Permanent Ineff=
       F       F
Bank Sta=4984.8,5033.4
XS Rating Curve= 0
Exp/Cntr=0.3,0.1

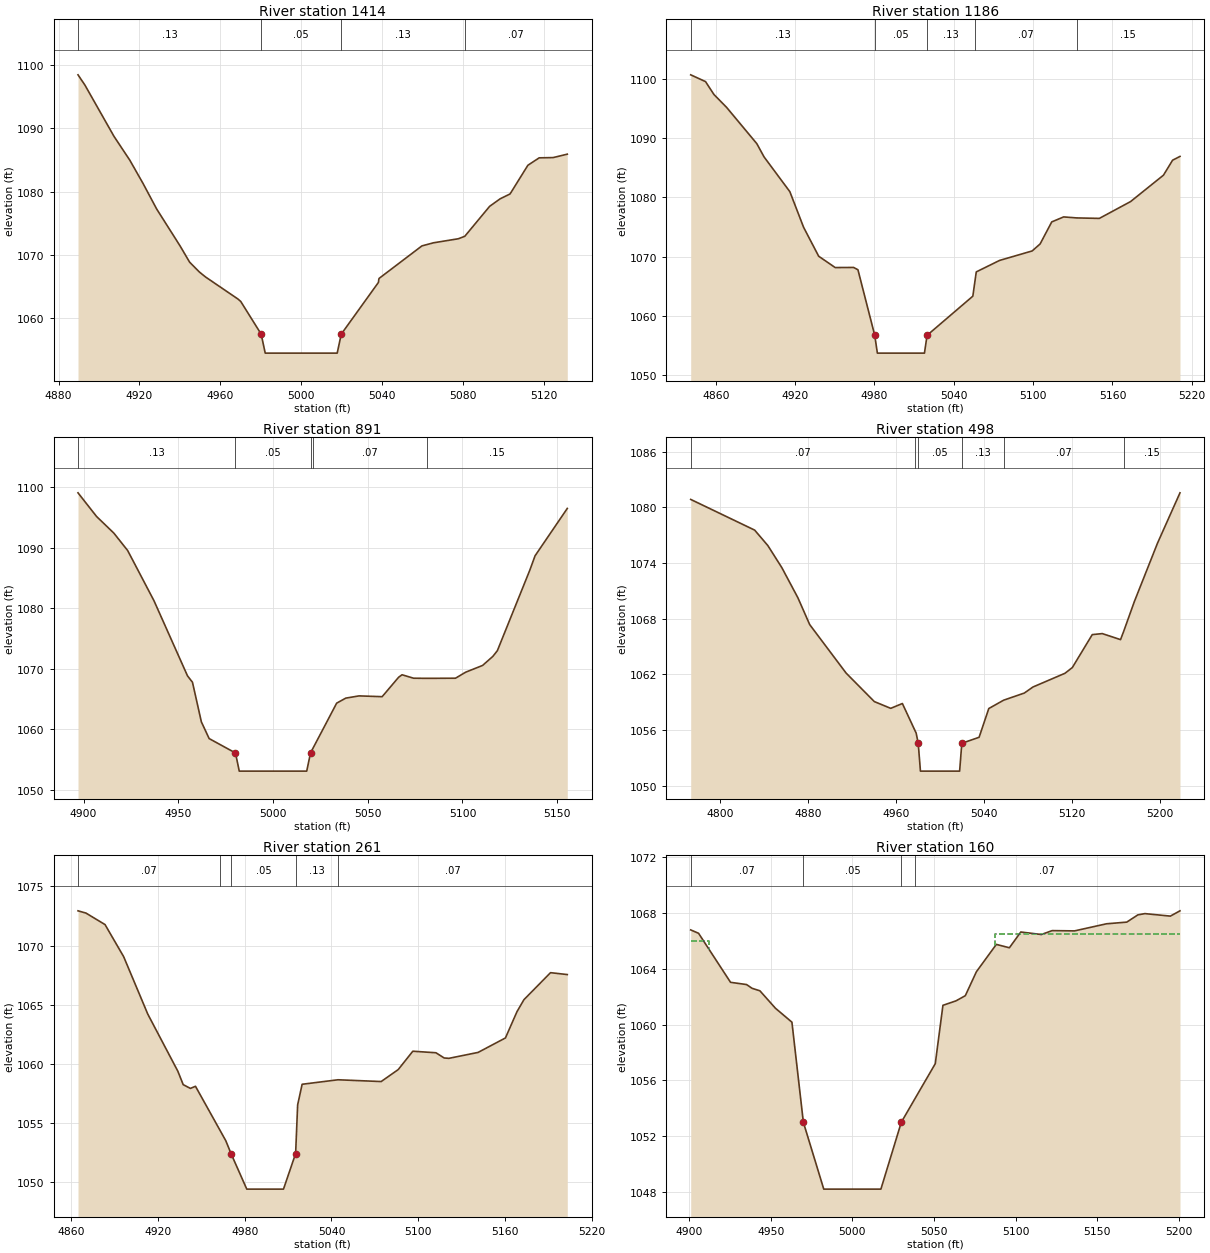
Type RM Length L Ch R = 1,1414,228,228,228
BEGIN DESCRIPTION:
Johnson Creek 5.0
END DESCRIPTION:
XS GIS Cut Line= 3
      1535100.30      1019103.68      1535061.13      1019084.83
      1534882.70      1018997.78
#Sta/Elev= 30
  4889.6 1098.48  4893.0 1096.87  4907.4 1088.75  4915.2 1084.99  4921.8 1081.28
  4928.5 1077.26  4940.1 1071.41  4944.8 1068.85  4949.6 1067.30  4952.7 1066.50
  4968.7 1063.02  4970.1 1062.63  4980.2 1057.46  4982.2 1054.46  5017.8 1054.46
  5019.8 1057.46  5038.2 1065.65  5038.4 1066.18  5038.6 1066.30  5059.7 1071.42
  5065.4 1071.91  5077.7 1072.55  5080.9 1072.94  5093.2 1077.68  5098.4 1078.87
  5103.3 1079.64  5112.1 1084.17  5117.7 1085.35  5124.6 1085.39  5131.6 1085.93
#Mann=4,-1,0
  4889.6    0.13       0  4980.2    0.05       0  5019.8    0.13       0
  5080.9    0.07       0
Bank Sta=4980.2,5019.8
XS Rating Curve= 0
Exp/Cntr=0.3,0.1

Type RM Length L Ch R = 1,1186,295,295,295
BEGIN DESCRIPTION:
Johnson Creek 4.0
END DESCRIPTION:
XS GIS Cut Line= 3
      1535249.35      1018854.21      1535127.56      1018857.11
      1534882.39      1018817.94
#Sta/Elev= 30
  4841.0 1100.62  4852.2 1099.48  4858.6 1097.30  4868.1 1095.15  4891.0 1089.03
  4896.5 1086.79  4916.0 1080.94  4926.4 1074.94  4937.8 1070.07  4950.3 1068.16
  4964.2 1068.18  4967.5 1067.79  4980.2 1056.75  4982.2 1053.75  5017.8 1053.75
  5019.8 1056.75  5054.4 1063.34  5056.3 1066.33  5057.0 1067.43  5074.6 1069.36
  5099.3 1070.96  5105.3 1072.14  5114.1 1075.85  5123.1 1076.69  5133.0 1076.52
  5150.1 1076.44  5173.7 1079.27  5198.6 1083.72  5205.5 1086.24  5211.1 1086.88
#Mann=5,-1,0
  4841.0    0.13       0  4980.2    0.05       0  5019.8    0.13       0
  5056.3    0.07       0  5133.0    0.15       0
Bank Sta=4980.2,5019.8
XS Rating Curve= 0
Exp/Cntr=0.3,0.1

Type RM Length L Ch R = 1,891,393,393,393
BEGIN DESCRIPTION:
Johnson Creek 3.0
END DESCRIPTION:
XS GIS Cut Line= 3
      1535268.51      1018604.72      1535098.84      1018545.27
      1535024.90      1018519.17
#Sta/Elev= 30
  4897.1 1099.04  4906.9 1095.13  4916.0 1092.39  4923.3 1089.51  4937.2 1081.21
  4954.9 1068.79  4957.5 1067.75  4962.2 1061.20  4966.3 1058.44  4980.2 1056.06
  4982.2 1053.06  5017.8 1053.06  5019.8 1056.06  5021.0 1056.78  5033.6 1064.29
  5038.4 1065.12  5045.4 1065.49  5057.6 1065.36  5066.3 1068.57  5068.1 1068.98
  5074.2 1068.41  5081.2 1068.39  5096.3 1068.41  5101.7 1069.41  5110.6 1070.52
  5116.0 1072.01  5118.4 1072.96  5135.5 1086.24  5138.3 1088.64  5155.3 1096.46
#Mann=5,-1,0
  4897.1    0.13       0  4980.2    0.05       0  5019.8    0.13       0
  5021.0    0.07       0  5081.2    0.15       0
Bank Sta=4980.2,5019.8
XS Rating Curve= 0
Exp/Cntr=0.3,0.1

Type RM Length L Ch R = 1,498,237,237,237
BEGIN DESCRIPTION:
Johnson Creek 2.0
END DESCRIPTION:
XS GIS Cut Line= 3
      1535522.40      1018204.41      1535397.63      1018211.67
      1535080.02      1018176.86
#Sta/Elev= 30
  4773.5 1080.87  4831.6 1077.56  4843.6 1075.89  4856.3 1073.51  4870.9 1070.26
  4881.6 1067.37  4914.7 1062.14  4940.3 1059.07  4955.2 1058.34  4965.8 1058.86
  4977.3 1055.93  4978.3 1055.68  4980.2 1054.57  4982.2 1051.57  5017.8 1051.57
  5019.8 1054.57  5035.5 1055.22  5044.3 1058.32  5057.8 1059.22  5076.6 1059.99
  5084.4 1060.64  5113.5 1062.12  5120.2 1062.74  5138.3 1066.29  5147.4 1066.40
  5164.0 1065.75  5166.9 1066.66  5176.5 1069.84  5197.6 1076.16  5218.0 1081.58
#Mann=6,-1,0
  4773.5    0.07       0  4977.3    0.13       0  4980.2    0.05       0
  5019.8    0.13       0  5057.8    0.07       0  5166.9    0.15       0
Bank Sta=4980.2,5019.8
XS Rating Curve= 0
Exp/Cntr=0.3,0.1

Type RM Length L Ch R = 1,261,101,101,101
BEGIN DESCRIPTION:
Johnson Creek 1.5
END DESCRIPTION:
XS GIS Cut Line= 3
      1535475.95      1018036.16      1535323.66      1017972.35
      1535156.91      1017924.50
#Sta/Elev= 30
  4864.6 1072.93  4870.1 1072.74  4883.3 1071.77  4896.2 1069.06  4912.9 1064.21
  4933.7 1059.39  4937.4 1058.26  4942.4 1057.94  4945.9 1058.12  4962.8 1054.42
  4966.9 1053.52  4970.5 1052.44  4981.4 1049.44  5006.8 1049.44  5015.2 1052.44
  5016.6 1056.55  5019.7 1058.29  5044.5 1058.67  5074.4 1058.52  5086.2 1059.53
  5096.3 1061.08  5112.3 1060.95  5118.0 1060.51  5121.3 1060.48  5141.5 1060.98
  5160.4 1062.20  5168.4 1064.42  5173.2 1065.43  5191.6 1067.71  5203.2 1067.55
#Mann=5,-1,0
  4864.6    0.07       0  4962.8    0.13       0  4970.5    0.05       0
  5015.2    0.13       0  5044.5    0.07       0
Bank Sta=4970.5,5015.2
XS Rating Curve= 0
Exp/Cntr=0.5,0.3

Type RM Length L Ch R = 1,160,80,80,80
BEGIN DESCRIPTION:
Riverside Dr (John) us
END DESCRIPTION:
XS GIS Cut Line= 4
      1535474.46      1017938.97      1535438.25      1017928.83
      1535313.51      1017831.66      1535246.81      1017751.90
#Sta/Elev= 30
  4901.0 1066.80  4905.8 1066.56  4925.4 1063.04  4935.2 1062.88  4938.6 1062.61
  4943.4 1062.43  4952.9 1061.18  4963.0 1060.18  4970.0 1053.00  4982.5 1048.20
  5017.5 1048.20  5030.0 1053.00  5038.1 1054.64  5050.8 1057.20  5055.5 1061.39
  5063.5 1061.71  5069.2 1062.08  5076.0 1063.80  5088.2 1065.76  5096.2 1065.52
  5103.2 1066.65  5115.8 1066.47  5122.4 1066.75  5136.1 1066.73  5155.7 1067.24
  5168.1 1067.36  5174.9 1067.88  5179.2 1067.97  5194.8 1067.79  5200.7 1068.17
#Mann=4,-1,0
  4901.0    0.07       0  4970.0    0.05       0  5030.0    0.07       0
  5038.1    0.07       0
#XS Ineff=2,0
    0.00 4912.50 1065.98 5087.50    0.00 1066.51
Permanent Ineff=
       F       F
Bank Sta=4970,5030
XS Rating Curve= 0
Exp/Cntr=0.5,0.3

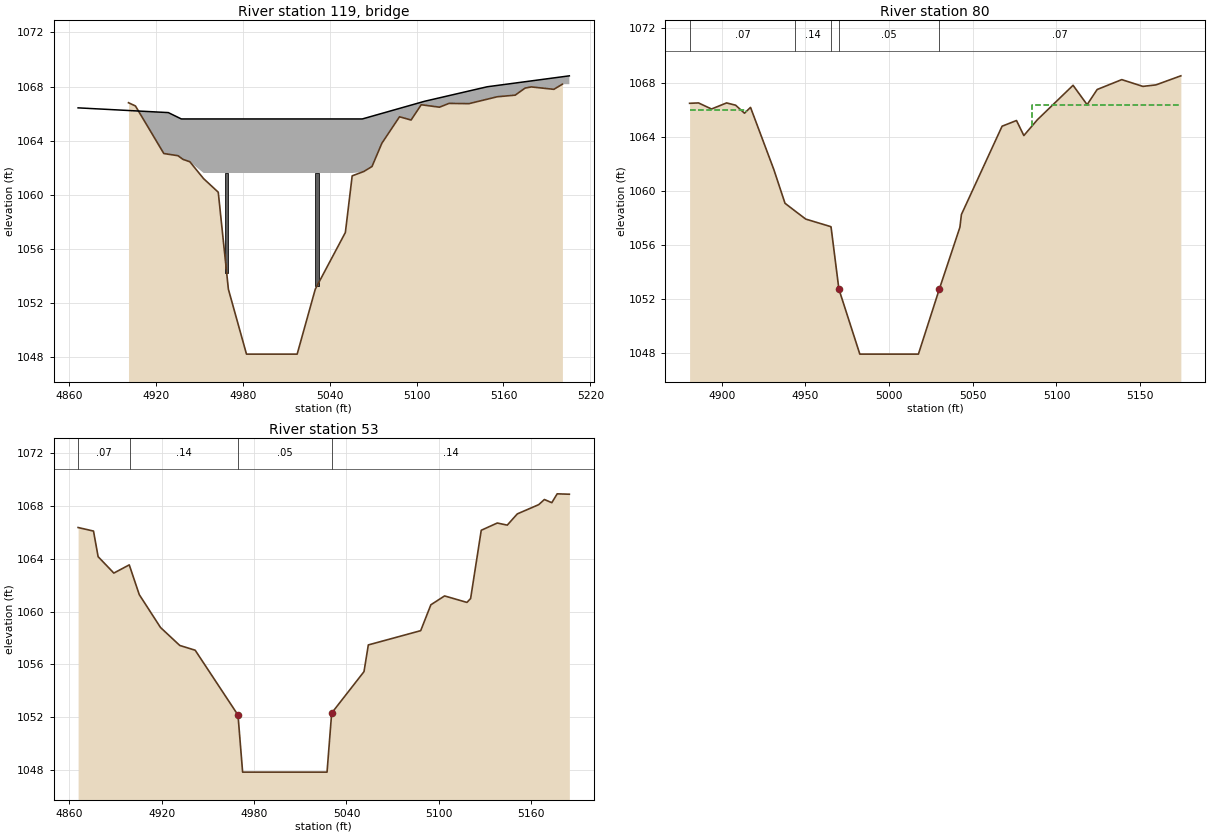
Type RM Length L Ch R =3,119,,,
BEGIN DESCRIPTION:
Riverside Dr (John) TOR
Structure ID: LDS_JC_01
Approximate Survey Structure
END DESCRIPTION:
Bridge Culvert--1,0,-1,-1,0
Deck Dist Width WeirC Skew NumUp NumDn MinLoCord MaxHiCord MaxSubmerge Is_Ogee
25,32,3,,9,9,,,0.95,0,1,1,,,
  4866.2  4928.5  4937.5  4937.5  5062.5  5062.5  5105.6  5148.7  5205.5
 1066.42 1066.07 1065.60 1065.60 1065.60 1065.60 1066.91 1067.98 1068.79
 1028.20 1028.20 1028.20 1061.60 1061.60 1028.20 1028.20 1028.20 1028.20
  4866.2  4928.5  4937.5  4937.5  5062.5  5062.5  5105.6  5148.7  5205.5
 1066.42 1066.07 1065.60 1065.60 1065.60 1065.60 1066.91 1067.98 1068.79
 1028.20 1028.20 1028.20 1061.60 1061.60 1028.20 1028.20 1028.20 1028.20
Pier Skew, UpSta & Num, DnSta & Num=,4968.8,2,4968.8,2,0,0,0,0,0
     2.5     2.5
 1050.00 1061.60
     2.5     2.5
 1050.00 1061.60
Pier Skew, UpSta & Num, DnSta & Num=,5031.3,2,5031.3,2,0,0,0,0,0
     2.5     2.5
 1050.00 1061.60
     2.5     2.5
 1053.13 1061.60
Abutment Skew #Up #Dn=,2,2
  4937.5  4957.5
 1061.60 1060.70
  4937.5  4957.5
 1061.60 1057.66
Abutment Skew #Up #Dn=,2,2
  5042.5  5062.5
 1054.76 1061.60
  5042.5  5062.5
 1057.53 1061.60
BR Coef=1,1,0,1.25,0,,,0.8,0,2,0,
WSPro=,,,, 1 ,,,, 0 ,,,, 0 ,,,,-1 ,-1 ,-1 , 0 , 0 , 0 , 0 , 0
BC Design=,,0,,0,,,,,,

Type RM Length L Ch R = 1,80,27,27,27
BEGIN DESCRIPTION:
Riverside Dr (John) ds
END DESCRIPTION:
XS GIS Cut Line= 4
      1535478.86      1017902.73      1535441.15      1017843.26
      1535371.53      1017788.14      1535252.60      1017725.78
#Sta/Elev= 30
  4880.8 1066.47  4886.1 1066.50  4893.9 1066.05  4902.9 1066.50  4908.3 1066.33
  4913.6 1065.74  4917.2 1066.17  4931.1 1061.59  4937.8 1059.09  4943.8 1058.52
  4950.2 1057.92  4965.0 1057.37  4965.3 1057.35  4970.0 1052.75  4982.5 1047.95
  5017.5 1047.95  5030.0 1052.75  5042.3 1057.32  5043.2 1058.26  5067.5 1064.78
  5076.1 1065.20  5080.5 1064.09  5088.6 1065.26  5109.9 1067.80  5118.3 1066.37
  5124.3 1067.49  5139.0 1068.22  5151.6 1067.72  5159.4 1067.83  5174.3 1068.50
#Mann=5,-1,0
  4880.8    0.07       0  4943.8    0.14       0  4965.0    0.07       0
  4970.0    0.05       0  5030.0    0.07       0
#XS Ineff=2,0
    0.00 4914.50 1065.99 5085.50    0.00 1066.36
Permanent Ineff=
       F       F
Bank Sta=4970,5030
XS Rating Curve= 0
Exp/Cntr=0.5,0.3

Type RM Length L Ch R = 1,53,0,0,0
BEGIN DESCRIPTION:
Johnson Creek 1.0
END DESCRIPTION:
XS GIS Cut Line= 4
      1535486.12      1017895.50      1535445.50      1017812.80
      1535377.33      1017760.58      1535245.34      1017711.27
#Sta/Elev= 30
  4865.8 1066.37  4875.8 1066.10  4878.8 1064.16  4889.0 1062.92  4899.0 1063.54
  4899.3 1063.44  4905.5 1061.29  4919.3 1058.80  4931.8 1057.44  4941.8 1057.08
  4969.6 1052.17  4972.6 1047.85  5027.4 1047.85  5030.4 1052.32  5051.4 1055.46
  5054.2 1057.48  5088.2 1058.56  5094.8 1060.52  5103.7 1061.19  5118.2 1060.70
  5120.6 1060.99  5127.5 1066.16  5137.9 1066.71  5144.4 1066.55  5150.9 1067.40
  5164.8 1068.10  5168.5 1068.49  5173.3 1068.25  5176.8 1068.92  5184.7 1068.89
#Mann=4,-1,0
  4865.8    0.07       0  4899.3    0.14       0  4969.6    0.05       0
  5030.4    0.14       0
Bank Sta=4969.6,5030.4
XS Rating Curve= 0
Exp/Cntr=0.3,0.1

Chan Stop Cuts=-1