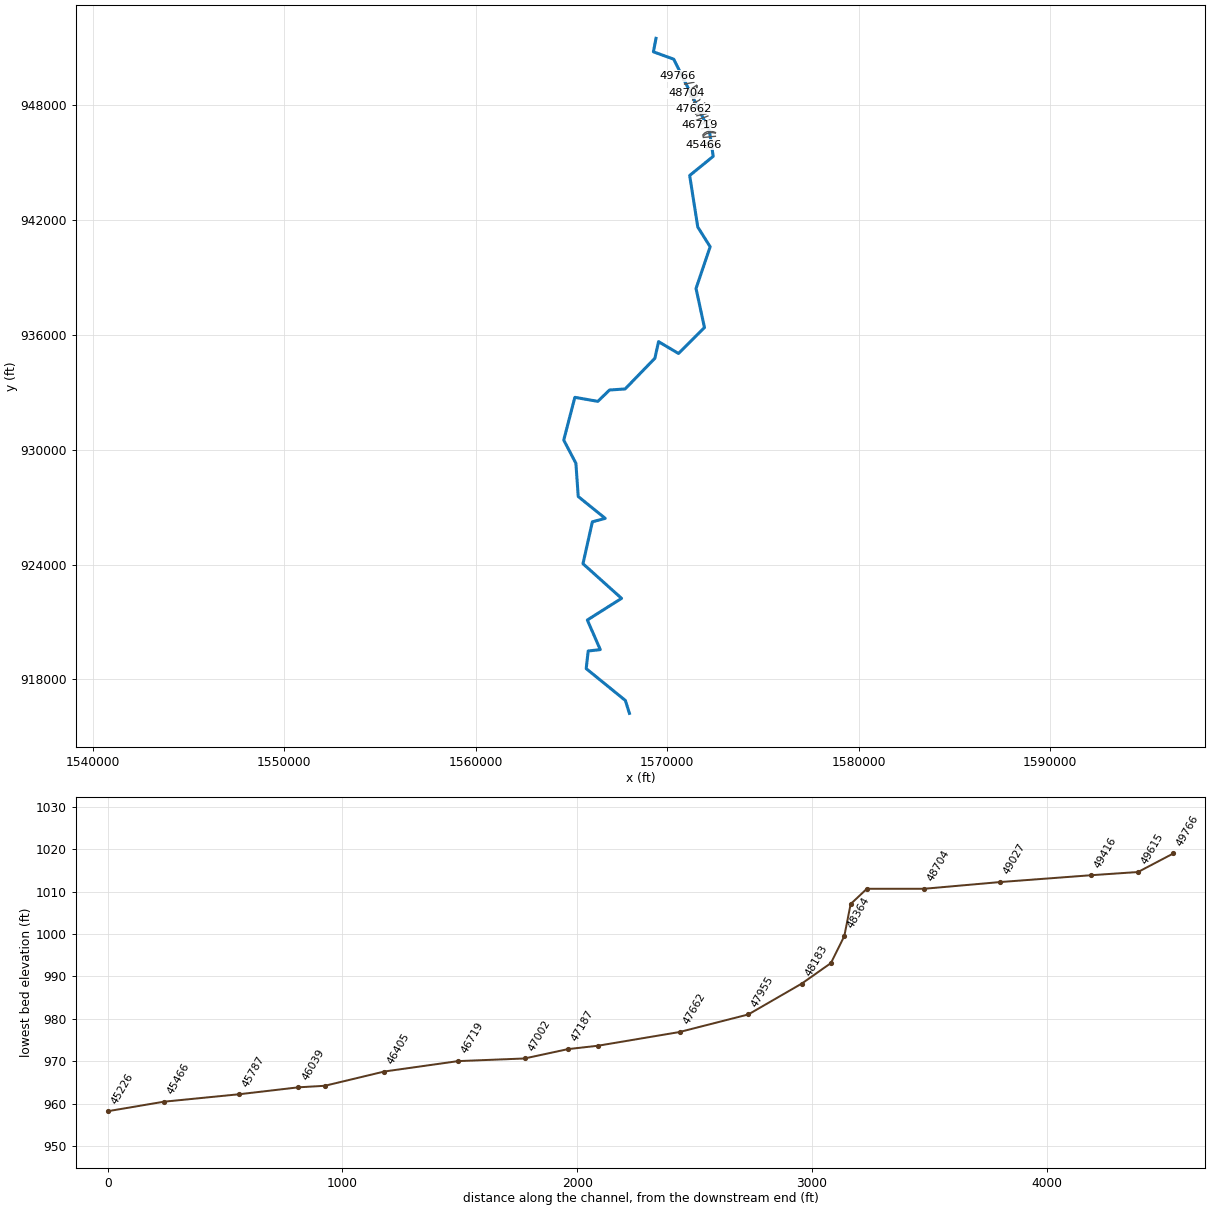
--- Grassy Creek.prj (project) ---

Proj Title=Grassy Creek Limited Detail Study
Current Plan=p01
Default Exp/Contr=0.3,0.1
English Units
Geom File=g01
Flow File=f01
Plan File=p01
Y Axis Title=Elevation
X Axis Title(PF)=Main Channel Distance
X Axis Title(XS)=Station
BEGIN DESCRIPTION:
Grassy Creek
END DESCRIPTION:
DSS Export Rating Curves= 0
DSS Export Rating Curve Sorted= 0
DSS Export Volume Flow Curves= 0
DXF OffsetX= 0
DXF OffsetY= 0
DXF ScaleX= 1
DXF ScaleY= 10

--- Grassy Creek.p01 (plan) ---

Plan Title=Floodway Run
Program Version=3.12
Short Identifier=Floodway
Geom File=g01
Flow File=f01
Subcritical Flow
K Sum by GR= 0
Std Step Tol= 0.01
Critical Tol= 0.01
Num of Std Step Trials= 20
Max Error Tol= 0.3
Flow Tol Ratio= 0.001
Split Flow NTrial= 30
Split Flow Tol= 0.02
Split Flow Ratio= 0.02
Log Output Level= 0
Friction Slope Method= 1
Unsteady Friction Slope Method= 2
Unsteady Bridges Friction Slope Method= 1
Parabolic Critical Depth
Global Vel Dist= 0 , 0 , 0
Global Log Level= 0
CheckData=True
Encroach Param=-1 ,5,5, 2
Encroach River=Grassy Creek
Encroach Reach=Reach-1
Encroach Node=49766
       1    4982  5013.6
Encroach Node=49615
       1    4976  5015.7
Encroach Node=49416
       1    4931    5057
Encroach Node=49027
       1  4889.8    5105
Encroach Node=48704
       1    4865    5181
Encroach Node=48460
       1  4863.5    5195
Encroach Node=48391
       1  4991.5  5008.5
Encroach Node=48364
       1  4993.5    5100
Encroach Node=48307
       1    4995    5090
Encroach Node=48183
       1    4976    5033
Encroach Node=47955
       1 4976.37  5009.3
Encroach Node=47662
       1    4943    5009
Encroach Node=47314
       1 4957.34 5028.02
Encroach Node=47187
       1 4977.81    5009
Encroach Node=47002
       1 4940.39    5009
Encroach Node=46719
       1    4930    5009
Encroach Node=46405
       1 4877.01    5009
Encroach Node=46151
       1    4865  5013.3
Encroach Node=46039
       1    4860  5013.3
Encroach Node=45787
       1 4824.27  5009.3
Encroach Node=45466
       1 4842.04  5009.3
Encroach Node=45226
       1 4876.63  5009.3
Encroach Node=44989
       1 4899.94 5016.26
Encroach Node=44726
       1 4915.93 5009.65
Encroach Node=44275
       1  4990.7 5038.79
Encroach Node=44036
       1 4977.43 5033.31
Encroach Node=43597
       1 4931.72 5023.19
Encroach Node=43341
       1    4900  5009.3
Encroach Node=43112
       1  4975.5  5024.5
Encroach Node=42835
       1    4988    5012
Encroach Node=42755
       1    4992  5006.4
Encroach Node=42662
       1    4975    5022
Encroach Node=42413
       1    4973    5020
Encroach Node=42229
       1    4980    5014
Encroach Node=42010
       1    4980    5012
Encroach Node=41879
       1    4990    5021
Encroach Node=41613
       1    4965    5060
Encroach Node=41268
       1    4964    5135
Encroach Node=40897
       1    4984    5080
Encroach Node=40640
       1  4914.3 5025.39
Encroach Node=40238
       1    4910    5023
Encroach Node=39954
       1    4972    5028
Encroach Node=39866
       1  4977.5  5022.2
Encroach Node=39565
       1 4921.25    5012
Encroach Node=39351
       1    4900    5012
Encroach Node=38661
       1 4956.27    5012
Encroach Node=38006
       1    4958    5023
Encroach Node=37754
       1    4950    5064
Encroach Node=37517
       1 4859.23    5012
Encroach Node=36832
       1    4983    5070
Encroach Node=36293
       1    4988    5130
Encroach Node=35709
       1    4958    5021
Encroach Node=34887
       1  4987.6    5110
Encroach Node=34581
       1    4880    5060
Encroach Node=34308
       1    4962    5104
Encroach Node=34104
       1 4946.57 5020.05
Encroach Node=33521
       1 4933.63 5074.78
Encroach Node=33271
       1  4986.2 5146.64
Encroach Node=32934
       1    4986    5140
Encroach Node=32453
       1    4968    5045
Encroach Node=32023
       1 4967.31 5040.43
Encroach Node=31649
       1    4978    5043
Encroach Node=31235
       1    4955    5039
Encroach Node=30704
       1  4924.2    5026
Encroach Node=30233
       1    4942    5058
Encroach Node=30139
       1    4934    5066
Encroach Node=29515
       1    4950    5145
Encroach Node=29078
       1 4955.04 5119.73
Encroach Node=28630
       1 4845.27  5014.5
Encroach Node=28274
       1    4910    5040
Encroach Node=28129
       1  4985.5 5131.83
Encroach Node=27303
       1 4819.05 5093.19
Encroach Node=26719
       1    4950    5095
Encroach Node=26211
       1    4985    5180
Encroach Node=25558
       1    4963    5040
Encroach Node=25145
       1  4932.3  5015.3
Encroach Node=24811
       1    4984    5070
Encroach Node=24323
       1 4982.26    5120
Encroach Node=23362
       1 4899.79  5015.3
Encroach Node=22445
       1 4849.31  5017.7
Encroach Node=21796
       1    4927    5070
Encroach Node=21697
       1    4927    5070
Encroach Node=21452
       1    4860    5025
Encroach Node=20911
       1    4690    5017
Encroach Node=20390
       1 4718.63  5017.7
Encroach Node=19418
       1    4820    5075
Encroach Node=18589
       1    4915    5035
Encroach Node=18084
       1  4981.7 5102.26
Encroach Node=17479
       1  4981.7    5210
Encroach Node=17185
       1    4963    5094
Encroach Node=16647
       1 4945.02 5072.96
Encroach Node=16251
       1  4930.3 5047.22
Encroach Node=15861
       1 4938.29 5028.91
Encroach Node=15371
       1 4956.86  5109.5
Encroach Node=14881
       1    4950    5030
Encroach Node=14444
       1 4969.96 5020.85
Encroach Node=14118
       1  4981.3 5029.09
Encroach Node=13901
       1    4975    5025
Encroach Node=13821
       1    4975    5025
Encroach Node=13681
       1    4967    5053
Encroach Node=13381
       1    4920    5097
Encroach Node=12573
       1    4960    5058
Encroach Node=12098
       1 4967.56  5019.7
Encroach Node=11701
       1 4979.33  5019.4
Encroach Node=11206
       1    4960  5019.4
Encroach Node=10828
       1 4916.82  5019.4
Encroach Node=10355
       1 4913.33 5027.68
Encroach Node=9921
       1    4965    5030
Encroach Node=9667
       1  4980.1 5027.64
Encroach Node=9156
       1 4978.88 5035.28
Encroach Node=8887
       1    4957  5016.5
Encroach Node=8830
       1 4962.61  5016.5
Encroach Node=8433
       1    4950  5020.7
Encroach Node=7935
       1    4910  5020.7
Encroach Node=7518
       1 4878.58  5020.7
Encroach Node=7057
       1    4945  5020.7
Encroach Node=6791
       1 4978.55 5024.32
Encroach Node=6388
       1 4969.91  5020.7
Encroach Node=6059
       1    4979    5040
Encroach Node=5572
       1    4905 5025.82
Encroach Node=5017
       1    4960    5070
Encroach Node=4566
       1    4935    5090
Encroach Node=4081
       1    4970    5052
Encroach Node=3831
       1    4973    5027
Encroach Node=3555
       1  4978.9  5021.1
Encroach Node=3254
       1  4978.9  5021.1
Encroach Node=3005
       1  4978.9  5021.1
Encroach Node=2801
       1  4977.6  5022.4
Encroach Node=2593
       1  4964.7  5009.3
Encroach Node=2433
       1    4970    5035
Encroach Node=2223
       1    4935    5060
Encroach Node=2117
       1    4948    5048
Encroach Node=2052
       1  4969.5  5030.5
BEGIN DESCRIPTION:
Floodway Run
END DESCRIPTION:
Computation Interval=1HOUR
Output Interval=1HOUR
Run HTab= 0
Run UNet= 0
Run PostProcess= 0
UNET Theta= 1
UNET Theta Warmup= 1
UNET ZTol= 0.02
UNET ZSATol= 0.05
UNET MxIter= 20
UNET MaxInSteps= 0
UNET DtIC= 0
UNET DtMin= 0
UNET MaxCRTS= 20
UNET WFStab= 2
UNET SFStab= 1
UNET WFX= 1
UNET SFX= 1
UNET DSS MLevel= 4
UNET DZMax Abort= 100
UNET Convert EG Bridges=-1
UNET Use Existing IB Tables=-1
UNET Froude Reduction=False
UNET Froude Limit= 1
UNET Froude Power= 10
Instantaneous Interval=1HOUR
Write IC File= 0
Echo Input=False
Echo Output=False
Write Detailed= 0
Detailed Automatic Start=False, 10

--- Grassy Creek.f01 (steady flow) ---

Flow Title=Floodway
Number of Profiles=2
Profile Names=100-year,100-FW
River Rch & RM= Grassy Creek,Reach-1,49766
     677     677
River Rch & RM= Grassy Creek,Reach-1,48704
     836     836
River Rch & RM= Grassy Creek,Reach-1,46151
    1234    1234
River Rch & RM= Grassy Creek,Reach-1,42413
    1359    1359
River Rch & RM= Grassy Creek,Reach-1,40640
    1653    1653
River Rch & RM= Grassy Creek,Reach-1,36293
    1707    1707
River Rch & RM= Grassy Creek,Reach-1,34581
    2154    2154
River Rch & RM= Grassy Creek,Reach-1,30704
    2267    2267
River Rch & RM= Grassy Creek,Reach-1,29515
    2384    2384
River Rch & RM= Grassy Creek,Reach-1,27303
    2434    2434
River Rch & RM= Grassy Creek,Reach-1,25145
    2648    2648
River Rch & RM= Grassy Creek,Reach-1,22445
    3310    3310
River Rch & RM= Grassy Creek,Reach-1,19418
    3374    3374
River Rch & RM= Grassy Creek,Reach-1,18589
    3461    3461
River Rch & RM= Grassy Creek,Reach-1,17479
    3553    3553
River Rch & RM= Grassy Creek,Reach-1,13681
    3567    3567
River Rch & RM= Grassy Creek,Reach-1,12098
    3735    3735
River Rch & RM= Grassy Creek,Reach-1,10355
    3840    3840
River Rch & RM= Grassy Creek,Reach-1,9156
    4043    4043
River Rch & RM= Grassy Creek,Reach-1,4081
    4114    4114
Boundary for River Rch & Prof#=Grassy Creek,Reach-1,1
Up Type=0
Dn Type=3
Dn Slope=0.0031
Boundary for River Rch & Prof#=Grassy Creek,Reach-1,2
Up Type=0
Dn Type=3
Dn Slope=0.0031

--- Grassy Creek.g01 (geometry) ---

Geom Title=Existing Conditions

River Reach=Grassy Creek,Reach-1
Reach XY= 30
      1569419.12       951503.11      1569281.70       950798.15
      1570344.89       950412.82      1572201.73       946694.49
      1572405.95       945337.00      1571176.40       944333.96
      1571599.83       941641.56      1572245.84       940611.30
      1571508.64       938429.26      1571949.60       936390.09
      1570591.76       935033.73      1569551.88       935652.15
      1569359.63       934783.00      1567805.52       933179.42
      1566989.47       933123.62      1566381.14       932531.42
      1565179.92       932741.41      1564599.82       930505.83
      1565235.04       929294.94      1565356.04       927557.99
      1566766.98       926416.60      1566094.78       926235.78
      1565604.46       924046.13      1567619.44       922235.90
      1565831.66       921104.32      1566507.94       919558.35
      1565876.86       919484.65      1565772.45       918563.36
      1567818.65       916898.71      1568030.50       916225.19

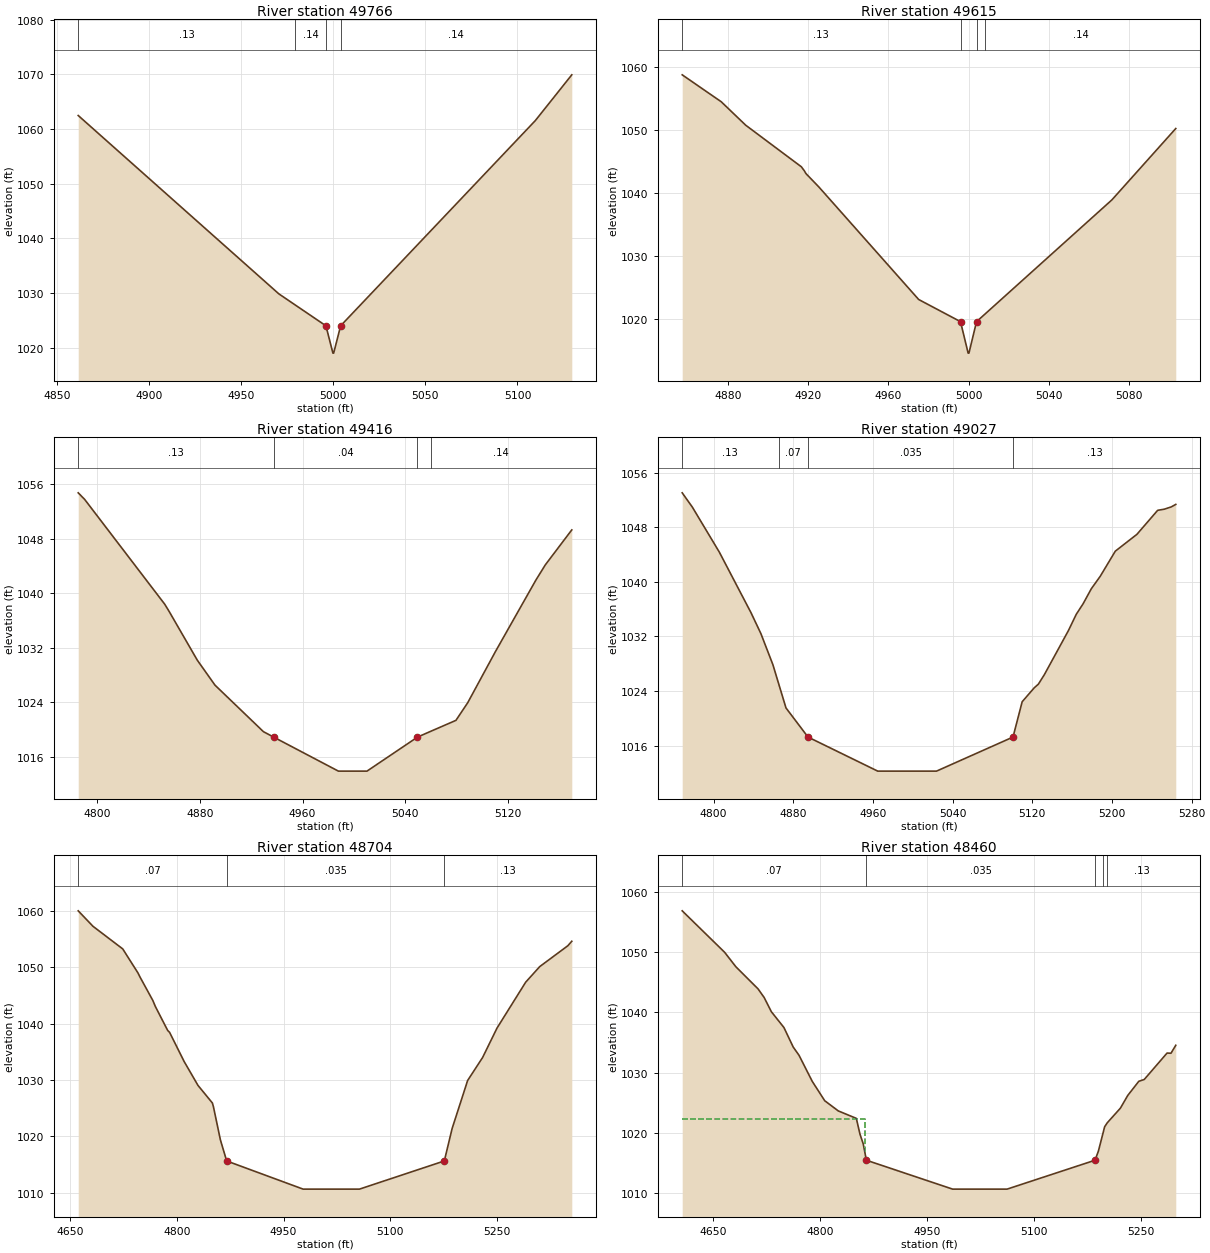
Type RM Length L Ch R = 1,49766,151,151,151
BEGIN DESCRIPTION:
Grassy Creek 100.0
END DESCRIPTION:
XS GIS Cut Line= 2
      1570741.93       949712.53      1570544.14       949531.69
#Sta/Elev= 9
  4861.5 1062.46  4970.4 1029.85  4979.4 1027.79  4996.0 1024.00  4999.8 1019.00
  5000.2 1019.00  5004.0 1024.00  5109.7 1061.53  5129.5 1069.90
#Mann=4,-1,0
  4861.5    0.13       0  4979.4    0.14       0  4996.0    0.05       0
  5004.0    0.14       0
Bank Sta=4996,5004
XS Rating Curve= 0
Exp/Cntr=0.3,0.1

Type RM Length L Ch R = 1,49615,199,199,199
BEGIN DESCRIPTION:
Grassy Creek 99.0
END DESCRIPTION:
XS GIS Cut Line= 3
      1570818.26       949658.81      1570775.88       949548.62
      1570693.94       949449.72
#Sta/Elev= 15
  4857.0 1058.83  4876.5 1054.55  4888.7 1050.83  4916.5 1044.22  4918.0 1043.58
  4918.8 1043.14  4925.2 1041.03  4975.1 1023.13  4996.0 1019.61  4999.8 1014.61
  5000.2 1014.61  5004.0 1019.61  5008.3 1020.84  5071.6 1038.96  5103.5 1050.30
#Mann=4,-1,0
  4857.0    0.13       0  4996.0    0.05       0  5004.0    0.13       0
  5008.3    0.14       0
Bank Sta=4996,5004
XS Rating Curve= 0
Exp/Cntr=0.3,0.1

Type RM Length L Ch R = 1,49416,389,389,389
BEGIN DESCRIPTION:
Grassy Creek 98.0
END DESCRIPTION:
XS GIS Cut Line= 3
      1571055.70       949630.59      1570982.22       949506.22
      1570826.77       949322.52
#Sta/Elev= 19
  4785.0 1054.76  4790.0 1053.80  4852.5 1038.39  4856.0 1037.31  4877.9 1030.17
  4891.7 1026.50  4929.5 1019.66  4937.5 1018.86  4988.0 1013.86  5010.3 1013.86
  5049.7 1018.86  5059.9 1019.70  5079.7 1021.32  5088.9 1023.91  5110.5 1031.42
  5142.1 1041.94  5149.4 1044.16  5169.6 1049.19  5170.1 1049.31
#Mann=4,-1,0
  4785.0    0.13       0  4937.5    0.04       0  5049.7    0.07       0
  5059.9    0.14       0
Bank Sta=4937.5,5049.7
XS Rating Curve= 0
Exp/Cntr=0.3,0.1

Type RM Length L Ch R = 1,49027,323,323,323
BEGIN DESCRIPTION:
Grassy Creek 97.0
END DESCRIPTION:
XS GIS Cut Line= 2
      1571394.84       949206.60      1570908.75       949110.52
#Sta/Elev= 27
  4768.5 1053.08  4778.7 1050.98  4805.8 1044.37  4837.5 1035.51  4847.5 1032.42
  4859.6 1027.84  4865.2 1025.13  4872.7 1021.51  4894.8 1017.24  4964.8 1012.24
  5023.8 1012.24  5100.6 1017.24  5109.8 1022.42  5121.8 1024.45  5126.1 1025.01
  5132.0 1026.38  5156.1 1032.83  5164.2 1035.28  5170.9 1036.78  5179.2 1039.00
  5188.2 1040.84  5203.3 1044.52  5225.0 1046.99  5245.8 1050.51  5252.5 1050.68
  5259.4 1051.01  5264.0 1051.38
#Mann=4,-1,0
  4768.5    0.13       0  4865.2    0.07       0  4894.8   0.035       0
  5100.6    0.13       0
Bank Sta=4894.8,5100.6
XS Rating Curve= 0
Exp/Cntr=0.3,0.1

Type RM Length L Ch R = 1,48704,244,244,244
BEGIN DESCRIPTION:
Grassy Creek 96.0
END DESCRIPTION:
XS GIS Cut Line= 3
      1571539.07       949051.18      1571092.45       948737.41
      1570993.55       948627.21
#Sta/Elev= 28
  4661.3 1060.04  4682.1 1057.29  4723.9 1053.28  4745.3 1049.02  4748.4 1048.24
  4766.1 1044.16  4769.9 1043.03  4787.1 1038.81  4789.7 1038.49  4808.7 1033.69
  4810.0 1033.35  4829.7 1029.06  4849.9 1025.95  4851.4 1025.28  4861.2 1019.40
  4870.0 1015.66  4977.5 1010.66  5056.7 1010.66  5176.0 1015.66  5187.0 1021.43
  5207.1 1029.28  5208.7 1029.92  5229.8 1034.01  5250.1 1039.24  5290.4 1047.38
  5310.2 1050.15  5349.6 1053.84  5355.2 1054.64
#Mann=3,-1,0
  4661.3    0.07       0  4870.0   0.035       0  5176.0    0.13       0
Bank Sta=4870,5176
XS Rating Curve= 0
Exp/Cntr=0.5,0.3

Type RM Length L Ch R = 1,48460,69,69,69
BEGIN DESCRIPTION:
Scenic Overlook Rd (GC) us
END DESCRIPTION:
XS GIS Cut Line= 5
      1571545.93       949019.56      1571526.92       948779.78
      1571477.46       948725.82      1571284.84       948543.70
      1571192.59       948478.28
#Sta/Elev= 30
  4606.9 1056.88  4666.4 1049.99  4682.2 1047.58  4713.2 1043.92  4721.8 1042.48
  4731.9 1040.12  4749.5 1037.50  4762.5 1034.26  4770.7 1032.88  4789.2 1028.56
  4806.7 1025.34  4825.7 1023.65  4851.0 1022.41  4856.1 1019.79  4860.6 1018.20
  4865.1 1015.46  4986.0 1010.66  5062.3 1010.66  5185.6 1015.46  5190.3 1016.96
  5196.5 1019.82  5199.1 1021.02  5202.8 1021.68  5221.2 1024.11  5231.5 1026.22
  5247.0 1028.57  5254.6 1028.87  5286.6 1033.26  5292.1 1033.23  5298.8 1034.55
#Mann=5,-1,0
  4606.9    0.07       0  4865.1   0.035       0  5185.6    0.07       0
  5196.5    0.07       0  5202.8    0.13       0
#XS Ineff=2,0
    0.00 4863.30 1022.32 5198.50    0.00 1019.25
Permanent Ineff=
       F       F
Bank Sta=4865.1,5185.6
XS Rating Curve= 0
Exp/Cntr=0.5,0.3

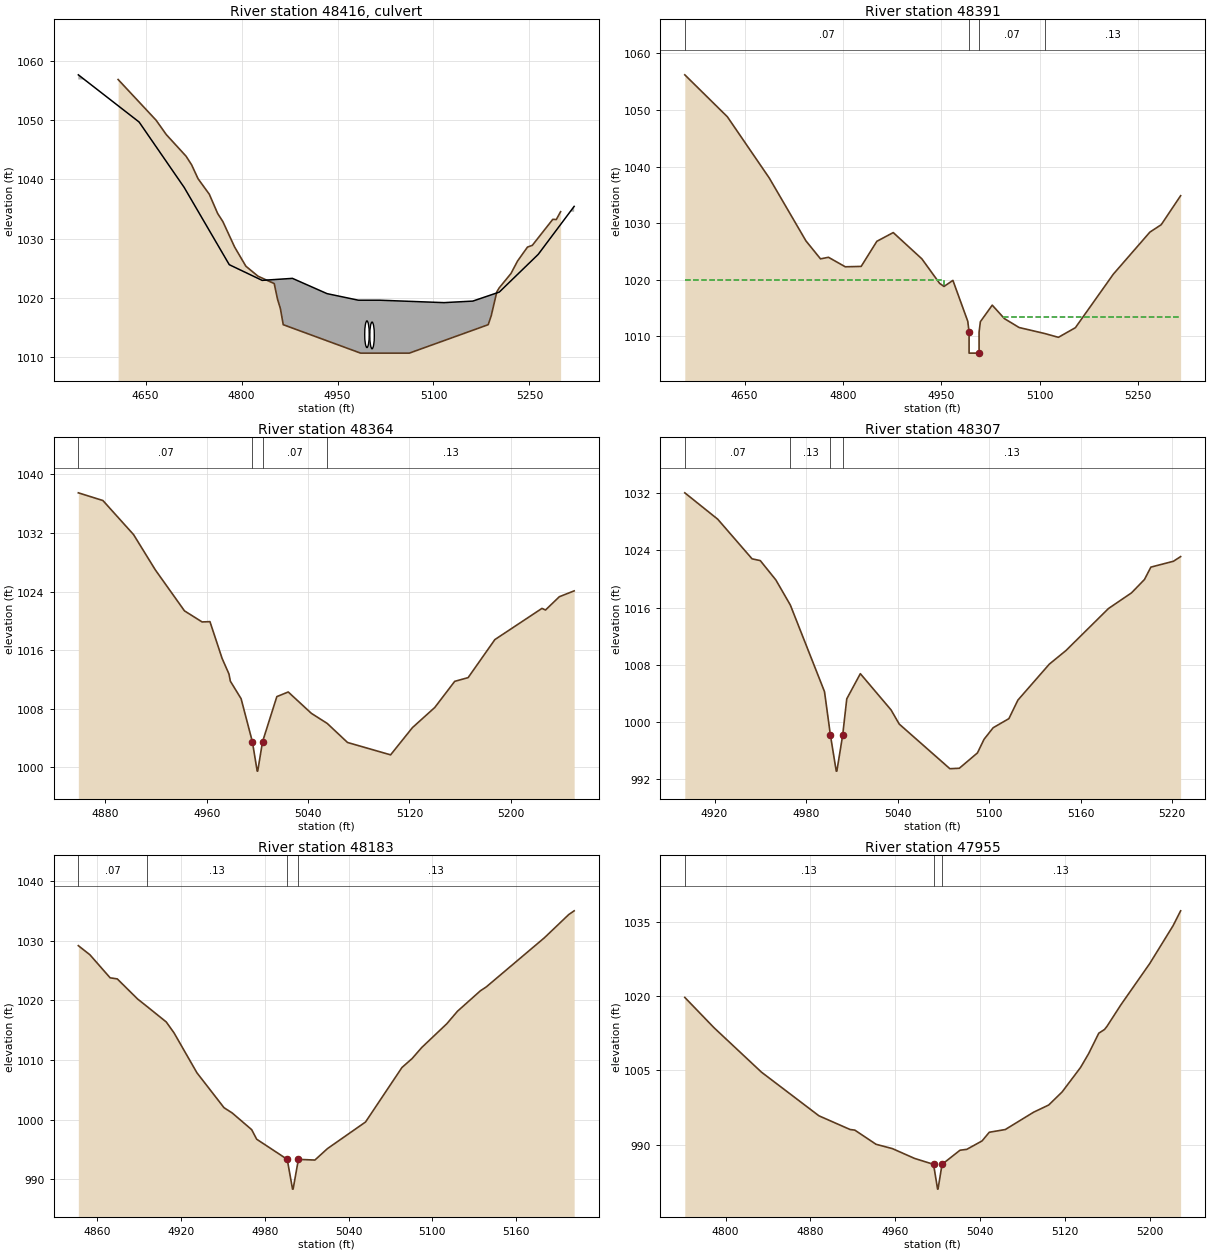
Type RM Length L Ch R =2,48416,,,
BEGIN DESCRIPTION:
Scenic Overlook Rd (GC) TOR
Structure ID: LDS_GC_09
Approximate Survey Structure
END DESCRIPTION:
Bridge Culvert--1,0,-1,-1,0
Deck Dist Width WeirC Skew NumUp NumDn MinLoCord MaxHiCord MaxSubmerge Is_Ogee
42,20,3,,14,14,,,0.95,0,1,1,,,
  4544.7  4639.7  4710.2  4780.7  4832.1  4879.5  4933.6  4982.6  5015.8  5116.4
  5161.5  5202.9  5263.8  5320.0
 1057.67 1049.70 1038.65 1025.60 1022.95 1023.29 1020.71 1019.60 1019.60 1019.19
 1019.45 1020.97 1027.34 1035.45
  990.66  990.66  990.66  990.66  990.66  990.66  990.66  990.66  990.66  990.66
  990.66  990.66  990.66  990.66
  4544.7  4639.7  4710.2  4780.7  4832.1  4879.5  4933.6  4982.6  5015.8  5116.4
  5161.5  5202.9  5263.8  5320.0
 1057.67 1049.70 1038.65 1025.60 1022.95 1023.29 1020.71 1019.60 1019.60 1019.19
 1019.45 1020.97 1027.34 1035.45
  987.06  987.06  987.06  987.06  987.06  987.06  987.06  987.06  987.06  987.06
  987.06  987.06  987.06  987.06
Culvert=3,4.5,7,20,0.024,0.5,1,34,1,1011.6,4996,1010.3,4996,Culvert #1,0,42
Culvert Bottom n=0.024
Culvert Bottom Depth=0
Culvert Depth Blocked=0
Culvert=3,4.5,7,20,0.024,0.5,1,34,1,1011.4,5004,1010.3,5004,Culvert #2,0,42
Culvert Bottom n=0.024
Culvert Bottom Depth=0
Culvert Depth Blocked=0
BC Design=,,0,,0,,,,,,

Type RM Length L Ch R = 1,48391,27,27,27
BEGIN DESCRIPTION:
Scenic Overlook Rd (GC) ds
END DESCRIPTION:
XS GIS Cut Line= 6
      1571569.72       949014.80      1571551.65       948719.08
      1571502.94       948650.87      1571438.48       948598.41
      1571326.81       948507.73      1571193.81       948440.23
#Sta/Elev= 30
  4558.8 1056.19  4623.7 1048.79  4687.6 1037.98  4743.6 1026.87  4765.8 1023.70
  4777.9 1023.98  4803.6 1022.30  4827.8 1022.37  4851.7 1026.80  4876.7 1028.34
  4920.4 1023.70  4947.4 1019.38  4954.1 1018.83  4967.7 1019.90  4990.4 1012.67
  4992.4 1010.75  4992.4 1007.06  5007.6 1007.06  5007.6 1010.75  5009.6 1012.61
  5027.7 1015.53  5046.3 1013.15  5068.7 1011.58  5107.4 1010.53  5128.6 1009.85
  5154.5 1011.55  5212.3 1020.99  5268.1 1028.42  5285.4 1029.73  5315.0 1034.85
#Mann=4,-1,0
  4558.8    0.07       0  4992.4    0.05       0  5007.6    0.07       0
  5107.4    0.13       0
#XS Ineff=2,0
    0.00 4954.50 1019.91 5045.50    0.00 1013.40
Permanent Ineff=
       F       F
Bank Sta=4992.4,5007.6
XS Rating Curve= 0
Exp/Cntr=0.5,0.3

Type RM Length L Ch R = 1,48364,57,57,57
BEGIN DESCRIPTION:
Grassy Creek 95.8
END DESCRIPTION:
XS GIS Cut Line= 3
      1571589.42       948656.16      1571442.73       948574.43
      1571264.08       948440.17
#Sta/Elev= 30
  4858.6 1037.48  4878.0 1036.43  4902.2 1031.78  4919.4 1026.96  4942.4 1021.37
  4956.3 1019.86  4962.5 1019.90  4972.1 1014.88  4977.5 1012.76  4978.6 1011.78
  4987.1 1009.38  4996.0 1003.50  4999.8  999.50  5000.2  999.50  5004.0 1003.50
  5015.3 1009.67  5024.3 1010.30  5042.6 1007.38  5055.0 1006.02  5071.1 1003.41
  5105.1 1001.72  5122.3 1005.43  5140.0 1008.19  5155.7 1011.75  5166.3 1012.26
  5187.4 1017.45  5224.6 1021.71  5227.4 1021.49  5238.3 1023.30  5250.0 1024.10
#Mann=4,-1,0
  4858.6    0.07       0  4996.0    0.05       0  5004.0    0.07       0
  5055.0    0.13       0
Bank Sta=4996,5004
XS Rating Curve= 0
Exp/Cntr=0.3,0.1

Type RM Length L Ch R = 1,48307,124,124,124
BEGIN DESCRIPTION:
Grassy Creek 95.5
END DESCRIPTION:
XS GIS Cut Line= 4
      1571572.64       948566.29      1571455.72       948523.53
      1571350.15       948455.85      1571278.13       948434.20
#Sta/Elev= 30
  4900.5 1032.06  4922.1 1028.37  4944.6 1022.83  4950.0 1022.58  4960.2 1019.88
  4969.7 1016.37  4992.1 1004.26  4996.0  998.14  4999.8  993.14  5000.2  993.14
  5004.0  998.14  5006.7 1003.25  5015.6 1006.77  5035.7 1001.71  5041.1  999.72
  5074.3  993.48  5080.5  993.54  5092.4  995.69  5096.7  997.59  5102.7  999.21
  5113.0 1000.48  5118.9 1003.07  5139.5 1008.10  5150.4 1010.00  5178.3 1015.88
  5193.4 1018.07  5201.9 1019.94  5206.1 1021.67  5220.9 1022.49  5225.6 1023.14
#Mann=4,-1,0
  4900.5    0.07       0  4969.7    0.13       0  4996.0    0.05       0
  5004.0    0.13       0
Bank Sta=4996,5004
XS Rating Curve= 0
Exp/Cntr=0.3,0.1

Type RM Length L Ch R = 1,48183,228,228,228
BEGIN DESCRIPTION:
Grassy Creek 95.0
END DESCRIPTION:
XS GIS Cut Line= 3
      1571606.91       948505.67      1571428.81       948381.27
      1571335.52       948279.51
#Sta/Elev= 30
  4846.3 1029.19  4854.6 1027.66  4869.1 1023.79  4874.2 1023.61  4888.8 1020.23
  4895.3 1019.02  4909.3 1016.38  4914.9 1014.54  4931.3 1007.84  4950.7 1001.98
  4956.5 1001.11  4970.5  998.30  4974.1  996.69  4996.0  993.31  4999.8  988.31
  5000.2  988.31  5004.0  993.31  5015.8  993.19  5024.8  995.11  5052.1  999.58
  5078.2 1008.73  5085.5 1010.24  5092.3 1012.07  5110.3 1016.07  5118.0 1018.18
  5134.4 1021.61  5138.6 1022.26  5180.3 1030.52  5197.7 1034.41  5201.6 1035.04
#Mann=4,-1,0
  4846.3    0.07       0  4895.3    0.13       0  4996.0    0.05       0
  5004.0    0.13       0
Bank Sta=4996,5004
XS Rating Curve= 0
Exp/Cntr=0.3,0.1

Type RM Length L Ch R = 1,47955,293,293,293
BEGIN DESCRIPTION:
Grassy Creek 94.0
END DESCRIPTION:
XS GIS Cut Line= 4
      1571748.19       948395.39      1571686.02       948273.87
      1571499.47       948177.77      1571380.76       948155.15
#Sta/Elev= 30
  4761.6 1019.72  4789.1 1013.61  4833.8 1004.64  4888.0  995.82  4917.3  993.06
  4921.8  992.93  4941.8  990.07  4957.2  989.20  4978.1  987.22  4996.0  986.02
  4999.8  981.02  5000.2  981.02  5004.0  986.02  5020.9  988.87  5027.3  989.05
  5041.7  990.75  5048.5  992.50  5063.6  993.05  5090.2  996.54  5104.5  998.00
  5117.1 1000.63  5134.5 1005.58  5142.1 1008.36  5151.7 1012.50  5157.1 1013.25
  5159.6 1013.94  5172.3 1018.16  5199.7 1026.56  5221.7 1034.20  5228.8 1037.20
#Mann=3,-1,0
  4761.6    0.13       0  4996.0    0.05       0  5004.0    0.13       0
Bank Sta=4996,5004
XS Rating Curve= 0
Exp/Cntr=0.3,0.1

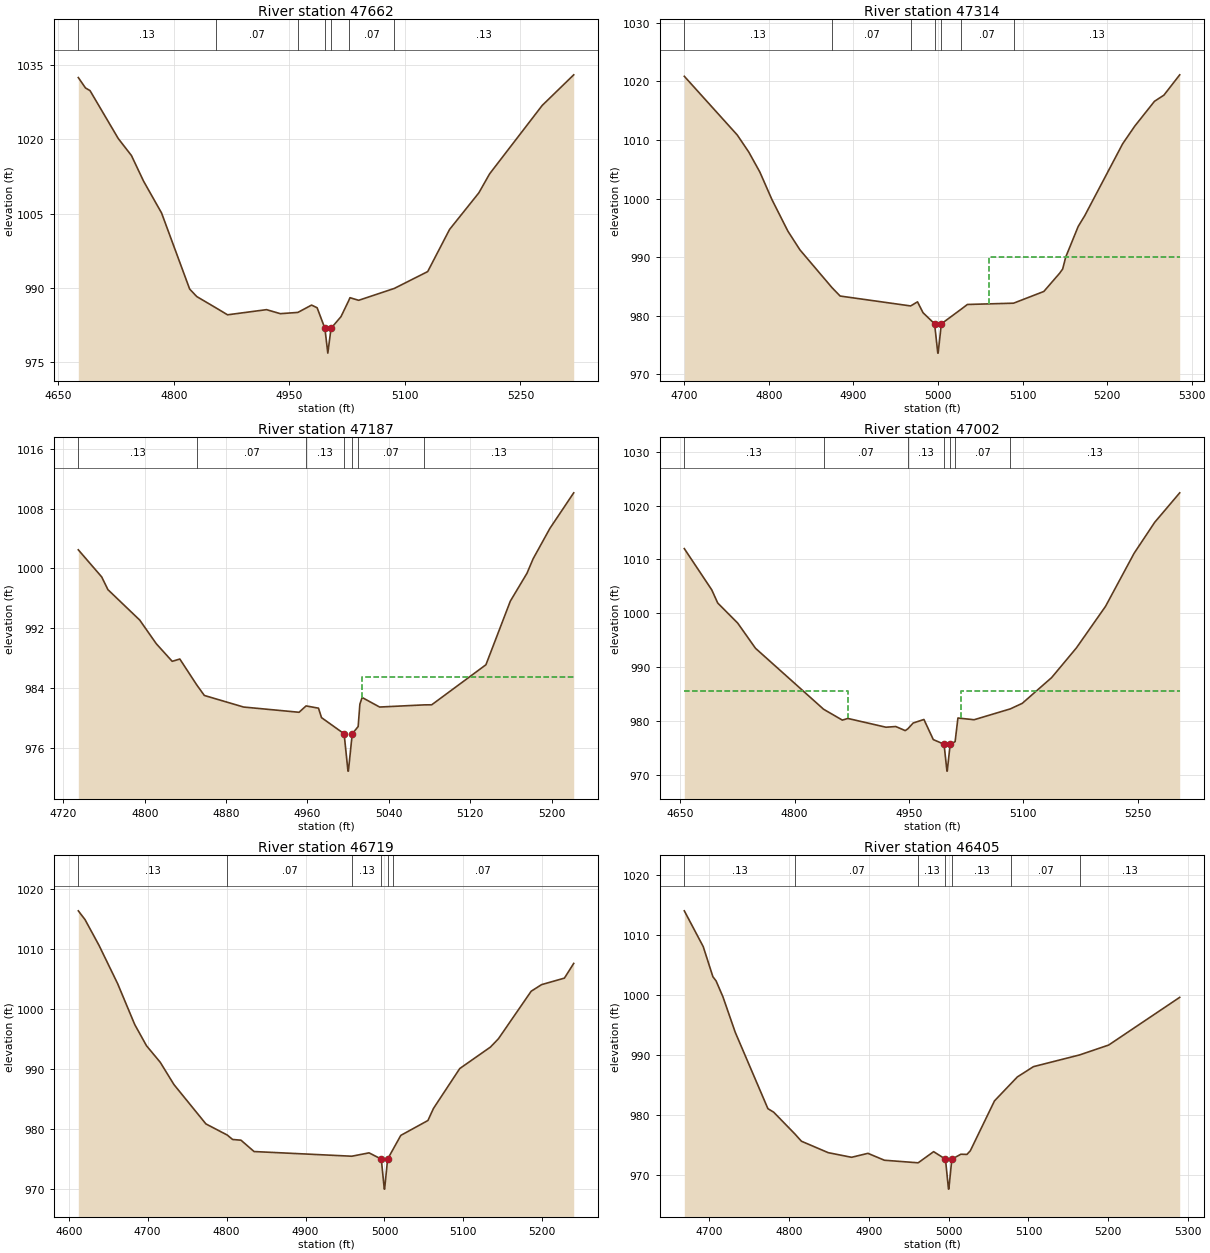
Type RM Length L Ch R = 1,47662,348,348,348
BEGIN DESCRIPTION:
Grassy Creek 93.0
END DESCRIPTION:
XS GIS Cut Line= 4
      1571960.18       948124.05      1571864.09       948025.13
      1571524.91       947900.77      1571397.73       947832.94
#Sta/Elev= 30
  4675.8 1032.40  4685.1 1030.31  4691.0 1029.77  4727.7 1020.11  4744.8 1016.69
  4760.5 1011.54  4783.9 1005.12  4820.4  989.79  4829.6  988.28  4854.1  986.04
  4869.6  984.60  4920.2  985.64  4938.1  984.83  4960.9  985.08  4978.7  986.56
  4985.9  986.02  4996.0  981.88  4999.8  976.88  5004.0  981.88  5016.9  984.23
  5026.7  987.38  5028.6  988.05  5039.8  987.52  5086.2  989.92  5129.5  993.31
  5157.9 1001.80  5195.9 1009.17  5209.9 1013.00  5278.1 1026.77  5319.1 1032.95
#Mann=7,-1,0
  4675.8    0.13       0  4854.1    0.07       0  4960.9    0.13       0
  4996.0    0.05       0  5004.0    0.13       0  5026.7    0.07       0
  5086.2    0.13       0
Bank Sta=4996,5004
XS Rating Curve= 0
Exp/Cntr=0.3,0.1

Type RM Length L Ch R = 1,47314,127,127,127
BEGIN DESCRIPTION:
Grassy Creek 92.0
END DESCRIPTION:
XS GIS Cut Line= 3
      1572030.89       947742.51      1571960.19       947688.78
      1571485.32       947541.80
#Sta/Elev= 30
  4700.0 1020.87  4762.6 1010.86  4776.1 1007.98  4789.3 1004.55  4803.6  999.85
  4822.5  994.45  4836.8  991.25  4874.7  984.81  4884.3  983.38  4967.7  981.69
  4975.8  982.39  4982.3  980.54  4996.0  978.64  4999.8  973.64  5000.2  973.64
  5004.0  978.64  5027.0  981.09  5034.8  981.94  5089.4  982.16  5125.2  984.16
  5144.0  987.29  5147.5  988.00  5151.1  990.03  5165.9  995.27  5173.4  997.04
  5218.4 1009.35  5232.7 1012.36  5256.1 1016.61  5267.2 1017.65  5285.9 1021.12
#Mann=7,-1,0
  4700.0    0.13       0  4874.7    0.07       0  4967.7    0.13       0
  4996.0    0.05       0  5004.0    0.13       0  5027.0    0.07       0
  5089.4    0.13       0
#XS Ineff=2,0
       0                 5059.80    0.00  990.12
Permanent Ineff=
       F       F
Bank Sta=4996,5004
XS Rating Curve= 0
Exp/Cntr=0.3,0.1

Type RM Length L Ch R = 1,47187,185,185,185
BEGIN DESCRIPTION:
Grassy Creek 91.5
END DESCRIPTION:
XS GIS Cut Line= 2
      1572027.66       947557.42      1571551.19       947456.71
#Sta/Elev= 30
  4734.7 1002.48  4757.7  998.85  4763.8  997.15  4795.1  993.07  4811.4  989.90
  4827.0  987.55  4834.5  987.86  4851.0  984.42  4858.6  982.98  4897.2  981.43
  4951.7  980.73  4958.6  981.58  4970.8  981.28  4973.8  980.01  4996.0  977.85
  4999.8  972.85  5000.2  972.85  5004.0  977.85  5009.8  978.82  5011.5  981.82
  5013.7  982.71  5030.9  981.43  5074.8  981.72  5082.1  981.73  5135.4  987.09
  5159.4  995.61  5175.8  999.35  5181.8 1001.28  5198.3 1005.35  5221.7 1010.11
#Mann=7,-1,0
  4734.7    0.13       0  4851.0    0.07       0  4958.6    0.13       0
  4996.0    0.05       0  5004.0    0.13       0  5009.8    0.07       0
  5074.8    0.13       0
#XS Ineff=2,0
       0                 5013.90    0.00  985.49
Permanent Ineff=
       F       F
Bank Sta=4996,5004
XS Rating Curve= 0
Exp/Cntr=0.3,0.1

Type RM Length L Ch R = 1,47002,283,283,283
BEGIN DESCRIPTION:
Grassy Creek 91.0
END DESCRIPTION:
XS GIS Cut Line= 4
      1572129.80       947445.71      1571968.67       947380.69
      1571660.58       947276.11      1571522.08       947216.75
#Sta/Elev= 30
  4655.3 1011.99  4691.3 1004.33  4699.1 1001.89  4725.4  998.14  4748.6  993.48
  4838.0  982.14  4862.6  980.12  4869.8  980.43  4919.8  978.80  4932.6  978.93
  4945.1  978.17  4948.6  978.52  4955.5  979.58  4969.6  980.24  4981.9  976.50
  4996.0  975.64  4999.8  970.64  5000.2  970.64  5004.0  975.64  5010.5  976.11
  5014.2  980.51  5035.4  980.19  5083.0  982.21  5098.6  983.24  5137.1  988.02
  5169.6  993.54  5207.8 1001.26  5245.4 1011.15  5272.3 1016.88  5305.1 1022.36
#Mann=7,-1,0
  4655.3    0.13       0  4838.0    0.07       0  4948.6    0.13       0
  4996.0    0.05       0  5004.0    0.13       0  5010.5    0.07       0
  5083.0    0.13       0
#XS Ineff=2,0
    0.00 4869.60  985.57 5017.80    0.00  985.57
Permanent Ineff=
       F       F
Bank Sta=4996,5004
XS Rating Curve= 0
Exp/Cntr=0.3,0.1

Type RM Length L Ch R = 1,46719,314,314,314
BEGIN DESCRIPTION:
Grassy Creek 90.0
END DESCRIPTION:
XS GIS Cut Line= 4
      1572237.19       947242.20      1572081.73       947171.53
      1571830.17       947044.34      1571680.32       946953.86
#Sta/Elev= 30
  4612.1 1016.37  4620.6 1014.91  4638.3 1010.63  4661.9 1004.25  4683.6  997.43
  4698.5  993.90  4715.9  991.15  4733.3  987.43  4773.8  980.88  4800.9  979.02
  4807.6  978.29  4818.2  978.17  4834.8  976.28  4958.6  975.50  4980.5  976.06
  4996.0  975.02  4999.8  970.02  5000.2  970.02  5004.0  975.02  5010.6  976.58
  5020.7  978.97  5055.1  981.45  5062.1  983.46  5095.4  990.10  5134.3  993.68
  5144.4  995.06  5185.9 1002.98  5199.1 1004.08  5228.0 1005.16  5239.8 1007.61
#Mann=6,-1,0
  4612.1    0.13       0  4800.9    0.07       0  4958.6    0.13       0
  4996.0    0.05       0  5004.0    0.13       0  5010.6    0.07       0
Bank Sta=4996,5004
XS Rating Curve= 0
Exp/Cntr=0.3,0.1

Type RM Length L Ch R = 1,46405,254,254,254
BEGIN DESCRIPTION:
Grassy Creek 89.0
END DESCRIPTION:
XS GIS Cut Line= 3
      1572372.89       946970.86      1572028.02       946804.08
      1571793.46       946767.35
#Sta/Elev= 30
  4668.9 1013.99  4692.6 1008.02  4704.7 1003.00  4708.7 1002.30  4717.3  999.64
  4732.7  993.73  4773.6  980.99  4780.8  980.41  4807.2  976.80  4815.6  975.56
  4849.2  973.65  4878.4  972.88  4898.9  973.54  4919.5  972.39  4961.8  971.96
  4981.2  973.82  4996.0  972.57  4999.8  967.57  5000.2  967.57  5004.0  972.57
  5015.3  973.39  5022.9  973.36  5027.1  973.96  5057.4  982.29  5078.4  985.22
  5086.0  986.28  5106.2  988.00  5163.9  989.95  5200.4  991.60  5289.4  999.56
#Mann=7,-1,0
  4668.9    0.13       0  4807.2    0.07       0  4961.8    0.13       0
  4996.0    0.05       0  5004.0    0.13       0  5078.4    0.07       0
  5163.9    0.13       0
Bank Sta=4996,5004
XS Rating Curve= 0
Exp/Cntr=0.5,0.3

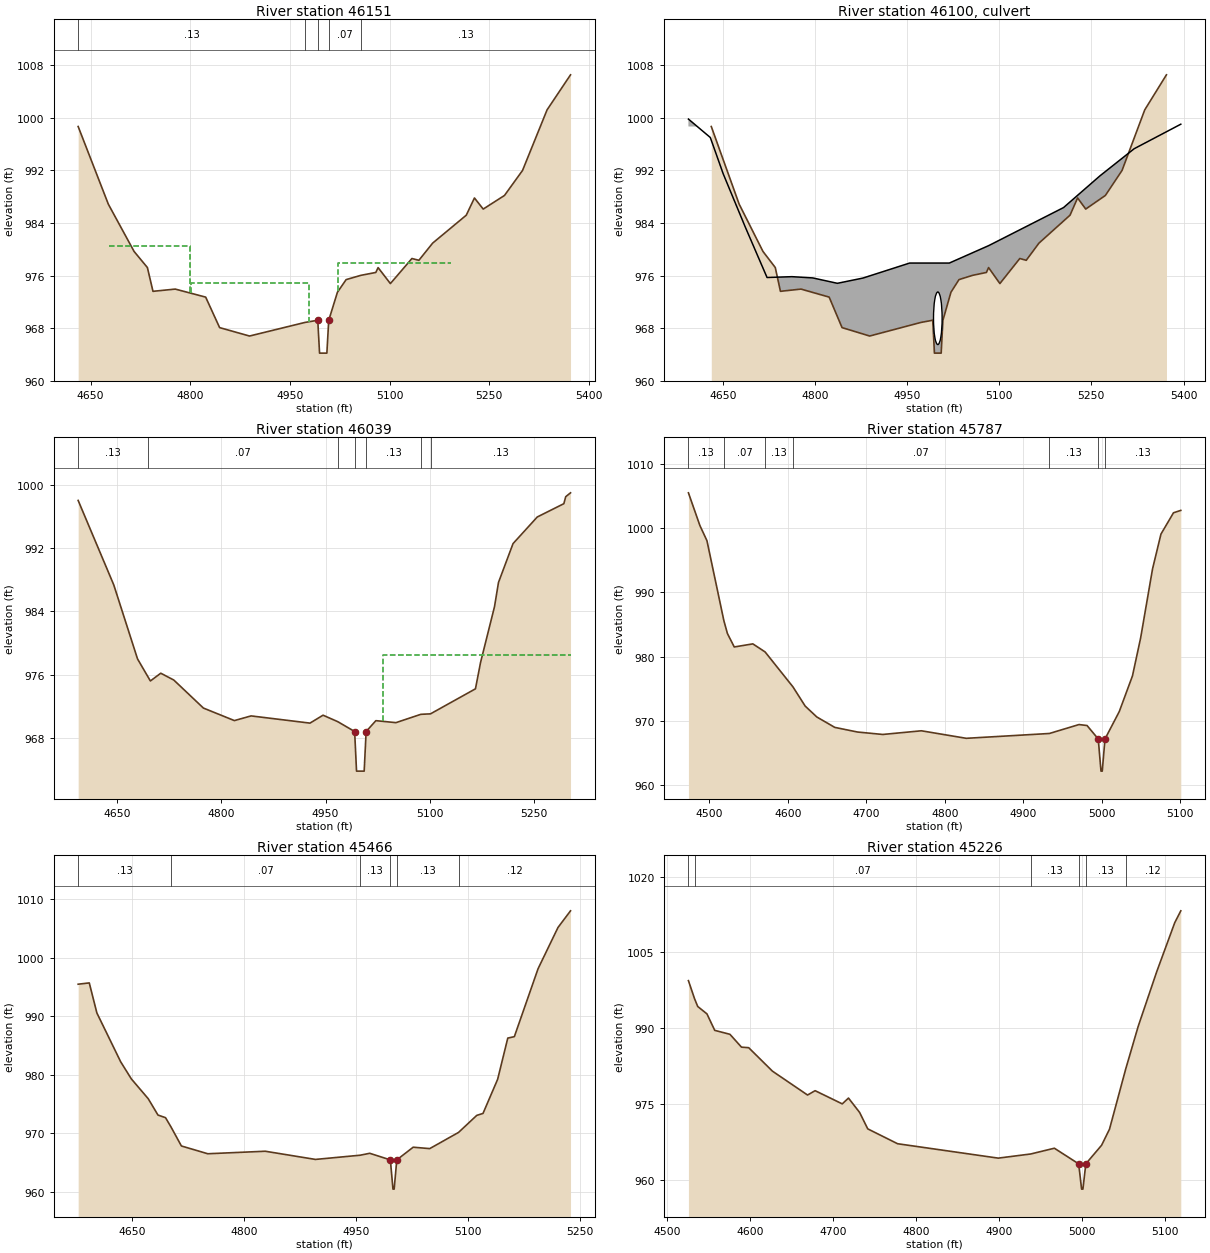
Type RM Length L Ch R = 1,46151,112,112,112
BEGIN DESCRIPTION:
Pilot Mountain Pkwy (GC) us
END DESCRIPTION:
XS GIS Cut Line= 6
      1572521.52       946580.84      1572326.77       946651.32
      1572234.03       946655.03      1572083.79       946621.64
      1571957.67       946554.87      1571861.23       946447.31
#Sta/Elev= 30
  4631.2  998.67  4676.6  986.86  4715.4  979.66  4735.4  977.22  4743.8  973.60
  4777.3  973.94  4823.1  972.72  4844.1  968.08  4889.1  966.80  4972.6  968.87
  4991.8  969.20  4994.5  964.20  5005.5  964.20  5008.3  969.18  5021.4  973.46
  5034.5  975.38  5056.6  976.03  5079.2  976.47  5082.6  977.21  5101.1  974.78
  5133.5  978.59  5144.0  978.32  5164.7  980.93  5215.3  985.18  5227.6  987.80
  5240.8  986.11  5272.8  988.18  5300.0  991.99  5336.9 1001.20  5372.2 1006.53
#Mann=5,-1,0
  4631.2    0.13       0  4972.6    0.07       0  4991.8    0.05       0
  5008.3    0.07       0  5056.6    0.13       0
#XS Ineff=3,-1
 4800.30 4978.00  974.80 4678.10 4800.20  980.43 5022.70 5191.80  977.90
Permanent Ineff=
       F       F       F
Bank Sta=4991.8,5008.3
XS Rating Curve= 0
Exp/Cntr=0.5,0.3

Type RM Length L Ch R =2,46100,,,
BEGIN DESCRIPTION:
Pilot Mountain Pkwy (GC) TOR
Structure ID: LDS_GC_08
Approximate Survey Structure
END DESCRIPTION:
Bridge Culvert--1,0,-1,-1,0
Deck Dist Width WeirC Skew NumUp NumDn MinLoCord MaxHiCord MaxSubmerge Is_Ogee
15,72,3,,16,16,,,0.95,0,1,1,,,
  4594.0  4629.6  4650.7  4686.5  4722.0  4762.6  4796.4  4836.5  4878.2  4954.1
  5018.7  5083.0  5204.7  5263.9  5319.7  5395.6
  999.80  997.00  991.45  983.39  975.70  975.83  975.64  974.82  975.62  977.90
  977.90  980.56  986.34  991.16  995.29  999.02
  944.20  944.20  944.20  944.20  944.20  944.20  944.20  944.20  944.20  944.20
  944.20  944.20  944.20  944.20  944.20  944.20
  4594.0  4629.6  4650.7  4686.5  4722.0  4762.6  4796.4  4836.5  4878.2  4954.1
  5018.7  5083.0  5204.7  5263.9  5319.7  5395.6
  999.80  997.00  991.45  983.39  975.70  975.83  975.64  974.82  975.62  977.90
  977.90  980.56  986.34  991.16  995.29  999.02
  943.84  943.84  943.84  943.84  943.84  943.84  943.84  943.84  943.84  943.84
  943.84  943.84  943.84  943.84  943.84  943.84
Culvert=3,8,14,72,0.024,0.9,1,34,3,965.5,5000,965.14,5000,Culvert #1,0,15
Culvert Bottom n=0.024
Culvert Bottom Depth=0
Culvert Depth Blocked=0
BC Design=,,0,,0,,,,,,

Type RM Length L Ch R = 1,46039,252,252,252
BEGIN DESCRIPTION:
Pilot Mountain Pkwy (GC) ds
END DESCRIPTION:
XS GIS Cut Line= 6
      1572517.81       946553.02      1572349.02       946578.98
      1572254.43       946578.98      1572031.86       946510.36
      1571937.27       946439.88      1571881.63       946367.54
#Sta/Elev= 30
  4594.5  998.01  4645.7  987.34  4679.8  978.01  4694.3  975.82  4698.3  975.22
  4713.2  976.20  4731.9  975.34  4774.5  971.80  4819.0  970.22  4843.0  970.81
  4927.6  969.90  4946.4  970.90  4967.6  970.08  4991.8  968.84  4994.5  963.84
  5005.5  963.84  5008.3  968.84  5022.3  970.21  5051.1  969.96  5086.9  971.01
  5100.8  971.07  5165.4  974.23  5172.7  977.55  5192.8  984.61  5198.5  987.66
  5219.4  992.56  5254.2  995.92  5292.4  997.60  5295.1  998.48  5302.0  998.97
#Mann=7,-1,0
  4594.5    0.13       0  4694.3    0.07       0  4967.6    0.13       0
  4991.8    0.05       0  5008.3    0.13       0  5086.9    0.13       0
  5100.8    0.13       0
#XS Ineff=2,0
    0.00 4968.00  970.00 5032.00    0.00  978.50
Permanent Ineff=
       F       F
Bank Sta=4991.8,5008.3
XS Rating Curve= 0
Exp/Cntr=0.5,0.3

Type RM Length L Ch R = 1,45787,321,321,321
BEGIN DESCRIPTION:
Grassy Creek 88.0
END DESCRIPTION:
XS GIS Cut Line= 2
      1572519.87       946382.94      1571895.18       946323.58
#Sta/Elev= 30
  4473.4 1005.47  4488.0 1000.39  4497.0  998.03  4518.6  985.58  4523.1  983.60
  4531.8  981.51  4555.5  981.99  4571.1  980.74  4606.6  975.31  4622.2  972.32
  4637.0  970.63  4659.9  969.01  4688.8  968.29  4721.1  967.91  4770.3  968.48
  4827.5  967.31  4933.4  968.06  4971.2  969.45  4981.4  969.30  4995.7  967.21
  4999.2  962.21  5000.8  962.21  5004.3  967.21  5022.5  971.47  5039.3  977.01
  5049.7  982.90  5064.9  993.65  5075.6  999.05  5091.6 1002.37  5100.9 1002.74
#Mann=7,-1,0
  4473.4    0.13       0  4518.6    0.07       0  4571.1    0.13       0
  4606.6    0.07       0  4933.4    0.13       0  4995.7    0.05       0
  5004.3    0.13       0
Bank Sta=4995.7,5004.3
XS Rating Curve= 0
Exp/Cntr=0.3,0.1

Type RM Length L Ch R = 1,45466,240,240,240
BEGIN DESCRIPTION:
Grassy Creek 87.0
END DESCRIPTION:
XS GIS Cut Line= 3
      1572536.75       946148.32      1572070.42       946032.45
      1571909.32       945953.31
#Sta/Elev= 30
  4577.2  995.50  4592.1  995.72  4602.3  990.58  4634.2  982.23  4648.5  979.30
  4671.1  975.92  4684.2  973.12  4694.3  972.67  4701.6  971.10  4715.6  967.83
  4751.0  966.50  4828.0  966.93  4895.3  965.53  4955.3  966.25  4968.0  966.58
  4995.7  965.45  4999.2  960.45  5000.8  960.45  5004.3  965.45  5026.3  967.62
  5048.5  967.38  5087.1  970.15  5111.5  973.06  5119.9  973.40  5139.5  979.23
  5153.1  986.28  5161.9  986.53  5193.7  998.15  5220.4 1005.20  5237.2 1008.05
#Mann=6,-1,0
  4577.2    0.13       0  4701.6    0.07       0  4955.3    0.13       0
  4995.7    0.05       0  5004.3    0.13       0  5087.1    0.12       0
Bank Sta=4995.7,5004.3
XS Rating Curve= 0
Exp/Cntr=0.3,0.1

Type RM Length L Ch R = 1,45226,237,237,237
BEGIN DESCRIPTION:
Grassy Creek 86.0
END DESCRIPTION:
XS GIS Cut Line= 3
      1572621.57       945987.21      1572432.22       945893.95
      1572064.79       945789.37
#Sta/Elev= 30
  4525.6  999.43  4533.0  995.85  4536.8  994.32  4547.9  992.86  4557.3  989.60
  4575.6  988.82  4589.5  986.28  4598.2  986.17  4626.8  981.53  4669.1  976.81
  4678.2  977.67  4710.9  975.06  4718.4  976.21  4731.8  973.37  4741.6  970.12
  4777.5  967.18  4898.8  964.33  4937.9  965.15  4966.4  966.29  4995.7  963.20
  4999.2  958.20  5000.8  958.20  5004.3  963.20  5023.3  966.88  5032.8  970.05
  5052.4  981.99  5067.4  990.40  5089.7 1001.20  5111.4 1010.89  5118.7 1013.24
#Mann=6,-1,0
  4525.6    0.13       0  4533.0    0.07       0  4937.9    0.13       0
  4995.7    0.05       0  5004.3    0.13       0  5052.4    0.12       0
Bank Sta=4995.7,5004.3
XS Rating Curve= 0
Exp/Cntr=0.3,0.1