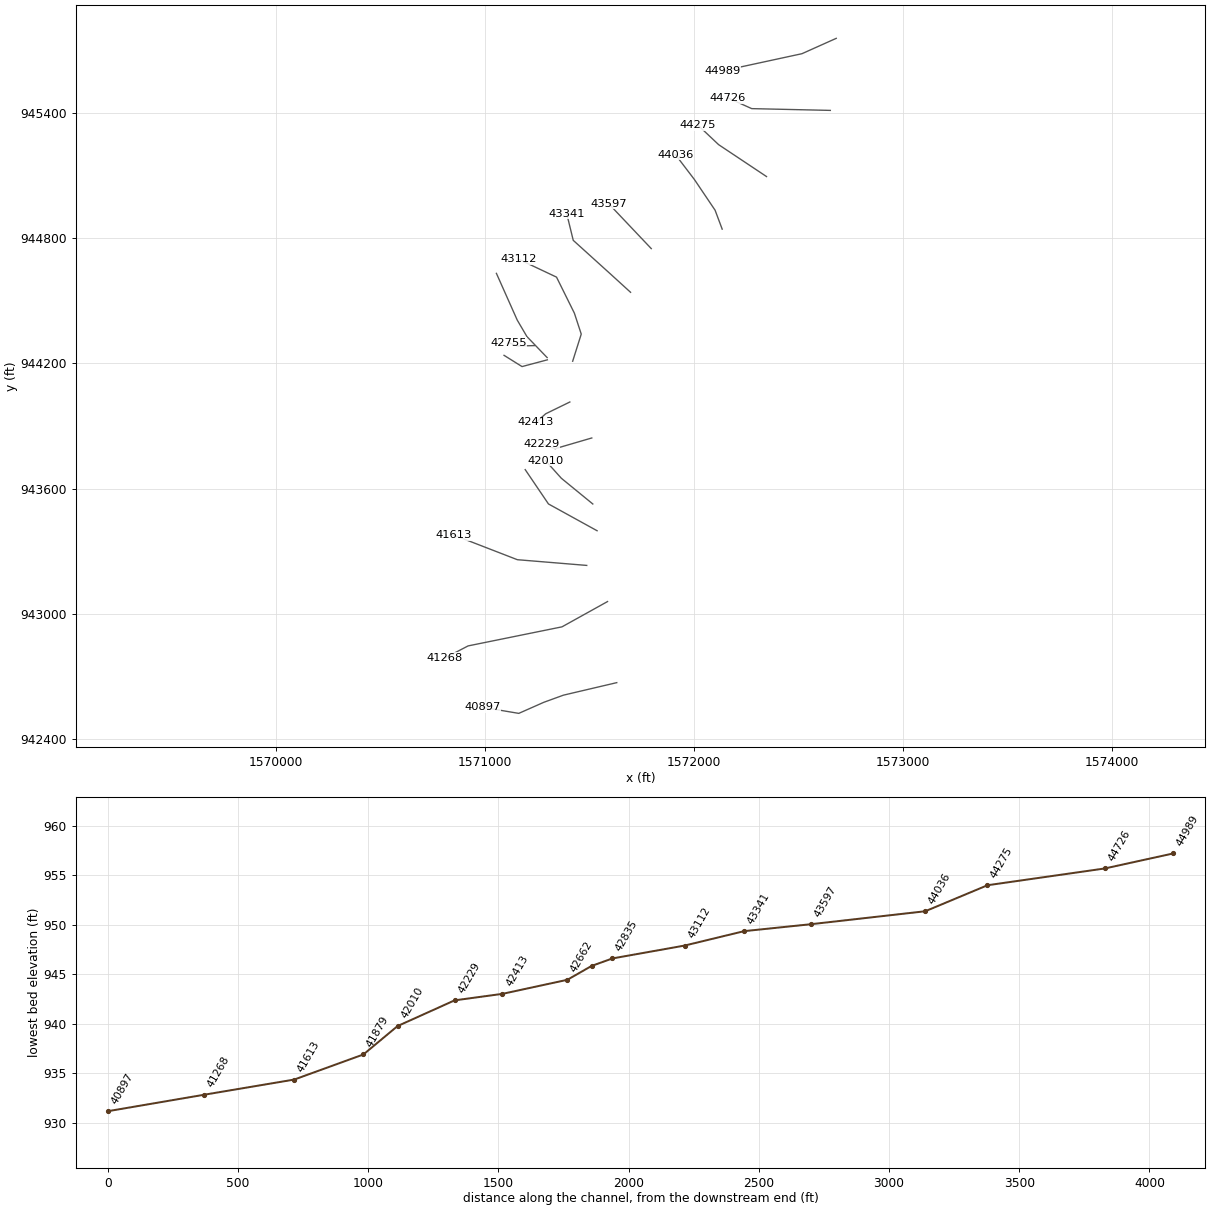
HEC-RAS study Grassy Creek.prj: Grassy Creek Limited Detail Study

--- Grassy Creek.g01 (geometry) --- (continued)

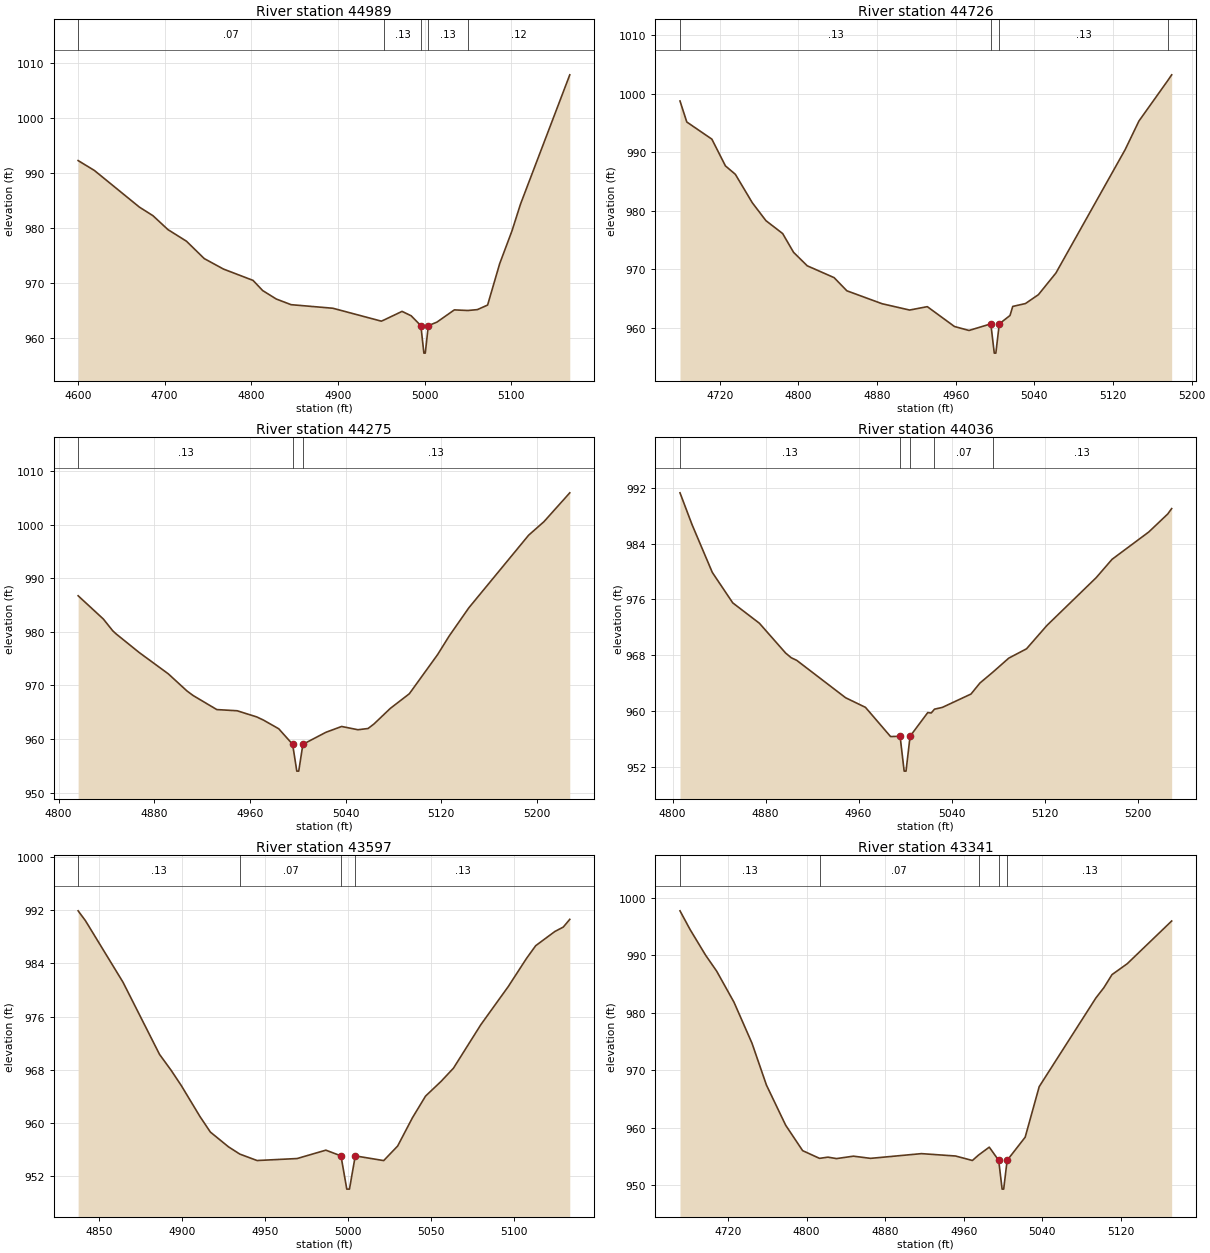
Type RM Length L Ch R = 1,44989,263,263,263
BEGIN DESCRIPTION:
Grassy Creek 85.0
END DESCRIPTION:
XS GIS Cut Line= 3
      1572680.99       945755.47      1572517.01       945681.96
      1572138.28       945600.00
#Sta/Elev= 30
  4600.3  992.27  4619.0  990.48  4670.9  983.81  4686.7  982.23  4703.9  979.71
  4725.3  977.59  4745.8  974.43  4768.0  972.52  4802.1  970.46  4813.2  968.61
  4828.9  967.07  4846.0  966.04  4894.2  965.39  4950.1  963.04  4953.7  963.29
  4974.0  964.82  4984.5  964.02  4995.7  962.22  4999.2  957.22  5000.8  957.22
  5004.3  962.22  5014.2  962.86  5034.3  965.09  5049.9  964.98  5060.9  965.14
  5072.7  965.97  5086.6  973.49  5100.8  979.47  5110.6  984.32  5167.5 1007.88
#Mann=5,-1,0
  4600.3    0.07       0  4953.7    0.13       0  4995.7    0.05       0
  5004.3    0.13       0  5049.9    0.12       0
Bank Sta=4995.7,5004.3
XS Rating Curve= 0
Exp/Cntr=0.3,0.1

Type RM Length L Ch R = 1,44726,451,451,451
BEGIN DESCRIPTION:
Grassy Creek 84.0
END DESCRIPTION:
XS GIS Cut Line= 3
      1572652.71       945410.62      1572276.76       945419.10
      1572163.72       945469.96
#Sta/Elev= 30
  4679.6  998.78  4686.5  995.19  4712.0  992.26  4725.8  987.69  4735.9  986.25
  4753.1  981.40  4767.0  978.33  4784.0  976.13  4795.1  972.92  4809.0  970.62
  4836.3  968.60  4849.3  966.35  4885.1  964.14  4913.1  963.06  4931.1  963.64
  4958.7  960.25  4973.5  959.57  4995.7  960.70  4999.2  955.70  5000.8  955.70
  5004.3  960.70  5015.2  962.13  5018.0  963.68  5030.9  964.17  5044.1  965.69
  5061.9  969.39  5132.3  990.47  5146.3  995.35  5175.8 1002.31  5179.6 1003.25
#Mann=4,-1,0
  4679.6    0.13       0  4995.7    0.05       0  5004.3    0.13       0
  5175.8    0.12       0
Bank Sta=4995.7,5004.3
XS Rating Curve= 0
Exp/Cntr=0.3,0.1

Type RM Length L Ch R = 1,44275,239,239,239
BEGIN DESCRIPTION:
Grassy Creek 83.0
END DESCRIPTION:
XS GIS Cut Line= 3
      1572347.44       945094.03      1572118.47       945246.68
      1572019.51       945339.99
#Sta/Elev= 30
  4816.3  986.71  4837.4  982.37  4845.2  980.19  4848.1  979.59  4867.4  976.12
  4891.7  972.15  4907.3  968.96  4912.5  968.10  4932.3  965.48  4949.3  965.26
  4965.7  964.11  4971.3  963.52  4984.1  961.90  4995.7  959.00  4999.2  954.00
  5000.8  954.00  5004.3  959.00  5023.5  961.24  5036.7  962.33  5050.3  961.72
  5058.8  961.95  5063.8  962.81  5077.4  965.70  5093.3  968.43  5117.0  975.75
  5126.6  979.19  5143.1  984.47  5193.1  998.01  5205.9 1000.53  5227.5 1005.91
#Mann=3,-1,0
  4816.3    0.13       0  4995.7    0.05       0  5004.3    0.13       0
Bank Sta=4995.7,5004.3
XS Rating Curve= 0
Exp/Cntr=0.3,0.1

Type RM Length L Ch R = 1,44036,439,439,439
BEGIN DESCRIPTION:
Grassy Creek 82.0
END DESCRIPTION:
XS GIS Cut Line= 4
      1572135.45       944842.44      1572101.51       944932.94
      1572002.59       945079.91      1571912.11       945198.66
#Sta/Elev= 30
  4806.3  991.30  4816.7  986.72  4834.1  979.88  4851.7  975.51  4874.6  972.59
  4897.2  968.31  4902.0  967.64  4906.7  967.27  4948.8  961.90  4965.9  960.52
  4987.5  956.33  4995.7  956.37  4999.2  951.37  5000.8  951.37  5004.3  956.37
  5019.5  959.77  5022.5  959.71  5025.3  960.26  5032.0  960.51  5056.7  962.43
  5064.4  964.01  5075.4  965.55  5089.2  967.58  5104.5  968.92  5122.1  972.28
  5164.4  979.12  5178.1  981.76  5209.7  985.68  5226.0  988.26  5229.4  989.04
#Mann=5,-1,0
  4806.3    0.13       0  4995.7    0.05       0  5004.3    0.13       0
  5025.3    0.07       0  5075.4    0.13       0
Bank Sta=4995.7,5004.3
XS Rating Curve= 0
Exp/Cntr=0.3,0.1

Type RM Length L Ch R = 1,43597,256,256,256
BEGIN DESCRIPTION:
Grassy Creek 81.0
END DESCRIPTION:
XS GIS Cut Line= 2
      1571796.26       944749.21      1571592.75       944964.02
#Sta/Elev= 30
  4837.5  991.91  4841.9  990.43  4864.5  981.18  4886.5  970.32  4893.5  967.92
  4899.6  965.63  4910.9  960.95  4917.1  958.64  4928.0  956.42  4934.8  955.33
  4945.2  954.36  4969.3  954.66  4986.6  955.92  4995.7  955.06  4999.2  950.06
  5000.8  950.06  5004.3  955.06  5021.4  954.35  5029.8  956.54  5038.7  960.79
  5046.6  964.05  5056.0  966.28  5063.4  968.25  5079.9  974.80  5096.4  980.53
  5107.4  984.77  5112.9  986.67  5124.4  988.80  5129.5  989.47  5133.4  990.63
#Mann=4,-1,0
  4837.5    0.13       0  4934.8    0.07       0  4995.7    0.05       0
  5004.3    0.13       0
Bank Sta=4995.7,5004.3
XS Rating Curve= 0
Exp/Cntr=0.3,0.1

Type RM Length L Ch R = 1,43341,229,229,229
BEGIN DESCRIPTION:
Grassy Creek 80.0
END DESCRIPTION:
XS GIS Cut Line= 4
      1571697.29       944540.08      1571601.22       944627.67
      1571423.15       944788.78      1571392.06       944915.99
#Sta/Elev= 30
  4670.9  997.75  4681.1  994.52  4696.9  990.06  4708.2  987.28  4725.9  981.87
  4744.3  974.72  4759.0  967.45  4778.6  960.47  4795.9  956.05  4813.1  954.71
  4821.7  954.92  4830.4  954.67  4847.7  955.09  4865.1  954.71  4917.0  955.53
  4951.7  955.12  4968.9  954.34  4975.3  955.30  4986.1  956.66  4995.7  954.36
  4999.2  949.36  5000.8  949.36  5004.3  954.36  5022.7  958.39  5037.0  967.18
  5094.7  982.58  5103.0  984.41  5111.2  986.66  5126.7  988.55  5172.0  995.98
#Mann=5,-1,0
  4670.9    0.13       0  4813.1    0.07       0  4975.3    0.13       0
  4995.7    0.05       0  5004.3    0.13       0
Bank Sta=4995.7,5004.3
XS Rating Curve= 0
Exp/Cntr=0.5,0.3

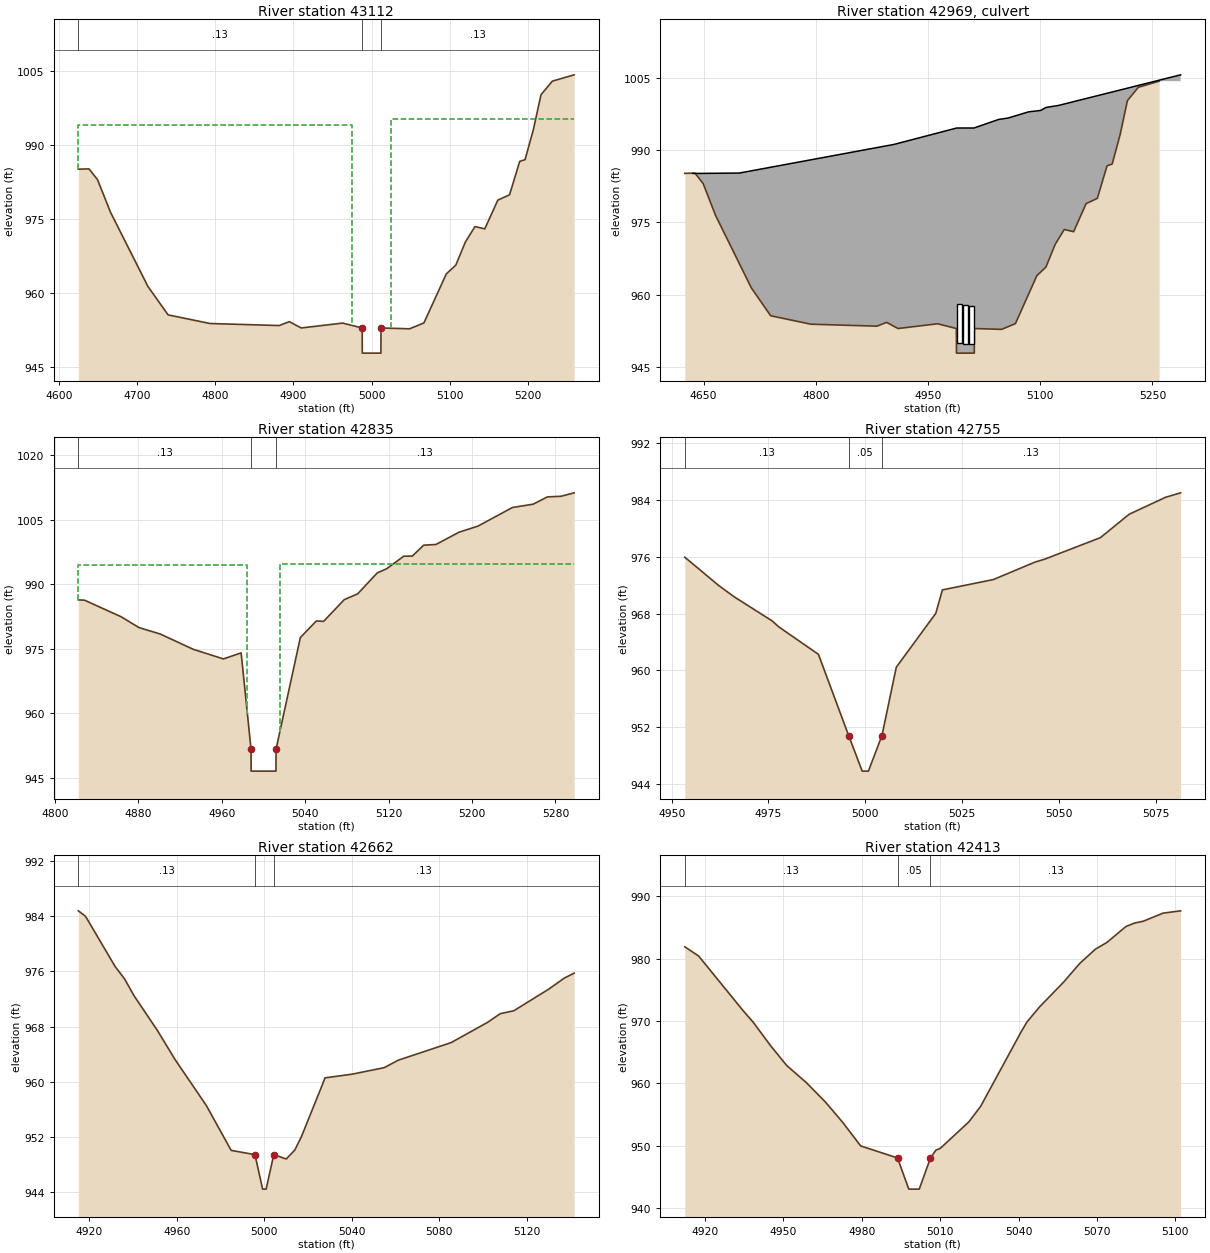
Type RM Length L Ch R = 1,43112,277,277,277
BEGIN DESCRIPTION:
Hwy-52 (GC) us
END DESCRIPTION:
XS GIS Cut Line= 5
      1571420.38       944210.22      1571461.45       944340.01
      1571428.59       944440.22      1571343.17       944612.72
      1571162.42       944698.16
#Sta/Elev= 30
  4625.0  985.19  4638.7  985.24  4649.6  983.05  4666.1  976.47  4713.9  961.44
  4739.8  955.65  4793.5  953.90  4881.8  953.49  4894.8  954.28  4910.0  953.00
  4962.9  953.99  4988.0  953.00  4988.1  947.90  5011.9  947.90  5012.0  953.00
  5048.6  952.83  5066.9  954.02  5095.5  963.95  5107.7  965.75  5120.0  970.45
  5132.2  973.55  5144.7  973.09  5161.4  978.91  5176.4  980.00  5189.4  986.77
  5196.2  987.11  5206.8  993.18  5216.6 1000.27  5231.1 1003.03  5259.0 1004.31
#Mann=3,-1,0
  4625.0    0.13       0  4988.0    0.05       0  5012.0    0.13       0
#XS Ineff=2,0
    0.00 4975.50  994.07 5024.50    0.00  995.30
Permanent Ineff=
       F       F
Bank Sta=4988,5012
XS Rating Curve= 0
Exp/Cntr=0.5,0.3

Type RM Length L Ch R =2,42969,,,
BEGIN DESCRIPTION:
Hwy-52 (GC) TOR
Structure ID: LDS_GC_07
Approximate Survey Structure
END DESCRIPTION:
Bridge Culvert--1,0,-1,-1,0
Deck Dist Width WeirC Skew NumUp NumDn MinLoCord MaxHiCord MaxSubmerge Is_Ogee
13,260,3,,13,13,,,0.95,0,1,1,,,
  4635.9  4697.7  4904.5  4988.5  5011.5  5044.4  5057.1  5084.5  5100.5  5107.2
  5108.3  5124.5  5287.7
  985.17  985.25  991.19  994.60  994.60  996.37  996.67  997.95  998.24  998.82
  998.88  999.28 1005.63
  927.90  927.90  927.90  927.90  927.90  927.90  927.90  927.90  927.90  927.90
  927.90  927.90  927.90
  4635.9  4697.7  4904.5  4988.5  5011.5  5044.4  5057.1  5084.5  5100.5  5107.2
  5108.3  5124.5  5287.7
  985.17  985.25  991.19  994.60  994.60  996.37  996.67  997.95  998.24  998.82
  998.88  999.28 1005.63
  926.60  926.60  926.60  926.60  926.60  926.60  926.60  926.60  926.60  926.60
  926.60  926.60  926.60
Culvert=2,8,7,260,0.012,0.4,1,8,1,950,4992,948,4992,Culvert #1,0,13
Culvert Bottom n=0.012
Culvert Bottom Depth=0
Culvert Depth Blocked=0
Culvert=2,8,7,260,0.012,0.4,1,8,1,949.8,5000,948,5000,Culvert #2,0,13
Culvert Bottom n=0.012
Culvert Bottom Depth=0
Culvert Depth Blocked=0
Culvert=2,8,7,260,0.012,0.4,1,8,1,949.7,5008,948,5008,Culvert #3,0,13
Culvert Bottom n=0.012
Culvert Bottom Depth=0
Culvert Depth Blocked=0
BC Design=,,0,,0,,,,,,

Type RM Length L Ch R = 1,42835,80,80,80
BEGIN DESCRIPTION:
Hwy-52 (GC) ds
END DESCRIPTION:
XS GIS Cut Line= 4
      1571298.24       944227.75      1571201.73       944328.01
      1571155.35       944406.99      1571055.69       944630.75
#Sta/Elev= 30
  4822.3  986.42  4828.3  986.34  4863.4  982.49  4880.5  979.97  4901.0  978.47
  4932.5  974.93  4961.5  972.69  4978.5  974.09  4988.0  951.70  4988.1  946.60
  5011.9  946.60  5012.0  951.70  5035.3  977.66  5050.7  981.52  5057.6  981.41
  5077.4  986.47  5090.3  987.82  5109.1  992.69  5118.2  993.67  5134.5  996.57
  5142.8  996.61  5153.6  999.14  5165.4  999.30  5187.5 1002.15  5205.7 1003.57
  5238.8 1007.90  5258.7 1008.67  5272.3 1010.36  5285.4 1010.51  5298.0 1011.31
#Mann=3,-1,0
  4822.3    0.13       0  4988.0    0.05       0  5012.0    0.13       0
#XS Ineff=2,0
    0.00 4984.50  994.44 5015.50    0.00  994.82
Permanent Ineff=
       F       F
Bank Sta=4988,5012
XS Rating Curve= 0
Exp/Cntr=0.5,0.3

Type RM Length L Ch R = 1,42755,93,93,93
BEGIN DESCRIPTION:
Grassy Creek 79.5
END DESCRIPTION:
XS GIS Cut Line= 3
      1571237.59       944285.05      1571157.72       944283.13
      1571112.48       944299.49
#Sta/Elev= 21
  4953.4  975.92  4962.2  971.92  4966.2  970.33  4975.9  966.98  4977.7  966.11
  4987.9  962.26  4995.7  950.84  4999.2  945.84  5000.8  945.84  5004.3  950.84
  5008.0  960.45  5018.2  968.03  5019.9  971.32  5033.1  972.78  5033.3  972.83
  5043.8  975.23  5046.3  975.64  5060.7  978.67  5068.1  981.95  5077.5  984.34
  5081.4  984.97
#Mann=3,-1,0
  4953.4    0.13       0  4995.7    0.05       0  5004.3    0.13       0
Bank Sta=4995.7,5004.3
XS Rating Curve= 0
Exp/Cntr=0.3,0.1

Type RM Length L Ch R = 1,42662,249,249,249
BEGIN DESCRIPTION:
Grassy Creek 79.0
END DESCRIPTION:
XS GIS Cut Line= 3
      1571299.30       944216.90      1571178.27       944184.63
      1571092.17       944238.44
#Sta/Elev= 29
  4914.9  984.79  4918.0  984.05  4918.7  983.73  4931.8  976.68  4936.1  974.90
  4940.3  972.52  4951.1  967.43  4959.1  963.25  4973.5  956.54  4984.8  950.06
  4995.7  949.44  4999.2  944.44  5000.8  944.44  5004.3  949.44  5010.0  948.81
  5013.9  950.10  5016.9  952.01  5026.6  959.64  5027.7  960.57  5040.2  961.11
  5054.8  962.05  5061.3  963.14  5085.4  965.68  5102.1  968.62  5107.9  969.88
  5114.1  970.30  5130.2  973.46  5137.1  975.02  5141.7  975.76
#Mann=3,-1,0
  4914.9    0.13       0  4995.7    0.05       0  5004.3    0.13       0
Bank Sta=4995.7,5004.3
XS Rating Curve= 0
Exp/Cntr=0.3,0.1

Type RM Length L Ch R = 1,42413,184,184,184
BEGIN DESCRIPTION:
Grassy Creek 78.0
END DESCRIPTION:
XS GIS Cut Line= 3
      1571406.94       944015.15      1571291.26       943958.65
      1571245.55       943918.32
#Sta/Elev= 30
  4912.3  981.90  4917.6  980.42  4934.6  971.66  4938.6  969.73  4945.2  965.99
  4951.3  962.85  4958.8  960.11  4966.2  956.95  4972.7  953.74  4979.6  949.95
  4993.7  948.02  4998.0  943.02  5002.0  943.02  5006.3  948.02  5008.4  949.28
  5010.1  949.58  5021.0  953.82  5025.5  956.31  5041.0  968.27  5043.2  969.83
  5048.1  972.29  5057.3  976.26  5063.4  979.23  5069.4  981.52  5073.8  982.60
  5081.1  985.16  5084.4  985.71  5087.7  986.00  5095.3  987.30  5102.0  987.67
#Mann=3,-1,0
  4912.3    0.13       0  4993.7    0.05       0  5006.3    0.13       0
Bank Sta=4993.7,5006.3
XS Rating Curve= 0
Exp/Cntr=0.3,0.1

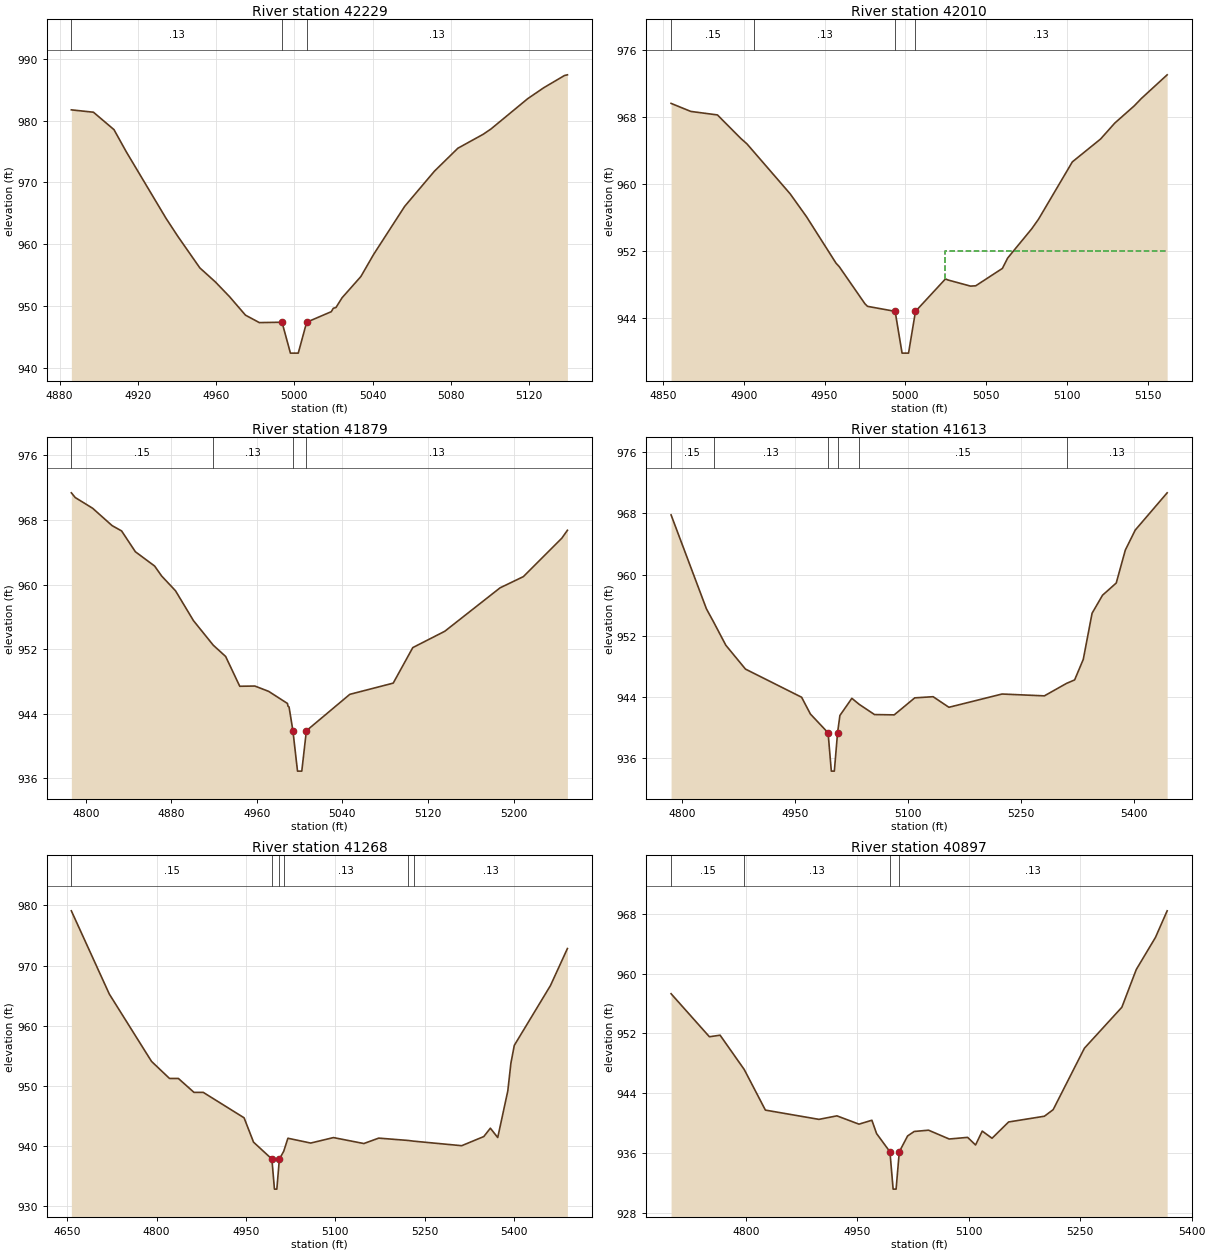
Type RM Length L Ch R = 1,42229,219,219,219
BEGIN DESCRIPTION:
Grassy Creek 77.0
END DESCRIPTION:
XS GIS Cut Line= 3
      1571511.83       943842.97      1571336.99       943791.86
      1571269.77       943816.06
#Sta/Elev= 30
  4886.0  981.73  4897.3  981.35  4907.8  978.53  4914.0  974.99  4934.4  964.18
  4940.4  961.28  4951.7  956.15  4959.6  953.89  4966.9  951.49  4975.0  948.51
  4982.1  947.30  4993.7  947.36  4998.0  942.36  5002.0  942.36  5006.3  947.36
  5018.9  949.07  5019.9  949.61  5021.3  949.75  5024.4  951.32  5034.0  954.75
  5040.5  958.32  5056.4  966.11  5071.6  971.80  5083.6  975.52  5096.5  977.77
  5100.5  978.63  5119.3  983.54  5127.5  985.31  5138.1  987.29  5139.6  987.40
#Mann=3,-1,0
  4886.0    0.13       0  4993.7    0.05       0  5006.3    0.13       0
Bank Sta=4993.7,5006.3
XS Rating Curve= 0
Exp/Cntr=0.3,0.1

Type RM Length L Ch R = 1,42010,131,131,131
BEGIN DESCRIPTION:
Grassy Creek 76.0
END DESCRIPTION:
XS GIS Cut Line= 3
      1571516.70       943527.07      1571366.20       943650.20
      1571290.94       943734.02
#Sta/Elev= 30
  4855.0  969.65  4867.2  968.69  4883.7  968.27  4898.2  965.45  4902.0  964.80
  4906.6  963.77  4928.7  958.83  4938.8  956.10  4957.1  950.53  4959.1  950.11
  4975.0  945.67  4976.6  945.36  4993.7  944.76  4998.0  939.76  5002.0  939.76
  5006.3  944.76  5024.9  948.65  5026.3  948.52  5040.4  947.78  5043.6  947.82
  5060.1  949.90  5063.4  951.15  5078.3  954.65  5082.5  955.80  5103.4  962.65
  5120.9  965.39  5129.7  967.30  5141.7  969.35  5146.2  970.25  5162.1  973.07
#Mann=4,-1,0
  4855.0    0.15       0  4906.6    0.13       0  4993.7    0.05       0
  5006.3    0.13       0
#XS Ineff=2,0
       0                 5024.60    0.00  951.93
Permanent Ineff=
       F       F
Bank Sta=4993.7,5006.3
XS Rating Curve= 0
Exp/Cntr=0.3,0.1

Type RM Length L Ch R = 1,41879,266,266,266
BEGIN DESCRIPTION:
Grassy Creek 75.0
END DESCRIPTION:
XS GIS Cut Line= 3
      1571537.19       943398.98      1571304.63       943527.23
      1571193.44       943691.45
#Sta/Elev= 30
  4786.5  971.36  4790.2  970.77  4806.4  969.45  4824.6  967.30  4833.5  966.64
  4846.4  964.06  4864.4  962.29  4871.0  961.05  4883.9  959.23  4900.7  955.53
  4919.2  952.49  4930.8  951.09  4944.0  947.40  4958.1  947.43  4971.0  946.77
  4988.6  945.27  4989.1  944.94  4990.1  944.83  4993.7  941.89  4998.0  936.89
  5002.0  936.89  5006.3  941.89  5046.9  946.40  5087.5  947.79  5105.8  952.19
  5135.7  954.21  5187.4  959.59  5209.2  960.98  5245.1  965.73  5250.4  966.72
#Mann=4,-1,0
  4786.5    0.15       0  4919.2    0.13       0  4993.7    0.05       0
  5006.3    0.13       0
Bank Sta=4993.7,5006.3
XS Rating Curve= 0
Exp/Cntr=0.3,0.1

Type RM Length L Ch R = 1,41613,345,345,345
BEGIN DESCRIPTION:
Grassy Creek 74.5
END DESCRIPTION:
XS GIS Cut Line= 3
      1571487.63       943233.06      1571155.84       943260.43
      1570851.42       943378.43
#Sta/Elev= 30
  4785.0  967.78  4832.0  955.52  4841.5  953.81  4857.8  950.77  4883.9  947.66
  4958.5  943.99  4970.2  941.80  4993.7  939.35  4998.0  934.35  5002.0  934.35
  5006.3  939.35  5009.4  941.61  5025.3  943.85  5035.1  943.06  5055.4  941.73
  5081.6  941.69  5108.9  943.91  5133.3  944.06  5154.3  942.68  5224.9  944.41
  5281.2  944.17  5310.7  945.80  5321.4  946.25  5332.9  948.93  5344.6  954.95
  5358.5  957.30  5376.7  958.89  5388.8  963.19  5401.9  965.79  5444.4  970.66
#Mann=6,-1,0
  4785.0    0.15       0  4841.5    0.13       0  4993.7    0.05       0
  5006.3    0.13       0  5035.1    0.15       0  5310.7    0.13       0
Bank Sta=4993.7,5006.3
XS Rating Curve= 0
Exp/Cntr=0.3,0.1

Type RM Length L Ch R = 1,41268,371,371,371
BEGIN DESCRIPTION:
Grassy Creek 74.0
END DESCRIPTION:
XS GIS Cut Line= 4
      1571587.20       943060.14      1571369.28       942939.07
      1570920.29       942847.87      1570809.03       942789.92
#Sta/Elev= 30
  4657.0  979.09  4720.8  965.24  4791.6  954.06  4821.8  951.22  4836.7  951.22
  4863.0  948.90  4878.4  948.91  4947.0  944.68  4962.9  940.63  4993.7  937.82
  4998.0  932.82  5002.0  932.82  5006.3  937.82  5013.6  939.12  5020.6  941.28
  5058.9  940.48  5097.1  941.39  5148.1  940.40  5173.1  941.30  5222.6  940.91
  5232.2  940.79  5312.4  940.04  5349.5  941.56  5360.5  942.95  5372.9  941.40
  5389.8  949.14  5395.0  953.75  5400.7  956.72  5461.4  966.66  5489.9  972.82
#Mann=6,-1,0
  4657.0    0.15       0  4993.7    0.05       0  5006.3    0.15       0
  5013.6    0.13       0  5222.6    0.15       0  5232.2    0.13       0
Bank Sta=4993.7,5006.3
XS Rating Curve= 0
Exp/Cntr=0.3,0.1

Type RM Length L Ch R = 1,40897,257,257,257
BEGIN DESCRIPTION:
Grassy Creek 73.5
END DESCRIPTION:
XS GIS Cut Line= 5
      1571631.29       942672.08      1571376.46       942612.22
      1571282.40       942578.02      1571162.68       942525.00
      1570989.90       942554.08
#Sta/Elev= 30
  4699.0  957.31  4750.6  951.55  4765.0  951.76  4797.6  947.15  4826.0  941.73
  4898.1  940.49  4922.3  940.96  4952.0  939.85  4969.4  940.37  4975.7  938.59
  4993.7  936.15  4998.0  931.15  5002.0  931.15  5006.3  936.15  5017.5  938.27
  5026.4  938.87  5045.7  939.04  5073.5  937.86  5098.3  938.08  5109.0  937.06
  5118.0  938.92  5131.2  937.96  5153.5  940.14  5201.7  940.91  5213.5  941.79
  5255.6  950.02  5306.0  955.50  5325.4  960.55  5351.3  964.86  5367.0  968.41
#Mann=4,-1,0
  4699.0    0.15       0  4797.6    0.13       0  4993.7    0.05       0
  5006.3    0.13       0
Bank Sta=4993.7,5006.3
XS Rating Curve= 0
Exp/Cntr=0.3,0.1