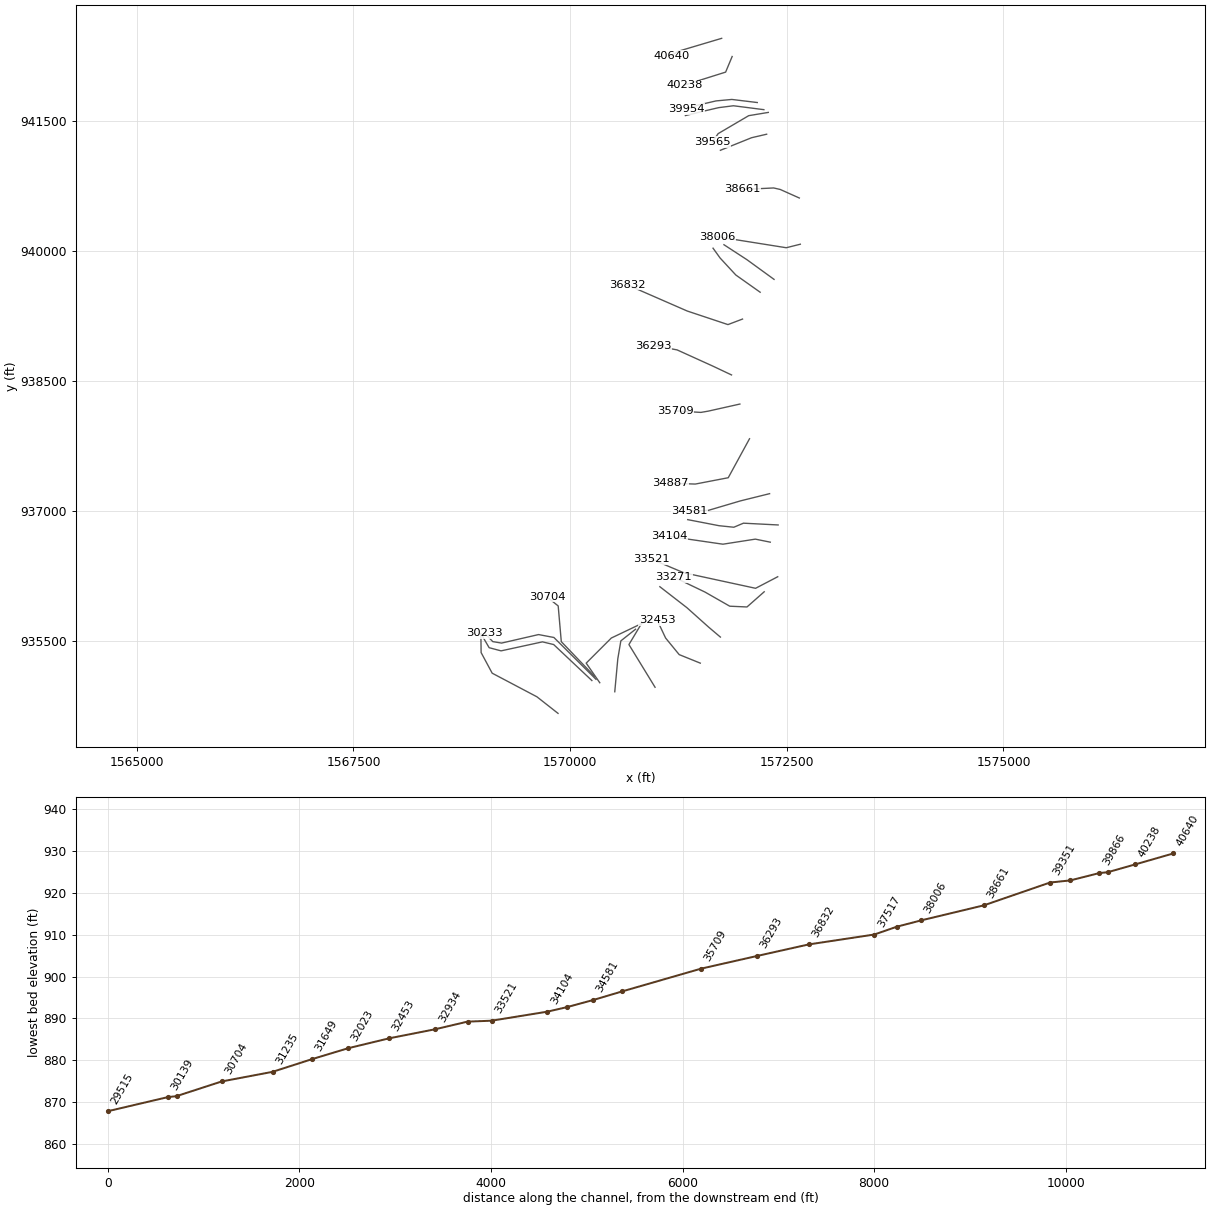
HEC-RAS study Grassy Creek.prj: Grassy Creek Limited Detail Study

--- Grassy Creek.g01 (geometry) --- (continued)

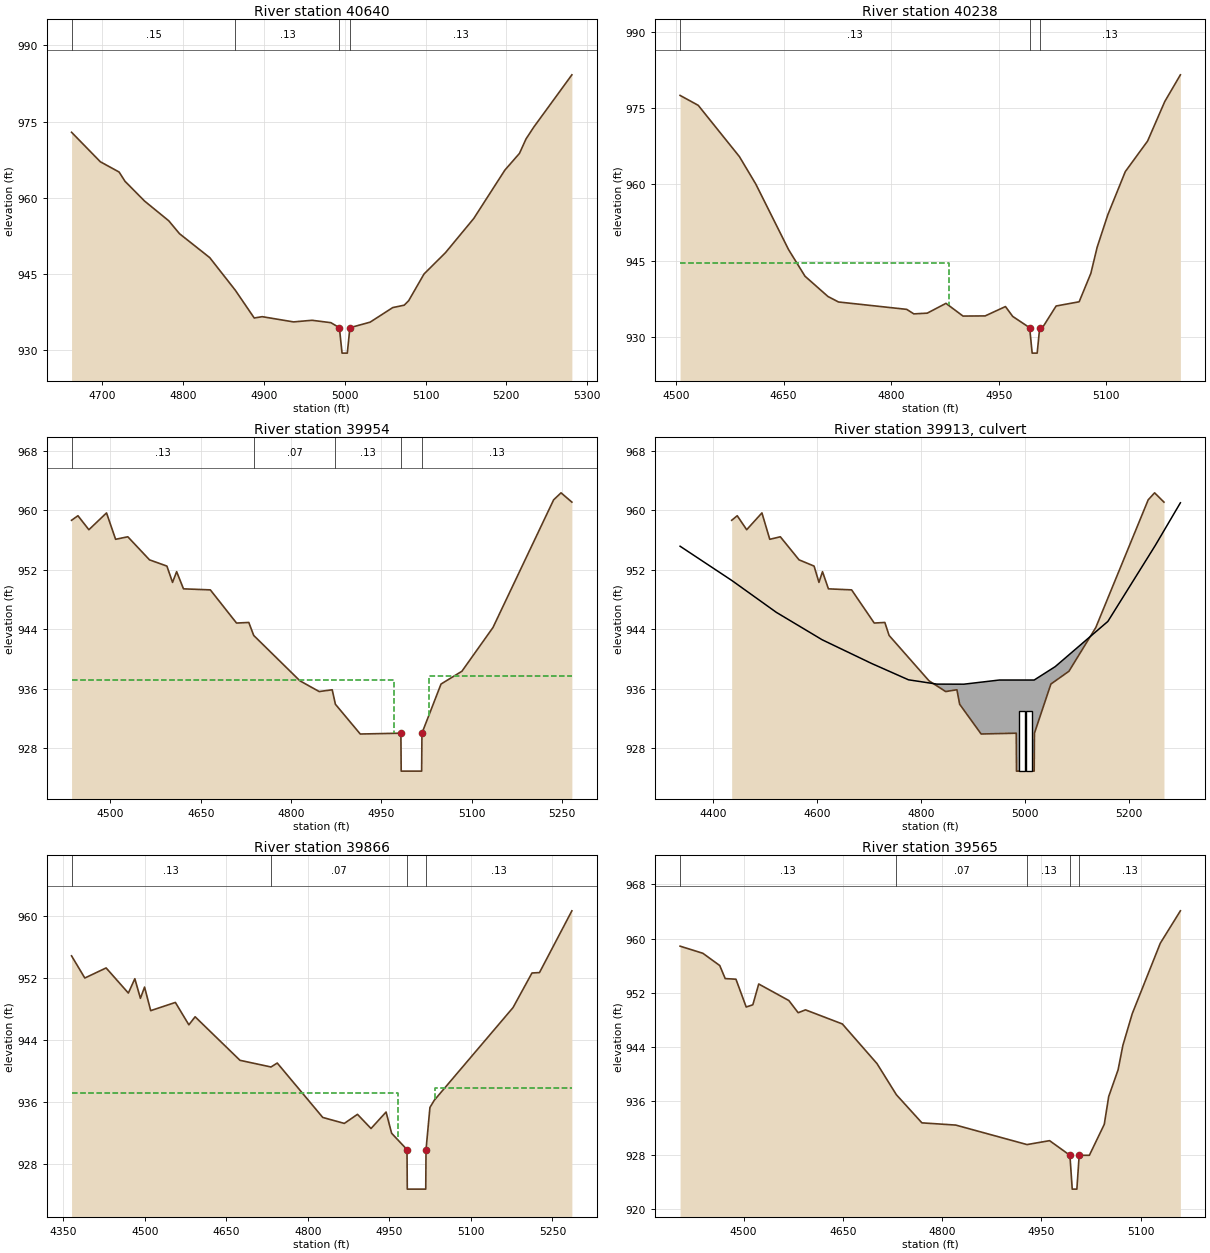
Type RM Length L Ch R = 1,40640,402,402,402
BEGIN DESCRIPTION:
Grassy Creek 73.0
END DESCRIPTION:
XS GIS Cut Line= 3
      1571748.56       942457.52      1571242.84       942306.88
      1571167.52       942255.78
#Sta/Elev= 30
  4662.3  972.89  4697.9  967.09  4721.1  965.07  4728.4  963.25  4752.6  959.36
  4782.5  955.48  4795.8  952.94  4833.2  948.23  4864.9  941.80  4888.2  936.36
  4898.1  936.62  4936.8  935.59  4959.6  935.91  4983.0  935.44  4993.5  934.45
  4996.8  929.45  5003.3  929.45  5006.5  934.45  5031.5  935.54  5059.5  938.41
  5073.7  938.88  5079.2  939.77  5098.2  945.02  5124.7  949.21  5159.7  955.94
  5198.2  965.46  5216.2  968.74  5224.3  971.58  5233.9  973.91  5281.0  984.19
#Mann=4,-1,0
  4662.3    0.15       0  4864.9    0.13       0  4993.5    0.05       0
  5006.5    0.13       0
Bank Sta=4993.5,5006.5
XS Rating Curve= 0
Exp/Cntr=0.3,0.1

Type RM Length L Ch R = 1,40238,284,284,284
BEGIN DESCRIPTION:
Grassy Creek 72.0
END DESCRIPTION:
XS GIS Cut Line= 3
      1571869.64       942247.68      1571794.32       942067.45
      1571315.50       941916.81
#Sta/Elev= 30
  4505.8  977.49  4531.1  975.54  4588.5  965.45  4611.3  960.06  4657.1  947.14
  4679.9  941.93  4711.9  937.94  4726.6  936.86  4821.6  935.41  4831.6  934.52
  4850.2  934.66  4876.4  936.59  4900.1  934.09  4931.0  934.12  4959.3  935.96
  4969.4  934.02  4993.0  931.80  4996.5  926.80  5003.5  926.80  5007.0  931.80
  5011.3  931.91  5029.9  936.07  5062.0  936.90  5078.3  942.49  5087.1  947.64
  5101.9  954.00  5126.3  962.50  5157.4  968.52  5181.3  976.28  5203.1  981.54
#Mann=3,-1,0
  4505.8    0.13       0  4993.0    0.05       0  5007.0    0.13       0
#XS Ineff=2,0
    0.00 4880.30  944.60               0
Permanent Ineff=
       F       F
Bank Sta=4993,5007
XS Rating Curve= 0
Exp/Cntr=0.5,0.3

Type RM Length L Ch R = 1,39954,88,88,88
BEGIN DESCRIPTION:
Pinnacle Hotel Rd (GC) us
END DESCRIPTION:
XS GIS Cut Line= 5
      1572159.63       941716.15      1571866.11       941751.87
      1571682.88       941734.79      1571463.93       941683.55
      1571344.35       941641.61
#Sta/Elev= 30
  4435.3  958.68  4445.9  959.29  4464.1  957.41  4493.4  959.67  4508.5  956.12
  4528.8  956.46  4564.8  953.36  4593.7  952.52  4603.1  950.33  4609.9  951.77
  4621.3  949.46  4665.9  949.32  4709.4  944.86  4729.8  944.94  4738.0  943.19
  4814.8  937.09  4846.8  935.65  4868.4  935.89  4873.7  933.94  4915.0  929.94
  4982.5  930.05  4983.0  924.95  5017.0  924.95  5017.5  930.05  5049.2  936.66
  5083.9  938.38  5135.5  944.26  5236.3  961.43  5248.6  962.37  5266.6  961.12
#Mann=5,-1,0
  4435.3    0.13       0  4738.0    0.07       0  4873.7    0.13       0
  4982.5    0.05       0  5017.5    0.13       0
#XS Ineff=2,0
    0.00 4971.50  937.20 5028.50    0.00  937.80
Permanent Ineff=
       F       F
Bank Sta=4982.5,5017.5
XS Rating Curve= 0
Exp/Cntr=0.5,0.3

Type RM Length L Ch R =2,39913,,,
BEGIN DESCRIPTION:
Pinnacle Hotel Rd (GC) TOR
Structure ID: LDS_GC_06
Approximate Survey Structure
END DESCRIPTION:
Bridge Culvert--1,0,-1,-1,0
Deck Dist Width WeirC Skew NumUp NumDn MinLoCord MaxHiCord MaxSubmerge Is_Ogee
16,50,3,,14,14,,,0.95,0,1,1,,,
  4336.0  4435.8  4521.1  4609.3  4704.5  4775.2  4830.0  4881.6  4950.0  5017.0
  5057.4  5158.7  5249.4  5298.2
  955.19  950.57  946.30  942.61  939.42  937.23  936.65  936.64  937.20  937.20
  939.00  945.08  955.24  961.03
  905.00  905.00  905.00  905.00  905.00  905.00  905.00  905.00  905.00  905.00
  905.00  905.00  905.00  905.00
  4336.0  4435.8  4521.1  4609.3  4704.5  4775.2  4830.0  4881.6  4950.0  5017.0
  5057.4  5158.7  5249.4  5298.2
  955.19  950.57  946.30  942.61  939.42  937.23  936.65  936.64  937.20  937.20
  939.00  945.08  955.24  961.03
  904.75  904.75  904.75  904.75  904.75  904.75  904.75  904.75  904.75  904.75
  904.75  904.75  904.75  904.75
Culvert=2,8,12,50,0.012,0.4,1,8,1,925,4993.5,924.75,4993.5,Culvert #1,0,16
Culvert Bottom n=0.012
Culvert Bottom Depth=0
Culvert Depth Blocked=0
Culvert=2,8,12,50,0.012,0.4,1,8,1,925,5006.5,924.75,5006.5,Culvert #2,0,16
Culvert Bottom n=0.012
Culvert Bottom Depth=0
Culvert Depth Blocked=0
BC Design=,,0,,0,,,,,,

Type RM Length L Ch R = 1,39866,301,301,301
BEGIN DESCRIPTION:
Pinnacle Hotel Rd (GC) ds
END DESCRIPTION:
XS GIS Cut Line= 5
      1572235.72       941633.85      1571884.74       941678.89
      1571713.93       941657.15      1571527.60       941613.67
      1571330.37       941565.53
#Sta/Elev= 30
  4365.4  954.85  4389.8  951.99  4429.0  953.29  4469.9  950.05  4481.8  951.90
  4492.1  949.37  4499.7  950.82  4511.0  947.78  4556.4  948.84  4581.2  945.95
  4592.7  946.99  4675.3  941.37  4732.3  940.51  4743.8  941.02  4827.5  934.00
  4867.2  933.23  4891.4  934.40  4916.3  932.57  4944.0  934.70  4954.2  931.96
  4982.5  929.85  4983.0  924.75  5017.0  924.75  5017.5  929.85  5024.7  935.29
  5032.6  936.21  5177.5  948.17  5212.4  952.64  5226.2  952.69  5285.8  960.66
#Mann=4,-1,0
  4365.4    0.13       0  4732.3    0.07       0  4982.5    0.05       0
  5017.5    0.13       0
#XS Ineff=2,0
    0.00 4965.50  937.20 5034.50    0.00  937.76
Permanent Ineff=
       F       F
Bank Sta=4982.5,5017.5
XS Rating Curve= 0
Exp/Cntr=0.5,0.3

Type RM Length L Ch R = 1,39565,214,214,214
BEGIN DESCRIPTION:
Grassy Creek 71.0
END DESCRIPTION:
XS GIS Cut Line= 4
      1572286.62       941602.05      1572060.65       941564.39
      1571708.24       941357.25      1571640.97       941260.39
#Sta/Elev= 30
  4404.1  958.89  4438.5  957.84  4464.0  956.03  4472.3  954.10  4488.5  954.01
  4504.0  949.90  4514.0  950.23  4522.9  953.30  4568.4  950.86  4582.5  949.06
  4593.6  949.48  4649.2  947.40  4701.6  941.54  4730.8  936.95  4769.4  932.79
  4820.6  932.46  4928.2  929.58  4962.3  930.16  4993.0  928.00  4996.5  923.00
  5003.5  923.00  5007.0  928.00  5022.4  928.00  5044.9  932.57  5051.6  936.68
  5065.8  940.63  5073.0  944.23  5087.1  948.90  5129.5  959.32  5159.9  964.11
#Mann=5,-1,0
  4404.1    0.13       0  4730.8    0.07       0  4928.2    0.13       0
  4993.0    0.05       0  5007.0    0.13       0
Bank Sta=4993,5007
XS Rating Curve= 0
Exp/Cntr=0.3,0.1

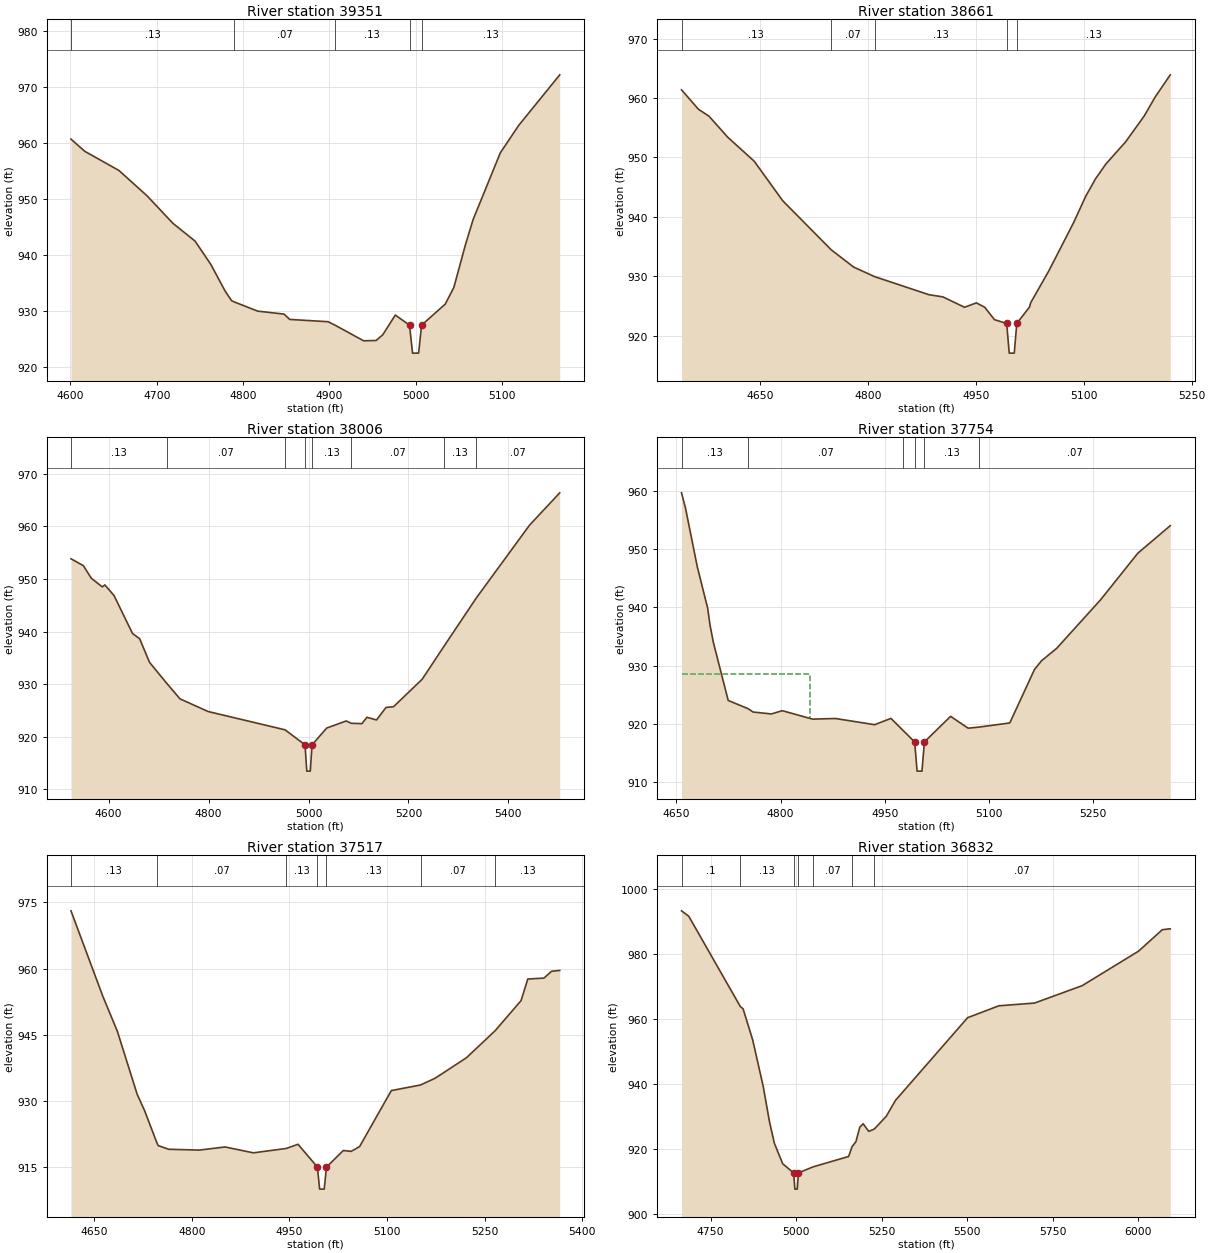
Type RM Length L Ch R = 1,39351,690,690,690
BEGIN DESCRIPTION:
Grassy Creek 70.0
END DESCRIPTION:
XS GIS Cut Line= 3
      1572267.70       941350.36      1572093.65       941309.75
      1571734.01       941164.73
#Sta/Elev= 30
  4600.6  960.70  4616.6  958.52  4656.2  955.10  4688.8  950.57  4718.7  945.67
  4744.4  942.49  4762.7  938.32  4779.3  933.56  4786.7  931.85  4789.6  931.64
  4817.0  929.98  4847.5  929.45  4854.2  928.50  4898.6  928.09  4906.7  927.47
  4939.8  924.68  4954.3  924.74  4962.0  925.76  4976.5  929.28  4993.0  927.48
  4996.5  922.48  5003.5  922.48  5007.0  927.48  5034.4  931.23  5044.4  934.22
  5057.6  941.73  5066.7  946.34  5098.2  958.24  5119.5  963.14  5167.1  972.18
#Mann=5,-1,0
  4600.6    0.13       0  4789.6    0.07       0  4906.7    0.13       0
  4993.0    0.05       0  5007.0    0.13       0
Bank Sta=4993,5007
XS Rating Curve= 0
Exp/Cntr=0.3,0.1

Type RM Length L Ch R = 1,38661,655,655,655
BEGIN DESCRIPTION:
Grassy Creek 69.0
END DESCRIPTION:
XS GIS Cut Line= 4
      1572644.67       940613.68      1572424.29       940712.28
      1572348.88       940729.68      1571989.22       940712.28
#Sta/Elev= 30
  4541.3  961.41  4564.9  958.12  4579.5  956.96  4605.4  953.43  4642.3  949.37
  4681.9  942.71  4749.1  934.46  4780.4  931.53  4809.6  929.92  4884.9  926.88
  4904.3  926.51  4934.4  924.76  4950.9  925.50  4962.5  924.76  4976.0  922.67
  4993.0  922.03  4996.5  917.03  5003.5  917.03  5007.0  922.03  5024.8  924.81
  5026.2  925.50  5051.3  930.84  5086.0  939.04  5102.7  943.45  5116.4  946.41
  5130.8  948.91  5157.9  952.59  5184.0  956.99  5199.0  960.15  5220.2  963.93
#Mann=5,-1,0
  4541.3    0.13       0  4749.1    0.07       0  4809.6    0.13       0
  4993.0    0.05       0  5007.0    0.13       0
Bank Sta=4993,5007
XS Rating Curve= 0
Exp/Cntr=0.3,0.1

Type RM Length L Ch R = 1,38006,252,252,252
BEGIN DESCRIPTION:
Grassy Creek 68.0
END DESCRIPTION:
XS GIS Cut Line= 3
      1572656.35       940080.01      1572493.90       940039.39
      1571693.36       940167.02
#Sta/Elev= 30
  4524.6  953.86  4549.4  952.54  4565.3  950.15  4587.2  948.51  4592.4  948.88
  4610.8  946.85  4647.7  939.64  4662.0  938.64  4681.8  934.14  4716.4  930.13
  4742.8  927.19  4798.9  924.78  4953.1  921.29  4993.0  918.43  4996.5  913.43
  5003.5  913.43  5007.0  918.43  5036.5  921.64  5075.4  922.98  5085.4  922.54
  5106.8  922.47  5116.9  923.68  5136.1  923.17  5155.0  925.55  5170.2  925.70
  5227.4  930.92  5271.4  937.24  5335.7  946.39  5442.4  960.27  5502.7  966.41
#Mann=8,-1,0
  4524.6    0.13       0  4716.4    0.07       0  4953.1    0.13       0
  4993.0    0.05       0  5007.0    0.13       0  5085.4    0.07       0
  5271.4    0.13       0  5335.7    0.07       0
Bank Sta=4993,5007
XS Rating Curve= 0
Exp/Cntr=0.3,0.1

Type RM Length L Ch R = 1,37754,237,237,237
BEGIN DESCRIPTION:
Grassy Creek 67.5
END DESCRIPTION:
XS GIS Cut Line= 3
      1572353.04       939673.93      1572040.06       939901.40
      1571774.98       940074.13
#Sta/Elev= 30
  4657.5  959.63  4663.2  957.04  4680.2  946.96  4695.2  939.84  4698.5  936.99
  4703.3  934.01  4724.7  924.04  4753.4  922.63  4760.5  922.06  4786.8  921.73
  4802.5  922.29  4846.2  920.84  4879.0  920.95  4935.4  919.89  4958.9  920.97
  4976.3  918.91  4993.0  916.93  4996.5  911.93  5003.5  911.93  5007.0  916.93
  5044.7  921.32  5069.9  919.29  5085.1  919.47  5129.9  920.19  5165.4  929.35
  5175.5  930.84  5197.3  932.97  5260.5  941.29  5314.1  949.28  5360.8  954.00
#Mann=6,-1,0
  4657.5    0.13       0  4753.4    0.07       0  4976.3    0.13       0
  4993.0    0.05       0  5007.0    0.13       0  5085.1    0.07       0
#XS Ineff=2,0
    0.00 4841.80  928.66               0
Permanent Ineff=
       F       F
Bank Sta=4993,5007
XS Rating Curve= 0
Exp/Cntr=0.3,0.1

Type RM Length L Ch R = 1,37517,685,685,685
BEGIN DESCRIPTION:
Grassy Creek 67.0
END DESCRIPTION:
XS GIS Cut Line= 4
      1572192.72       939525.60      1571912.16       939724.33
      1571730.94       939920.16      1571649.08       940034.19
#Sta/Elev= 30
  4614.4  973.09  4663.3  953.75  4685.6  945.83  4716.1  931.54  4727.5  927.83
  4746.4  920.55  4748.3  919.93  4764.5  919.08  4811.8  918.89  4851.1  919.60
  4894.6  918.27  4945.2  919.26  4963.3  920.21  4993.0  915.05  4996.5  910.05
  5003.5  910.05  5007.0  915.05  5032.9  918.80  5044.9  918.60  5057.9  919.69
  5106.6  932.37  5151.5  933.64  5174.1  935.18  5222.2  939.83  5266.2  945.94
  5306.0  952.76  5316.3  957.64  5341.1  957.85  5352.8  959.39  5365.4  959.59
#Mann=7,-1,0
  4614.4    0.13       0  4746.4    0.07       0  4945.2    0.13       0
  4993.0    0.05       0  5007.0    0.13       0  5151.5    0.07       0
  5266.2    0.13       0
Bank Sta=4993,5007
XS Rating Curve= 0
Exp/Cntr=0.3,0.1

Type RM Length L Ch R = 1,36832,539,539,539
BEGIN DESCRIPTION:
Grassy Creek 66.0
END DESCRIPTION:
XS GIS Cut Line= 4
      1571989.27       939215.71      1571821.02       939151.89
      1571351.16       939308.51      1570660.91       939610.13
#Sta/Elev= 30
  4665.2  993.34  4686.3  991.69  4837.0  963.90  4845.2  963.17  4873.0  953.71
  4904.1  939.27  4922.1  928.55  4936.6  921.79  4961.0  915.48  4993.0  912.68
  4996.5  907.68  5003.5  907.68  5007.0  912.68  5049.6  914.53  5153.6  917.73
  5163.6  920.74  5175.0  922.29  5186.2  926.73  5196.1  927.80  5212.5  925.45
  5228.8  926.19  5263.4  930.06  5290.7  935.01  5501.4  960.45  5592.8  964.11
  5697.0  964.95  5836.1  970.30  6001.1  980.93  6070.4  987.53  6093.7  987.81
#Mann=7,-1,0
  4665.2     0.1       0  4837.0    0.13       0  4993.0    0.05       0
  5007.0    0.13       0  5049.6    0.07       0  5163.6    0.13       0
  5228.8    0.07       0
Bank Sta=4993,5007
XS Rating Curve= 0
Exp/Cntr=0.3,0.1

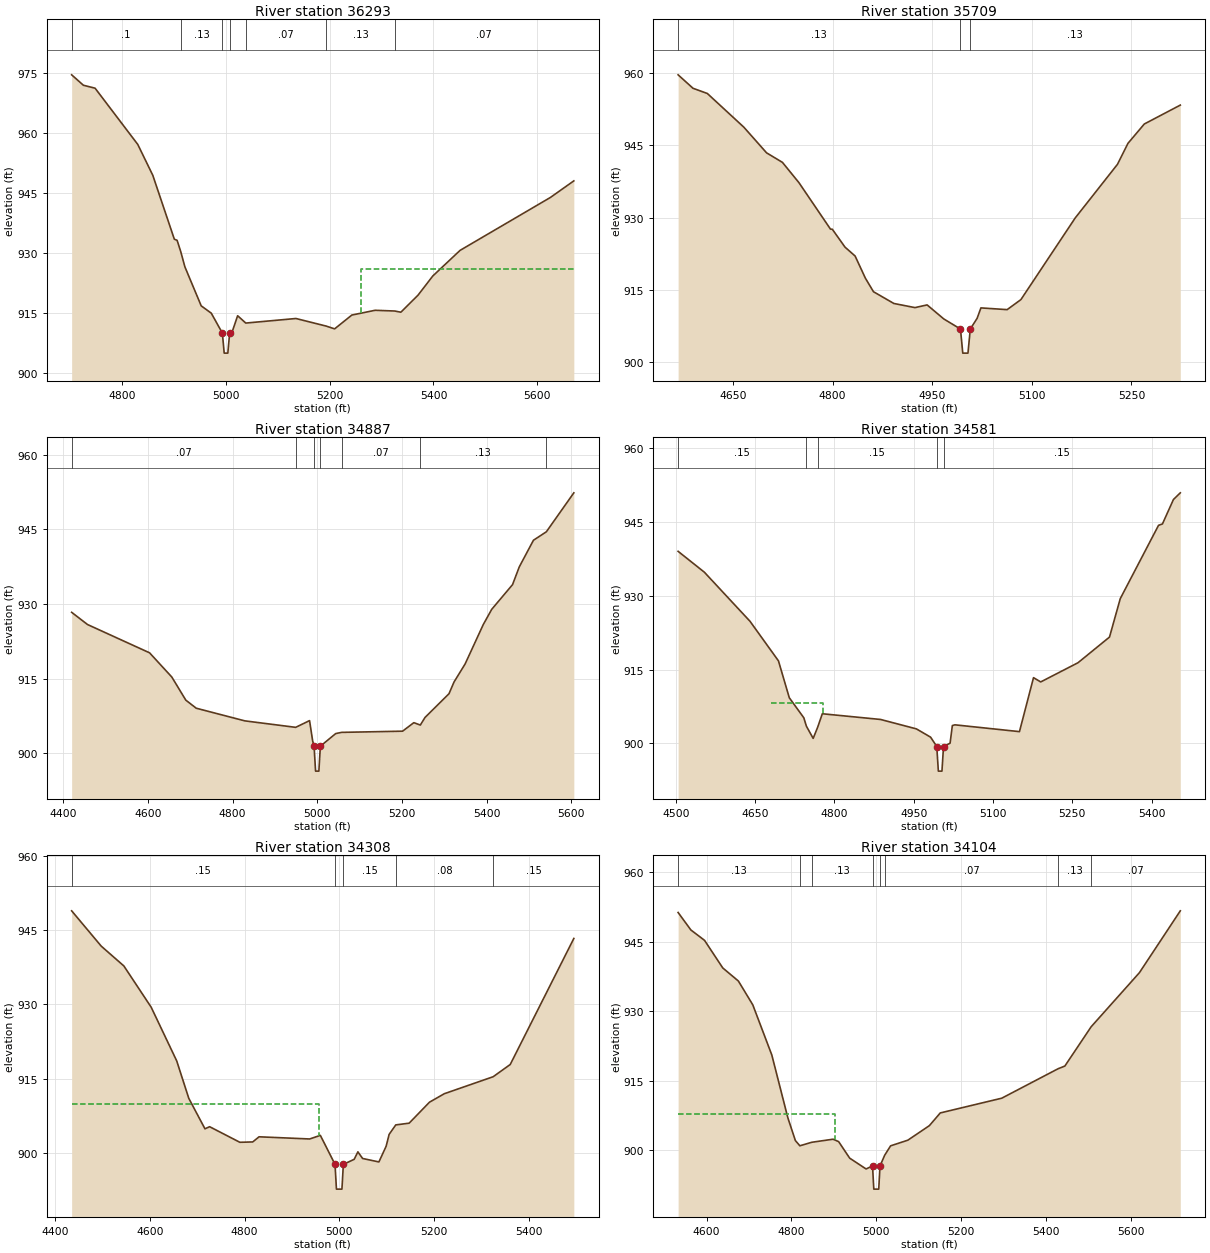
Type RM Length L Ch R = 1,36293,584,584,584
BEGIN DESCRIPTION:
Grassy Creek 65.0
END DESCRIPTION:
XS GIS Cut Line= 4
      1571862.45       938570.39      1571646.18       938672.68
      1571234.05       938859.74      1570962.20       938909.44
#Sta/Elev= 30
  4702.4  974.44  4725.0  971.84  4747.6  971.10  4829.9  957.05  4858.8  949.36
  4900.4  933.37  4905.7  933.11  4912.7  930.30  4920.7  926.48  4952.2  916.73
  4971.6  914.90  4993.0  909.92  4996.5  904.92  5003.5  904.92  5007.0  909.92
  5011.8  910.20  5022.4  914.26  5038.1  912.43  5134.8  913.57  5193.3  911.67
  5209.4  910.98  5242.6  914.43  5287.4  915.62  5325.3  915.44  5337.1  915.14
  5370.2  919.40  5398.7  924.19  5451.3  930.59  5625.6  943.82  5670.6  947.95
#Mann=7,-1,0
  4702.4     0.1       0  4912.7    0.13       0  4993.0    0.05       0
  5007.0    0.13       0  5038.1    0.07       0  5193.3    0.13       0
  5325.3    0.07       0
#XS Ineff=2,0
       0                 5260.00    0.00  926.01
Permanent Ineff=
       F       F
Bank Sta=4993,5007
XS Rating Curve= 0
Exp/Cntr=0.3,0.1

Type RM Length L Ch R = 1,35709,822,822,822
BEGIN DESCRIPTION:
Grassy Creek 64.0
END DESCRIPTION:
XS GIS Cut Line= 4
      1571958.92       938234.25      1571593.57       938152.41
      1571508.80       938137.79      1571213.64       938155.33
#Sta/Elev= 30
  4567.5  959.61  4589.9  956.82  4611.5  955.74  4666.4  948.76  4700.7  943.43
  4724.6  941.45  4749.4  937.25  4796.9  927.61  4799.7  927.58  4818.8  923.87
  4834.0  922.03  4849.4  917.45  4861.6  914.63  4892.3  912.19  4924.1  911.33
  4942.4  911.89  4967.5  908.98  4992.6  906.89  4996.1  901.89  5003.9  901.89
  5007.4  906.89  5017.7  909.11  5023.4  911.27  5062.9  910.91  5083.6  912.99
  5165.4  929.93  5229.0  941.05  5244.8  945.40  5269.4  949.41  5323.6  953.33
#Mann=3,-1,0
  4567.5    0.13       0  4992.6    0.05       0  5007.4    0.13       0
Bank Sta=4992.6,5007.4
XS Rating Curve= 0
Exp/Cntr=0.3,0.1

Type RM Length L Ch R = 1,34887,306,306,306
BEGIN DESCRIPTION:
Grassy Creek 63.0
END DESCRIPTION:
XS GIS Cut Line= 4
      1572070.01       937833.54      1571824.47       937383.40
      1571444.50       937310.33      1571158.02       937319.10
#Sta/Elev= 30
  4419.9  928.34  4457.4  925.89  4604.0  920.21  4656.5  915.35  4689.6  910.71
  4714.2  909.09  4829.0  906.55  4949.1  905.25  4981.9  906.60  4989.2  902.54
  4992.6  901.46  4996.1  896.46  5003.9  896.46  5007.4  901.46  5043.7  904.00
  5057.5  904.24  5201.7  904.48  5228.2  906.19  5243.6  905.71  5254.6  907.23
  5311.3  912.00  5323.1  914.34  5349.4  917.98  5392.3  925.89  5412.3  928.95
  5461.4  933.90  5477.3  937.46  5510.8  942.81  5541.3  944.51  5606.2  952.33
#Mann=7,-1,0
  4419.9    0.07       0  4949.1    0.13       0  4992.6    0.05       0
  5007.4    0.13       0  5057.5    0.07       0  5243.6    0.13       0
  5541.3    0.07       0
Bank Sta=4992.6,5007.4
XS Rating Curve= 0
Exp/Cntr=0.3,0.1

Type RM Length L Ch R = 1,34581,273,273,273
BEGIN DESCRIPTION:
Grass Creek 62.7
END DESCRIPTION:
XS GIS Cut Line= 4
      1572301.64       937199.40      1571965.76       937116.08
      1571596.05       937006.73      1571377.39       936998.92
#Sta/Elev= 30
  4504.1  939.01  4553.8  934.77  4640.2  924.80  4694.0  916.77  4714.5  909.28
  4742.0  905.21  4746.9  903.50  4759.7  901.03  4768.1  903.26  4777.0  906.03
  4887.3  904.87  4955.0  902.96  4981.9  901.28  4993.6  899.38  4996.6  894.38
  5003.4  894.38  5006.4  899.38  5018.8  900.05  5023.1  903.64  5028.0  903.78
  5150.1  902.40  5176.7  913.36  5190.3  912.49  5260.9  916.39  5320.5  921.60
  5340.9  929.41  5413.3  944.29  5420.7  944.57  5441.5  949.53  5454.5  950.89
#Mann=5,-1,0
  4504.1    0.15       0  4746.9   0.055       0  4768.1    0.15       0
  4993.6   0.055       0  5006.4    0.15       0
#XS Ineff=1,-1
 4680.00 4777.90  908.22
Permanent Ineff=
       F
Bank Sta=4993.6,5006.4
XS Rating Curve= 0
Exp/Cntr=0.3,0.1

Type RM Length L Ch R = 1,34308,204,204,204
BEGIN DESCRIPTION:
Grassy Creek 62.5
END DESCRIPTION:
XS GIS Cut Line= 5
      1572400.30       936837.99      1571999.85       936858.45
      1571888.78       936811.69      1571719.25       936829.22
      1571356.80       936899.38
#Sta/Elev= 30
  4434.7  948.89  4497.2  941.76  4545.0  937.76  4602.7  929.43  4656.7  918.58
  4682.2  911.02  4716.4  904.86  4726.2  905.29  4790.1  902.14  4817.3  902.21
  4830.7  903.25  4937.6  902.81  4960.2  903.54  4991.2  897.68  4994.2  892.68
  5005.8  892.68  5008.8  897.68  5031.7  898.70  5039.5  900.21  5049.5  898.87
  5083.9  898.17  5099.2  901.34  5105.5  903.73  5119.5  905.65  5147.8  906.00
  5190.8  910.24  5222.1  911.95  5325.3  915.38  5361.4  917.85  5495.8  943.31
#Mann=5,-1,0
  4434.7    0.15       0  4991.2   0.055       0  5008.8    0.15       0
  5119.5    0.08       0  5325.3    0.15       0
#XS Ineff=2,0
    0.00 4958.10  909.84               0
Permanent Ineff=
       F       F
Bank Sta=4991.2,5008.8
XS Rating Curve= 0
Exp/Cntr=0.3,0.1

Type RM Length L Ch R = 1,34104,583,583,583
BEGIN DESCRIPTION:
Grassy Creek 62.0
END DESCRIPTION:
XS GIS Cut Line= 4
      1572309.71       936639.23      1572137.22       936674.31
      1571763.09       936615.85      1571140.54       936706.46
#Sta/Elev= 30
  4532.9  951.29  4563.0  947.52  4595.2  945.28  4638.2  939.32  4675.0  936.50
  4708.9  931.37  4753.8  920.54  4791.5  907.02  4809.3  902.08  4819.9  900.95
  4847.9  901.71  4898.1  902.37  4911.3  901.85  4937.4  898.28  4976.0  895.95
  4991.2  896.60  4994.2  891.60  5005.8  891.60  5008.8  896.60  5020.0  898.94
  5033.8  900.94  5074.4  902.16  5125.1  905.29  5150.9  908.04  5295.8  911.22
  5428.5  917.57  5444.6  918.16  5506.6  926.64  5620.3  938.30  5716.7  951.65
#Mann=8,-1,0
  4532.9    0.13       0  4819.9    0.07       0  4847.9    0.13       0
  4991.2    0.05       0  5008.8    0.13       0  5020.0    0.07       0
  5428.5    0.13       0  5506.6    0.07       0
#XS Ineff=2,0
    0.00 4903.10  907.85               0
Permanent Ineff=
       F       F
Bank Sta=4991.2,5008.8
XS Rating Curve= 0
Exp/Cntr=0.3,0.1

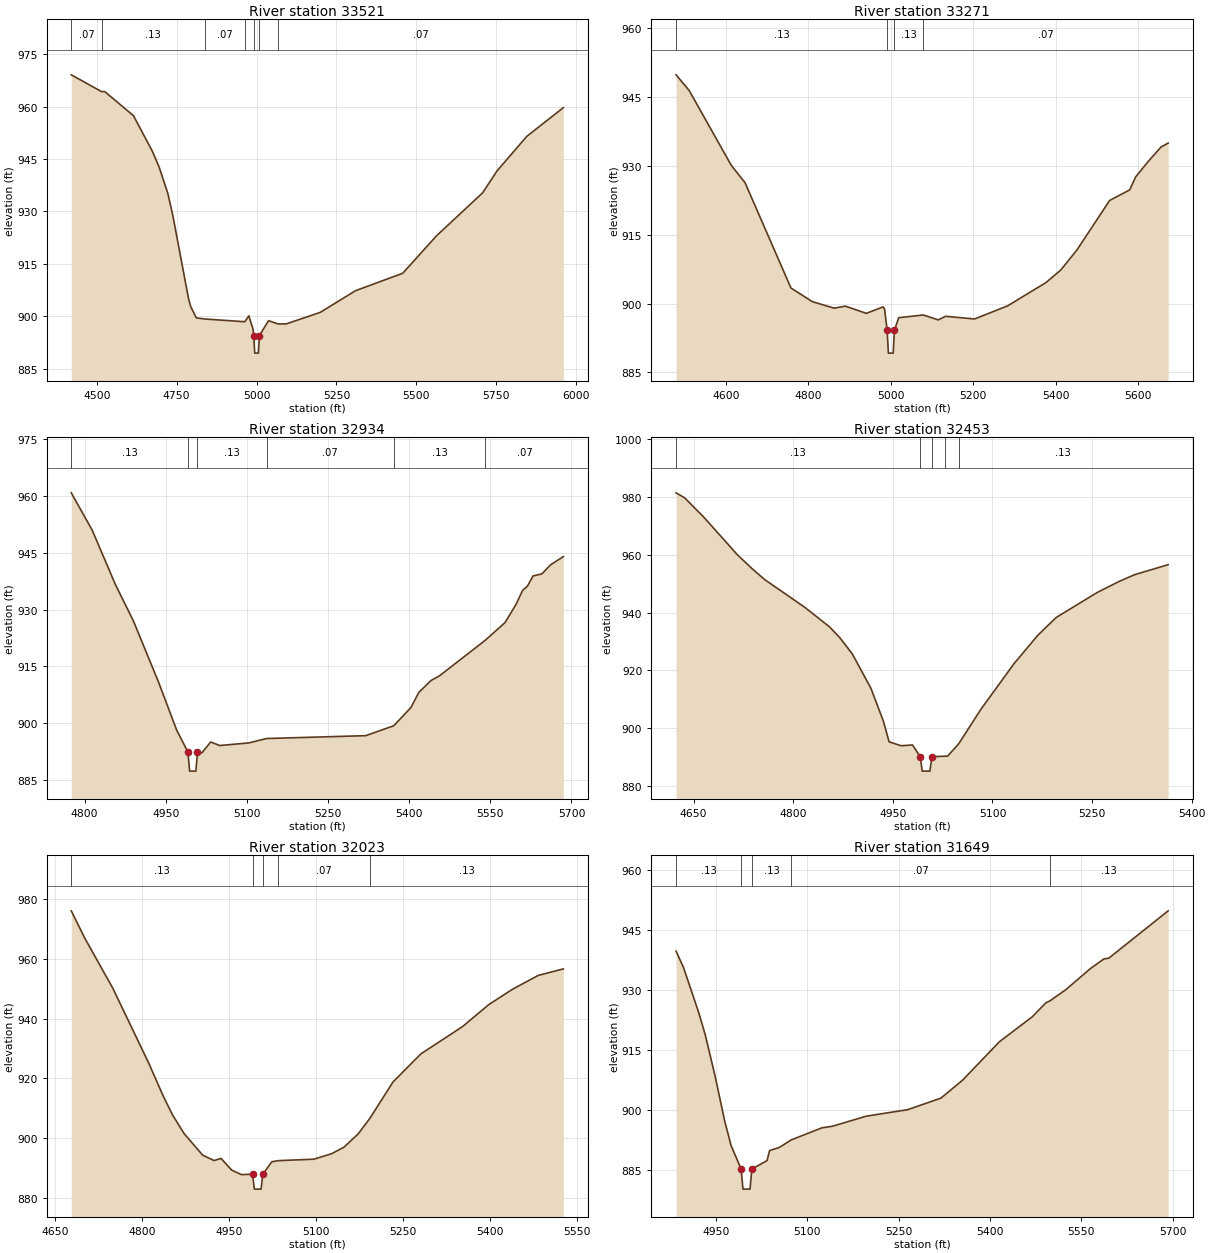
Type RM Length L Ch R = 1,33521,250,250,250
BEGIN DESCRIPTION:
Grassy Creek 61.0
END DESCRIPTION:
XS GIS Cut Line= 4
      1572395.24       936239.91      1572140.05       936106.52
      1571310.55       936286.34      1570939.35       936442.94
#Sta/Elev= 30
  4420.2  969.12  4515.0  964.32  4525.2  964.31  4614.8  957.42  4674.6  947.12
  4695.2  942.68  4722.3  935.18  4737.7  928.95  4787.4  904.91  4793.7  902.81
  4811.4  899.53  4837.8  899.21  4963.1  898.43  4975.8  900.11  4988.9  896.32
  4991.2  894.44  4994.2  889.44  5005.8  889.44  5008.8  894.44  5037.4  898.74
  5066.6  897.80  5092.8  897.81  5199.2  901.11  5309.9  907.33  5457.2  912.30
  5562.9  923.03  5707.3  935.34  5752.2  941.60  5845.7  951.53  5959.8  959.72
#Mann=7,-1,0
  4420.2    0.07       0  4515.0    0.13       0  4837.8    0.07       0
  4963.1    0.13       0  4991.2    0.05       0  5008.8    0.13       0
  5066.6    0.07       0
Bank Sta=4991.2,5008.8
XS Rating Curve= 0
Exp/Cntr=0.3,0.1

Type RM Length L Ch R = 1,33271,337,337,337
BEGIN DESCRIPTION:
Grassy Creek 60.5
END DESCRIPTION:
XS GIS Cut Line= 5
      1572239.49       936066.33      1572040.77       935890.98
      1571842.01       935899.75      1571555.57       936063.43
      1571196.07       936235.87
#Sta/Elev= 30
  4479.6  949.86  4511.2  946.47  4613.5  930.13  4646.7  926.37  4758.0  903.42
  4809.7  900.44  4862.8  899.02  4889.9  899.46  4940.7  897.89  4981.3  899.29
  4984.8  898.86  4991.2  894.22  4994.2  889.22  5005.8  889.22  5008.8  894.22
  5019.3  896.94  5078.8  897.53  5115.1  896.46  5132.8  897.25  5202.9  896.66
  5283.1  899.52  5375.7  904.57  5411.7  907.30  5451.5  911.74  5530.3  922.48
  5579.0  924.79  5593.2  927.58  5624.5  931.05  5654.9  934.13  5672.2  934.99
#Mann=4,-1,0
  4479.6    0.13       0  4991.2    0.05       0  5008.8    0.13       0
  5078.8    0.07       0
Bank Sta=4991.2,5008.8
XS Rating Curve= 0
Exp/Cntr=0.3,0.1

Type RM Length L Ch R = 1,32934,481,481,481
BEGIN DESCRIPTION:
Grassy Creek 60.0
END DESCRIPTION:
XS GIS Cut Line= 4
      1571733.86       935543.16      1571599.41       935657.15
      1571348.04       935882.21      1571035.28       936124.83
#Sta/Elev= 30
  4775.5  960.78  4814.1  950.96  4857.1  936.59  4890.3  927.02  4936.7  910.91
  4970.3  898.23  4991.2  892.40  4994.2  887.40  5005.8  887.40  5008.8  892.40
  5016.9  892.22  5033.2  895.08  5050.0  894.15  5104.1  894.85  5136.6  896.00
  5319.8  896.75  5371.6  899.37  5403.4  904.19  5417.8  908.15  5440.5  911.31
  5456.0  912.52  5541.0  921.94  5577.2  926.57  5597.6  931.38  5609.7  935.06
  5618.5  936.15  5629.0  938.87  5645.4  939.41  5661.4  941.80  5685.0  943.97
#Mann=6,-1,0
  4775.5    0.13       0  4991.2    0.05       0  5008.8    0.13       0
  5136.6    0.07       0  5371.6    0.13       0  5541.0    0.07       0
Bank Sta=4991.2,5008.8
XS Rating Curve= 0
Exp/Cntr=0.3,0.1

Type RM Length L Ch R = 1,32453,430,430,430
BEGIN DESCRIPTION:
Grassy Creek 59.0
END DESCRIPTION:
XS GIS Cut Line= 4
      1571501.94       935242.23      1571258.35       935340.83
      1571101.73       935532.25      1571003.10       935741.11
#Sta/Elev= 30
  4623.5  981.33  4636.3  979.63  4664.8  973.05  4715.9  959.93  4738.2  955.10
  4757.1  951.35  4817.1  941.84  4854.4  935.09  4869.7  931.43  4888.8  925.75
  4917.1  913.78  4935.7  902.49  4944.3  895.36  4962.1  894.00  4979.6  894.26
  4991.2  890.23  4994.2  885.23  5005.8  885.23  5008.8  890.23  5029.1  890.38
  5032.4  890.41  5048.9  894.59  5082.9  906.68  5132.4  922.32  5168.5  932.19
  5196.0  938.29  5257.6  946.90  5290.6  950.71  5314.2  953.08  5364.6  956.52
#Mann=5,-1,0
  4623.5    0.13       0  4991.2    0.05       0  5008.8    0.13       0
  5029.1    0.07       0  5048.9    0.13       0
Bank Sta=4991.2,5008.8
XS Rating Curve= 0
Exp/Cntr=0.3,0.1

Type RM Length L Ch R = 1,32023,374,374,374
BEGIN DESCRIPTION:
Grassy Creek 58.0
END DESCRIPTION:
XS GIS Cut Line= 3
      1570979.94       934963.74      1570678.28       935456.84
      1570817.47       935688.83
#Sta/Elev= 30
  4678.5  976.20  4701.8  967.03  4750.1  950.26  4812.2  925.07  4837.4  913.94
  4853.2  907.72  4872.9  901.53  4905.1  894.25  4924.9  892.43  4936.7  893.17
  4955.1  889.24  4971.9  887.72  4991.2  887.85  4994.2  882.85  5005.8  882.85
  5008.8  887.85  5024.3  892.02  5035.5  892.40  5096.8  892.89  5127.5  894.73
  5148.5  896.89  5173.0  901.32  5193.3  906.54  5233.4  918.81  5281.5  928.23
  5353.3  937.38  5398.6  944.76  5439.7  949.93  5484.0  954.55  5527.1  956.72
#Mann=5,-1,0
  4678.5    0.13       0  4991.2    0.05       0  5008.8    0.13       0
  5035.5    0.07       0  5193.3    0.13       0
Bank Sta=4991.2,5008.8
XS Rating Curve= 0
Exp/Cntr=0.3,0.1

Type RM Length L Ch R = 1,31649,414,414,414
BEGIN DESCRIPTION:
Grassy Creek 57.5
END DESCRIPTION:
XS GIS Cut Line= 4
      1570515.02       934911.79      1570550.10       935291.79
      1570585.17       935499.32      1570754.74       935633.80
#Sta/Elev= 30
  4884.3  939.68  4896.5  935.59  4921.5  924.34  4932.5  918.64  4948.6  908.35
  4964.2  897.24  4974.8  891.09  4991.2  885.26  4994.2  880.26  5005.8  880.26
  5008.8  885.26  5033.8  887.39  5038.0  889.89  5054.2  890.68  5073.3  892.54
  5124.1  895.57  5141.0  895.95  5196.7  898.47  5264.7  900.09  5319.5  902.98
  5355.0  907.46  5415.6  917.06  5469.4  923.27  5491.9  926.78  5498.3  927.25
  5524.3  930.01  5565.3  935.35  5587.1  937.71  5595.4  937.93  5692.8  949.74
#Mann=5,-1,0
  4884.3    0.13       0  4991.2    0.05       0  5008.8    0.13       0
  5073.3    0.07       0  5498.3    0.13       0
Bank Sta=4991.2,5008.8
XS Rating Curve= 0
Exp/Cntr=0.3,0.1

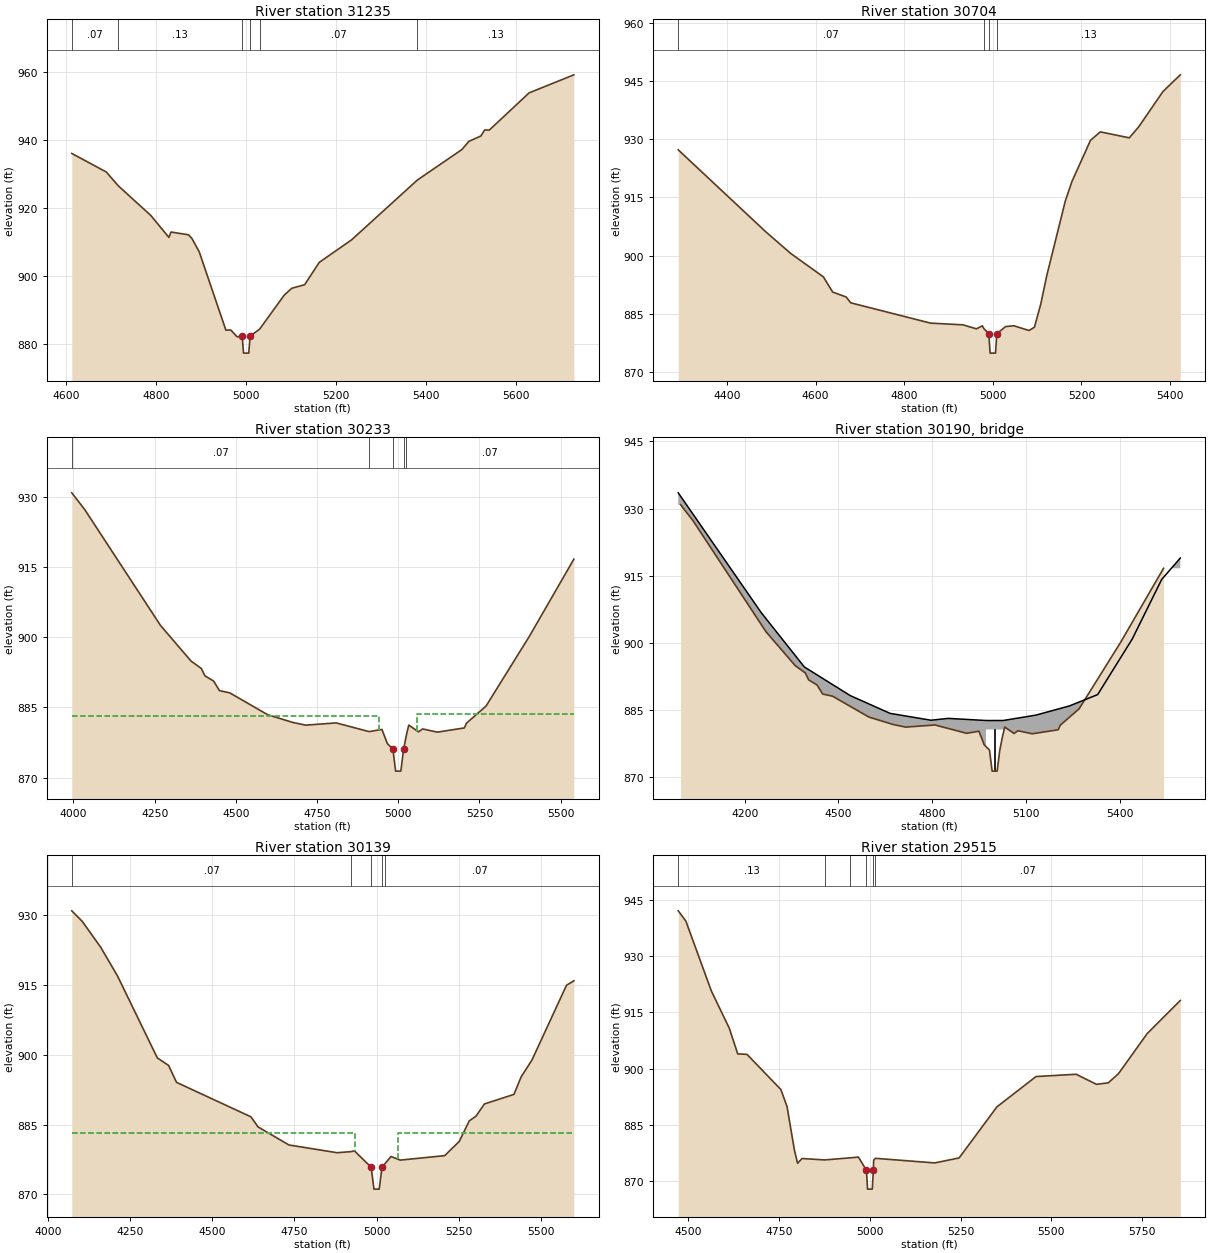
Type RM Length L Ch R = 1,31235,531,531,531
BEGIN DESCRIPTION:
Grassy Creek 57.0
END DESCRIPTION:
XS GIS Cut Line= 4
      1570341.84       935015.99      1570185.22       935242.21
      1570475.25       935532.25      1570863.88       935717.86
#Sta/Elev= 30
  4612.4  935.92  4689.0  930.48  4715.7  926.41  4788.0  917.70  4828.3  911.23
  4832.9  912.81  4871.9  912.00  4879.6  910.89  4895.7  907.00  4955.0  883.96
  4965.9  884.01  4980.0  882.00  4991.2  882.21  4994.2  877.21  5005.8  877.21
  5008.8  882.21  5030.0  884.27  5084.8  894.29  5101.4  896.28  5130.0  897.32
  5162.5  903.89  5234.4  910.52  5380.6  928.10  5479.4  937.05  5495.1  939.47
  5521.7  941.04  5530.2  942.83  5540.4  942.78  5629.0  953.73  5728.4  959.03
#Mann=6,-1,0
  4612.4    0.07       0  4715.7    0.13       0  4991.2    0.05       0
  5008.8    0.13       0  5030.0    0.07       0  5380.6    0.13       0
Bank Sta=4991.2,5008.8
XS Rating Curve= 0
Exp/Cntr=0.3,0.1

Type RM Length L Ch R = 1,30704,471,471,471
BEGIN DESCRIPTION:
Grassy Creek 56.0
END DESCRIPTION:
XS GIS Cut Line= 4
      1570278.93       935091.94      1569897.97       935490.48
      1569862.24       935902.68      1569731.19       936008.16
#Sta/Elev= 30
  4289.9  927.23  4487.6  906.13  4543.8  900.57  4617.5  894.54  4638.5  890.63
  4669.1  889.35  4679.3  887.86  4859.4  882.63  4932.7  882.19  4963.0  881.16
  4976.4  881.94  4979.8  881.21  4990.9  879.91  4993.9  874.91  5006.1  874.91
  5009.1  879.91  5028.9  881.75  5047.6  881.95  5081.6  880.73  5093.9  881.57
  5108.2  887.52  5121.7  894.83  5163.7  914.10  5178.4  919.03  5220.5  929.69
  5242.6  931.86  5308.1  930.32  5329.4  933.17  5383.9  942.22  5423.2  946.54
#Mann=4,-1,0
  4289.9    0.07       0  4979.8    0.13       0  4990.9    0.05       0
  5009.1    0.13       0
Bank Sta=4990.9,5009.1
XS Rating Curve= 0
Exp/Cntr=0.5,0.3

Type RM Length L Ch R = 1,30233,94,94,94
BEGIN DESCRIPTION:
Mt Zion Rd (GC) us
END DESCRIPTION:
XS GIS Cut Line= 6
      1570298.64       935055.37      1569812.69       935538.52
      1569635.73       935572.22      1569208.79       935473.91
      1569107.67       935490.76      1569012.18       935589.06
#Sta/Elev= 30
  3994.9  930.85  4034.3  927.33  4267.9  902.54  4362.0  894.92  4393.9  893.32
  4404.9  891.75  4431.6  890.64  4449.6  888.60  4481.3  888.12  4597.7  883.46
  4676.4  881.78  4715.3  881.22  4809.1  881.70  4910.3  879.84  4949.8  880.31
  4966.5  877.29  4983.5  876.10  4992.0  871.40  5008.0  871.40  5016.5  876.10
  5024.9  879.03  5032.4  881.24  5062.1  879.80  5074.9  880.41  5120.4  879.73
  5203.6  880.63  5210.1  881.65  5270.2  885.29  5403.6  900.19  5540.6  916.67
#Mann=5,-1,0
  3994.9    0.07       0  4910.3    0.13       0  4983.5    0.05       0
  5016.5    0.13       0  5024.9    0.07       0
#XS Ineff=2,0
    0.00 4942.00  883.17 5058.00    0.00  883.57
Permanent Ineff=
       F       F
Bank Sta=4983.5,5016.5
XS Rating Curve= 0
Exp/Cntr=0.5,0.3

Type RM Length L Ch R =3,30190,,,
BEGIN DESCRIPTION:
Mt Zion Rd (GC) TOR
Structure ID: LDS_GC_05
Approximate Survey Structure
END DESCRIPTION:
Bridge Culvert--1,0,-1,-1,0
Deck Dist Width WeirC Skew NumUp NumDn MinLoCord MaxHiCord MaxSubmerge Is_Ogee
30.5,25,3,,17,17,,,0.95,0,1,1,,,
  3987.4  4252.2  4390.8  4538.3  4665.5  4796.3  4851.2  4972.5  4972.5  5027.5
  5027.5  5131.9  5239.4  5329.7  5440.6  5534.6  5594.2
  933.51  906.85  894.66  888.24  884.29  882.76  883.17  882.70  882.70  882.70
  882.70  883.90  885.95  888.48  900.91  914.18  918.96
  851.40  851.40  851.40  851.40  851.40  851.40  851.40  851.40  880.70  880.70
  851.40  851.40  851.40  851.40  851.40  851.40  851.40
  3987.4  4252.2  4390.8  4538.3  4665.5  4796.3  4851.2  4972.5  4972.5  5027.5
  5027.5  5131.9  5239.4  5329.7  5440.6  5534.6  5594.2
  933.51  906.85  894.66  888.24  884.29  882.76  883.17  882.70  882.70  882.70
  882.70  883.90  885.95  888.48  900.91  914.18  918.96
  851.40  851.40  851.40  851.40  851.40  851.40  851.40  851.40  880.70  880.70
  851.40  851.40  851.40  851.40  851.40  851.40  851.40
Pier Skew, UpSta & Num, DnSta & Num=,5000,2,5000,2,0,0,0,0,0
       2       2
  871.40  880.70
       2       2
  871.15  880.70
BR Coef=1,1,0,1.25,0,,,0.8,0,2,0,
WSPro=,,,, 1 ,,,, 0 ,,,, 0 ,,,,-1 ,-1 ,-1 , 0 , 0 , 0 , 0 , 0
BC Design=,,0,,0,,,,,,

Type RM Length L Ch R = 1,30139,624,624,624
BEGIN DESCRIPTION:
Mt Zion Rd (GC) ds
END DESCRIPTION:
XS GIS Cut Line= 6
      1570250.89       935041.33      1569809.88       935457.06
      1569680.68       935487.96      1569203.17       935384.03
      1569065.53       935420.54      1568986.89       935555.36
#Sta/Elev= 30
  4072.5  930.92  4104.5  928.65  4160.8  923.07  4211.7  916.93  4332.8  899.34
  4367.1  897.72  4391.3  894.08  4617.9  886.67  4639.3  884.52  4733.5  880.63
  4880.0  878.97  4923.0  879.21  4932.8  879.36  4983.5  875.85  4992.0  871.15
  5008.0  871.15  5016.5  875.85  5026.0  876.65  5043.9  878.16  5072.2  877.38
  5207.2  878.34  5251.6  881.39  5282.1  885.81  5302.6  886.82  5328.2  889.44
  5418.1  891.50  5439.9  895.25  5472.9  898.89  5577.9  914.92  5600.3  915.90
#Mann=5,-1,0
  4072.5    0.07       0  4923.0    0.13       0  4983.5    0.05       0
  5016.5    0.13       0  5026.0    0.07       0
#XS Ineff=2,0
    0.00 4934.00  883.30 5066.00    0.00  883.26
Permanent Ineff=
       F       F
Bank Sta=4983.5,5016.5
XS Rating Curve= 0
Exp/Cntr=0.5,0.3

Type RM Length L Ch R = 1,29515,437,437,437
BEGIN DESCRIPTION:
Grassy Creek 55.0
END DESCRIPTION:
XS GIS Cut Line= 5
      1569860.39       934662.13      1569616.75       934853.57
      1569100.49       935126.20      1568972.87       935364.03
      1568970.03       935583.42
#Sta/Elev= 30
  4472.0  942.12  4492.9  939.41  4563.3  920.70  4612.5  910.80  4635.9  903.91
  4661.5  903.78  4754.7  894.39  4771.7  889.85  4792.0  878.24  4800.8  874.69
  4813.1  875.97  4875.4  875.59  4945.7  876.15  4968.4  876.35  4990.5  872.79
  4993.5  867.79  5006.5  867.79  5009.5  872.79  5010.3  875.49  5015.0  876.02
  5178.5  874.79  5245.7  876.12  5349.9  889.77  5457.6  897.86  5568.3  898.47
  5624.0  895.78  5656.5  896.18  5684.6  898.61  5763.6  909.31  5855.0  918.18
#Mann=6,-1,0
  4472.0    0.13       0  4875.4    0.07       0  4945.7    0.13       0
  4990.5    0.05       0  5009.5    0.13       0  5015.0    0.07       0
Bank Sta=4990.5,5009.5
XS Rating Curve= 0
Exp/Cntr=0.3,0.1