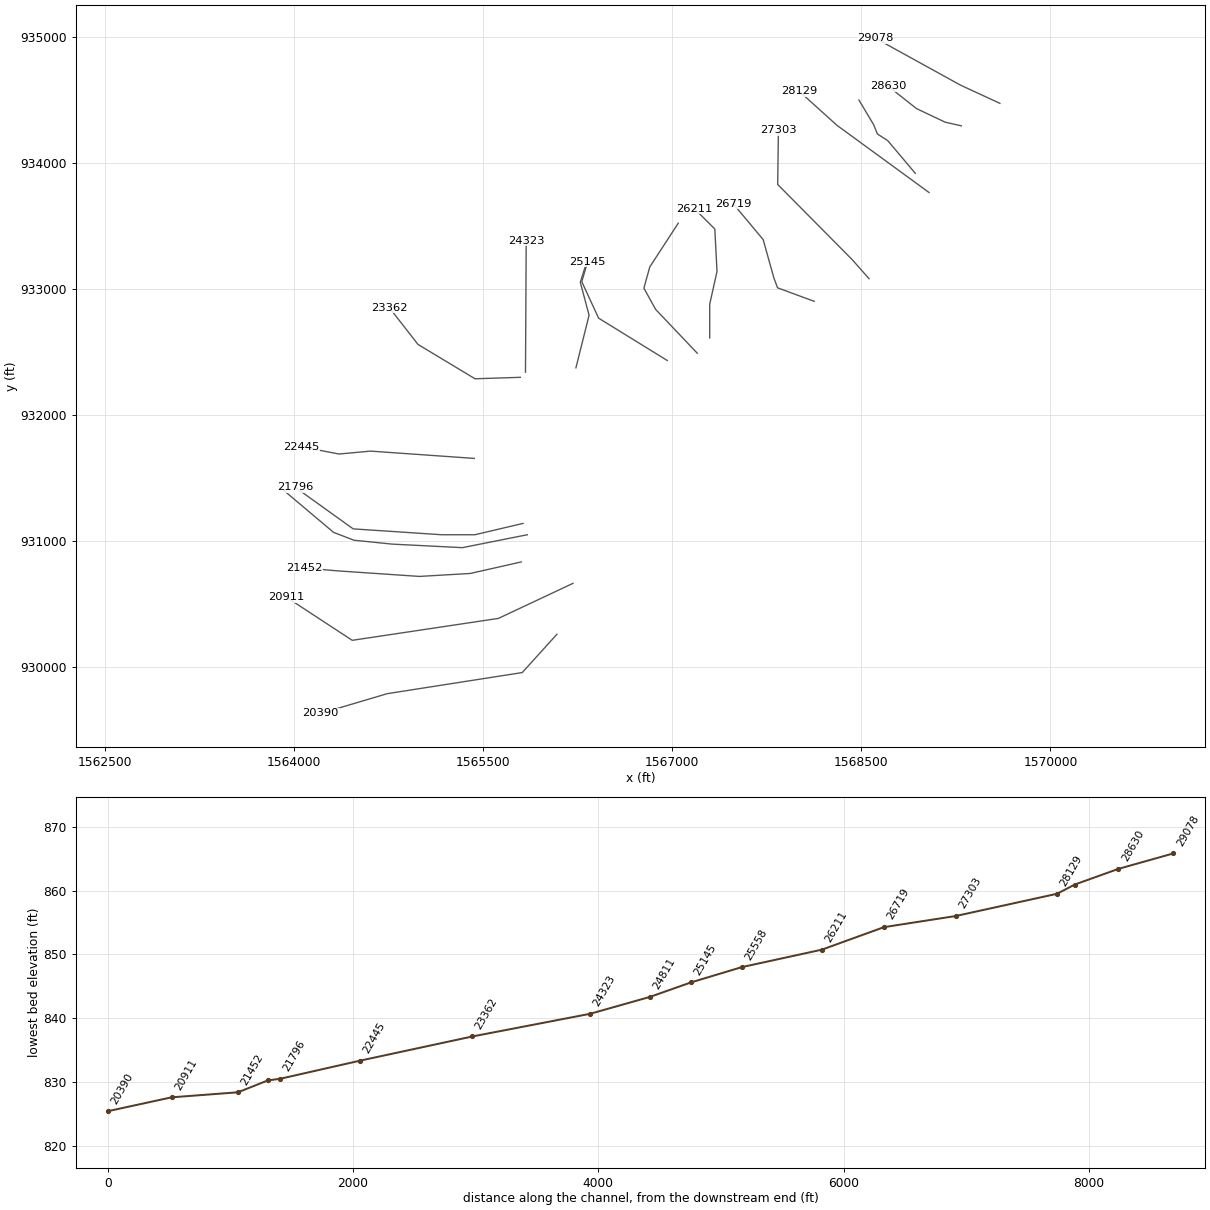
HEC-RAS study Grassy Creek.prj: Grassy Creek Limited Detail Study

--- Grassy Creek.g01 (geometry) --- (continued)

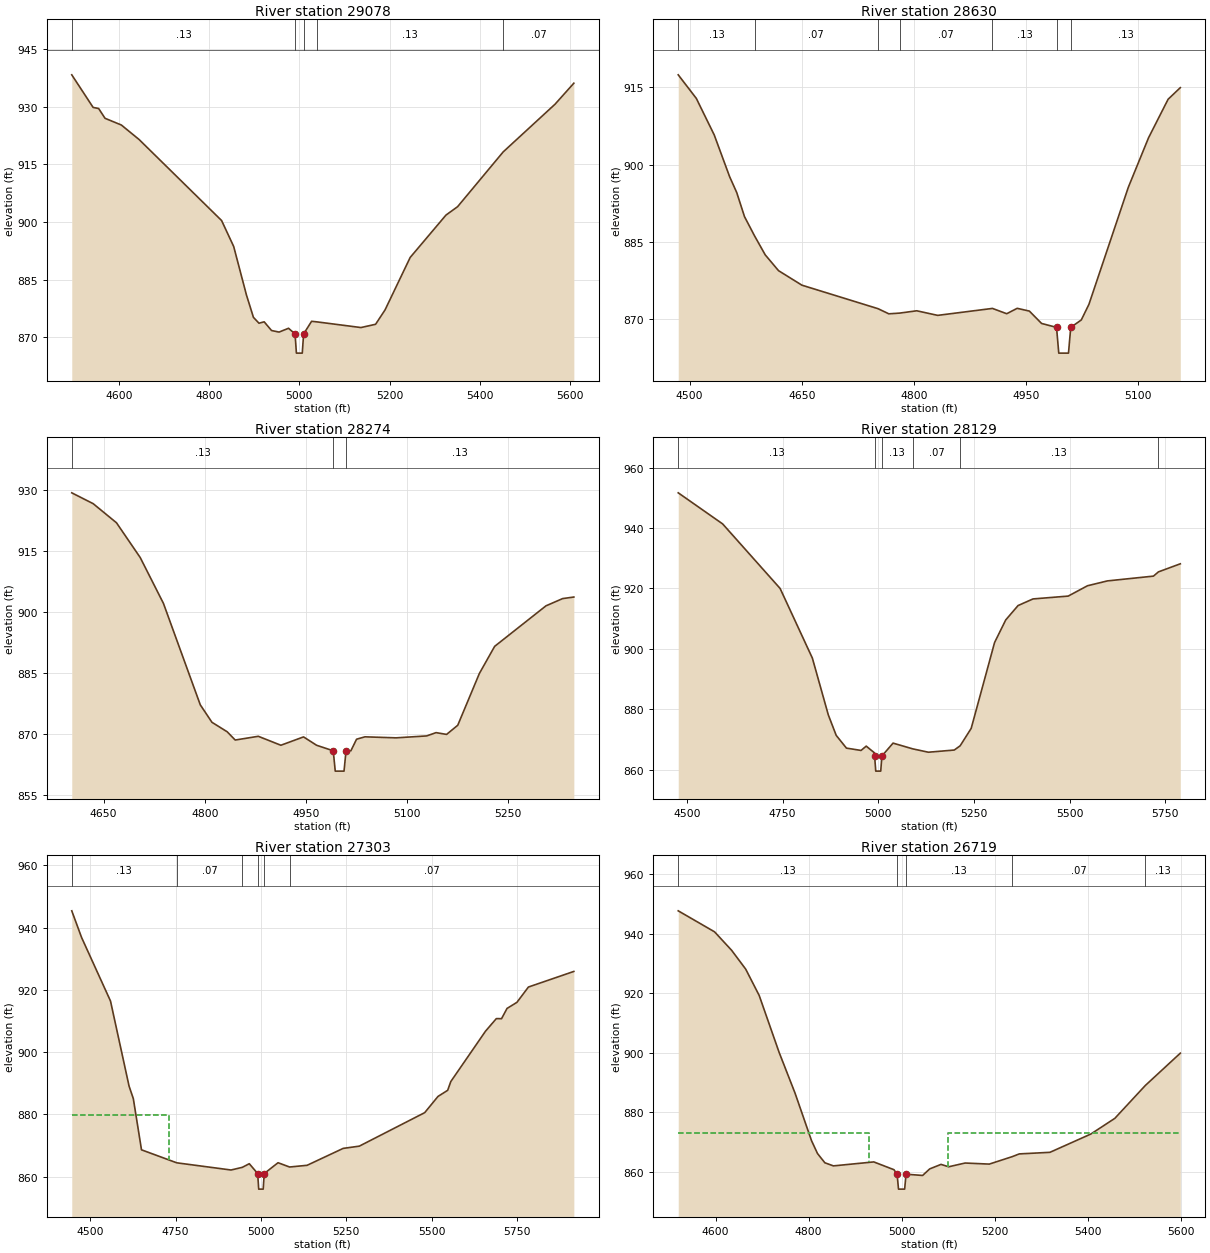
Type RM Length L Ch R = 1,29078,448,448,448
BEGIN DESCRIPTION:
Grassy Creek 54.0
END DESCRIPTION:
XS GIS Cut Line= 3
      1569599.32       934476.53      1569286.11       934621.54
      1568613.19       934992.81
#Sta/Elev= 30
  4495.2  938.31  4542.6  929.82  4554.8  929.54  4569.0  926.99  4605.2  925.24
  4644.5  921.47  4827.6  900.36  4854.4  893.60  4882.7  880.97  4898.2  875.15
  4910.5  873.63  4922.0  873.99  4938.3  871.73  4955.0  871.32  4976.0  872.31
  4990.5  870.84  4993.5  865.84  5006.5  865.84  5009.5  870.84  5027.2  874.13
  5038.8  873.98  5136.7  872.50  5169.1  873.35  5190.1  877.09  5245.9  890.76
  5325.3  901.79  5351.0  903.97  5452.2  918.24  5567.3  930.67  5608.9  936.13
#Mann=5,-1,0
  4495.2    0.13       0  4990.5    0.05       0  5009.5    0.13       0
  5038.8    0.13       0  5452.2    0.07       0
Bank Sta=4990.5,5009.5
XS Rating Curve= 0
Exp/Cntr=0.3,0.1

Type RM Length L Ch R = 1,28630,356,356,356
BEGIN DESCRIPTION:
Grassy Creek 53.7
END DESCRIPTION:
XS GIS Cut Line= 4
      1569293.25       934298.02      1569164.66       934327.24
      1568936.67       934435.39      1568711.64       934613.66
#Sta/Elev= 30
  4484.7  917.45  4508.9  912.87  4532.8  905.79  4553.4  897.68  4562.9  894.60
  4573.3  889.92  4586.8  886.17  4601.0  882.50  4618.8  879.43  4650.1  876.61
  4751.8  872.05  4766.3  871.05  4780.7  871.19  4803.6  871.64  4831.6  870.75
  4904.8  872.10  4923.9  871.07  4937.9  872.12  4954.2  871.58  4970.5  869.18
  4990.5  868.42  4993.5  863.42  5006.5  863.42  5009.5  868.42  5023.6  869.86
  5033.8  872.88  5086.5  895.62  5113.6  905.25  5139.7  912.71  5156.0  914.96
#Mann=7,-1,0
  4484.7    0.13       0  4586.8    0.07       0  4751.8    0.13       0
  4780.7    0.07       0  4904.8    0.13       0  4990.5    0.05       0
  5009.5    0.13       0
Bank Sta=4990.5,5009.5
XS Rating Curve= 0
Exp/Cntr=0.3,0.1

Type RM Length L Ch R = 1,28274,145,145,145
BEGIN DESCRIPTION:
Grassy Creek 53.5
END DESCRIPTION:
XS GIS Cut Line= 6
      1568927.91       933920.96      1568772.99       934105.10
      1568708.69       934181.10      1568626.85       934233.71
      1568597.62       934306.78      1568480.69       934502.64
#Sta/Elev= 30
  4602.9  929.35  4634.6  926.69  4669.2  921.99  4704.4  913.44  4738.8  902.18
  4793.4  877.26  4810.7  872.96  4833.3  870.63  4845.2  868.60  4879.4  869.52
  4912.9  867.32  4946.5  869.37  4965.9  867.31  4990.5  865.96  4993.5  860.96
  5006.5  860.96  5009.5  865.96  5016.6  865.94  5025.1  868.80  5037.5  869.39
  5083.6  869.14  5129.0  869.61  5143.0  870.42  5158.5  869.98  5175.1  872.23
  5207.2  884.97  5229.8  891.62  5305.9  901.58  5330.6  903.36  5347.2  903.74
#Mann=3,-1,0
  4602.9    0.13       0  4990.5    0.05       0  5009.5    0.13       0
Bank Sta=4990.5,5009.5
XS Rating Curve= 0
Exp/Cntr=0.3,0.1

Type RM Length L Ch R = 1,28129,826,826,826
BEGIN DESCRIPTION:
Grassy Creek 53.0
END DESCRIPTION:
XS GIS Cut Line= 3
      1569036.68       933768.84      1568305.79       934302.50
      1568004.13       934575.15
#Sta/Elev= 30
  4477.5  951.65  4593.6  941.35  4743.7  919.98  4827.9  896.93  4869.6  878.11
  4890.2  871.34  4916.9  867.13  4955.1  866.36  4968.6  867.79  4990.3  865.53
  4990.5  864.51  4993.5  859.51  5006.5  859.51  5009.5  864.51  5038.7  868.78
  5090.2  866.88  5130.9  865.77  5198.6  866.49  5214.0  867.90  5242.8  873.66
  5303.9  902.09  5333.0  909.56  5365.3  914.33  5404.3  916.52  5496.2  917.46
  5546.6  920.88  5598.7  922.49  5718.9  924.07  5732.0  925.48  5789.1  928.15
#Mann=6,-1,0
  4477.5    0.13       0  4990.5    0.05       0  5009.5    0.13       0
  5090.2    0.07       0  5214.0    0.13       0  5732.0    0.07       0
Bank Sta=4990.5,5009.5
XS Rating Curve= 0
Exp/Cntr=0.3,0.1

Type RM Length L Ch R = 1,27303,584,584,584
BEGIN DESCRIPTION:
Grassy Creek 52.0
END DESCRIPTION:
XS GIS Cut Line= 4
      1568561.05       933084.32      1568427.60       933235.17
      1567835.93       933832.64      1567841.73       934261.93
#Sta/Elev= 30
  4445.5  945.38  4474.3  936.81  4559.0  916.43  4613.5  889.07  4625.9  885.09
  4649.9  868.64  4753.2  864.47  4912.3  862.16  4945.5  863.02  4965.8  864.18
  4990.4  861.02  4993.4  856.02  5006.6  856.02  5009.6  861.02  5050.1  864.50
  5083.9  863.12  5135.3  863.67  5241.0  869.10  5288.3  869.82  5480.0  880.58
  5518.9  885.78  5547.3  887.75  5556.4  890.55  5658.1  906.72  5689.9  910.77
  5705.2  910.75  5721.3  914.04  5750.2  915.99  5784.0  920.91  5917.1  925.92
#Mann=6,-1,0
  4445.5    0.13       0  4753.2    0.07       0  4945.5    0.13       0
  4990.4    0.05       0  5009.6    0.13       0  5083.9    0.07       0
#XS Ineff=2,0
    0.00 4731.90  879.93               0
Permanent Ineff=
       F       F
Bank Sta=4990.4,5009.6
XS Rating Curve= 0
Exp/Cntr=0.3,0.1

Type RM Length L Ch R = 1,26719,508,508,508
BEGIN DESCRIPTION:
Grassy Creek 51.0
END DESCRIPTION:
XS GIS Cut Line= 5
      1568125.99       932904.52      1567834.75       933011.95
      1567805.52       933090.87      1567720.76       933394.85
      1567484.02       933678.35
#Sta/Elev= 30
  4519.8  947.68  4597.9  940.63  4634.5  934.45  4664.8  928.13  4693.8  919.30
  4736.7  900.18  4770.9  886.52  4806.4  870.54  4819.2  866.24  4835.0  863.13
  4853.4  862.08  4940.3  863.41  4983.6  860.80  4990.4  859.28  4993.4  854.28
  5006.6  854.28  5009.6  859.28  5045.3  858.87  5060.5  861.07  5084.8  862.58
  5101.2  861.78  5136.7  863.04  5188.5  862.68  5237.9  865.18  5253.1  866.10
  5319.0  866.63  5407.1  872.78  5458.5  878.03  5524.1  889.07  5599.3  899.91
#Mann=5,-1,0
  4519.8    0.13       0  4990.4    0.05       0  5009.6    0.13       0
  5237.9    0.07       0  5524.1    0.13       0
#XS Ineff=2,0
    0.00 4930.20  873.08 5099.60    0.00  873.08
Permanent Ineff=
       F       F
Bank Sta=4990.4,5009.6
XS Rating Curve= 0
Exp/Cntr=0.3,0.1

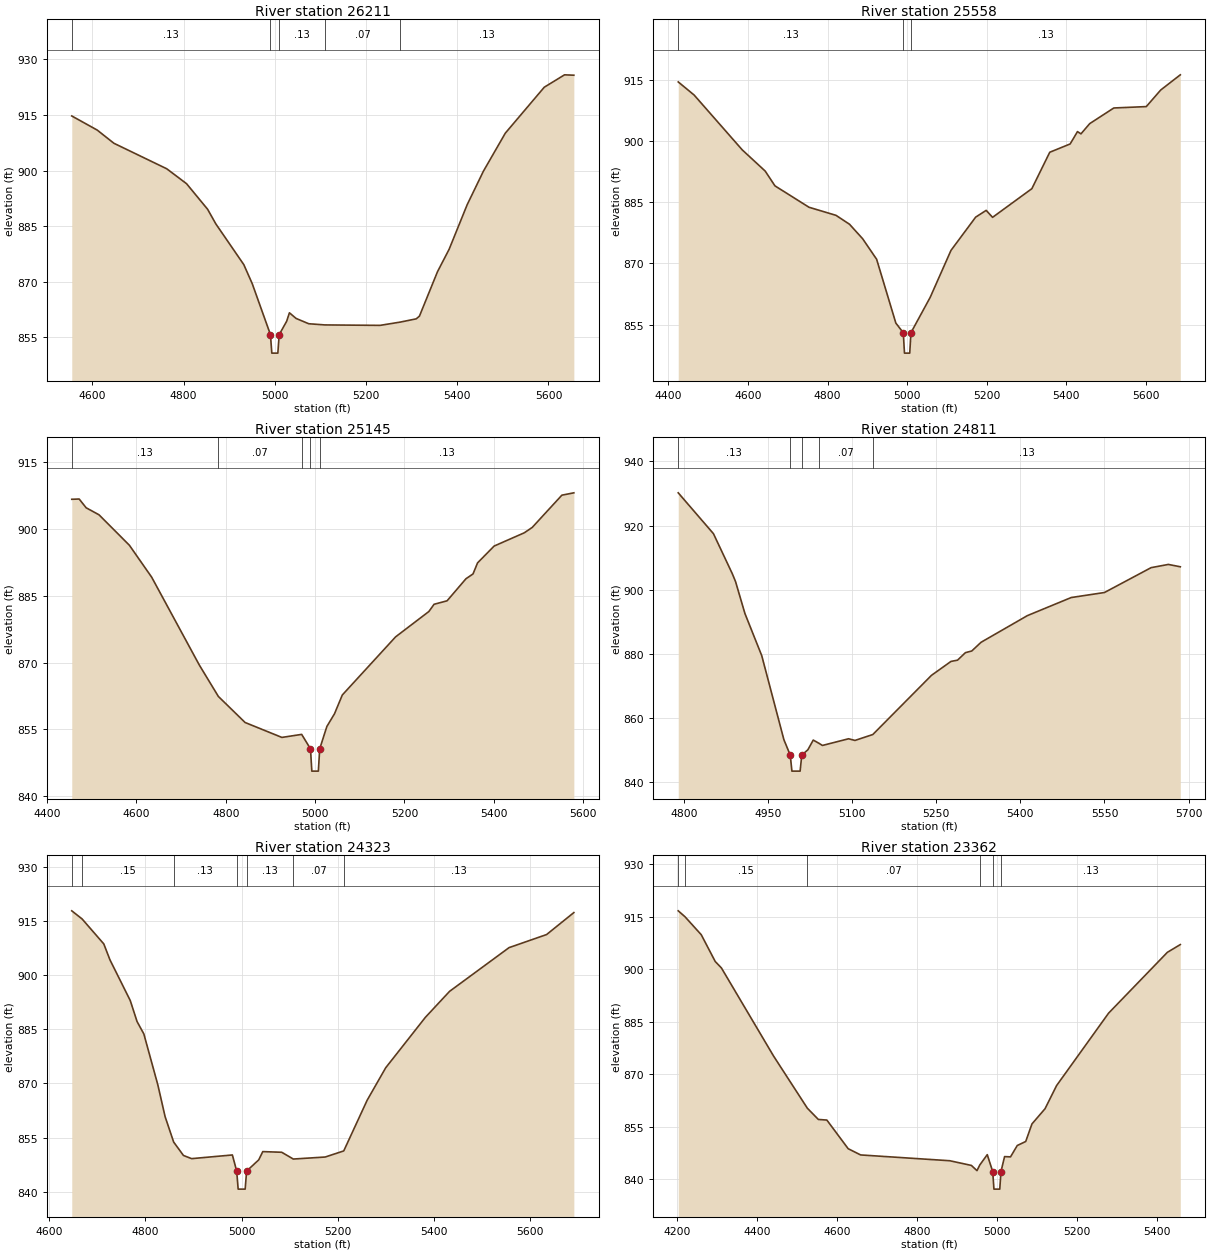
Type RM Length L Ch R = 1,26211,653,653,653
BEGIN DESCRIPTION:
Grassy Creek 50.0
END DESCRIPTION:
XS GIS Cut Line= 5
      1567296.47       932614.47      1567296.47       932881.33
      1567354.47       933142.36      1567337.07       933478.80
      1567174.68       933641.19
#Sta/Elev= 30
  4554.8  914.74  4610.6  910.93  4647.2  907.37  4763.0  900.49  4806.4  896.47
  4852.7  889.55  4870.7  885.61  4932.0  874.62  4950.4  869.51  4990.4  855.74
  4993.4  850.74  5006.6  850.74  5009.6  855.74  5026.0  859.35  5032.0  861.63
  5046.5  860.11  5074.3  858.67  5109.6  858.35  5230.8  858.23  5275.3  859.12
  5310.0  859.99  5317.1  860.73  5356.7  872.72  5382.1  878.75  5421.7  890.78
  5457.3  899.83  5505.3  910.09  5590.7  922.49  5635.2  925.84  5655.6  925.74
#Mann=5,-1,0
  4554.8    0.13       0  4990.4    0.05       0  5009.6    0.13       0
  5109.6    0.07       0  5275.3    0.13       0
Bank Sta=4990.4,5009.6
XS Rating Curve= 0
Exp/Cntr=0.3,0.1

Type RM Length L Ch R = 1,25558,413,413,413
BEGIN DESCRIPTION:
Grassy Creek 49.0
END DESCRIPTION:
XS GIS Cut Line= 5
      1567197.88       932492.66      1566867.22       932840.72
      1566774.40       933008.94      1566820.81       933177.16
      1567047.03       933525.19
#Sta/Elev= 30
  4424.8  914.51  4464.8  911.29  4585.7  897.84  4643.3  892.65  4667.9  889.02
  4753.5  883.77  4821.3  881.79  4855.2  879.61  4888.3  876.05  4923.4  871.02
  4971.7  855.37  4990.4  853.00  4993.4  848.00  5006.6  848.00  5009.6  853.00
  5058.0  861.68  5110.3  873.20  5172.3  881.35  5198.7  883.01  5214.8  881.30
  5313.5  888.33  5358.5  897.26  5409.8  899.30  5428.2  902.33  5436.9  901.77
  5458.9  904.28  5519.5  908.12  5601.1  908.46  5637.4  912.53  5686.6  916.25
#Mann=3,-1,0
  4424.8    0.13       0  4990.4    0.05       0  5009.6    0.13       0
Bank Sta=4990.4,5009.6
XS Rating Curve= 0
Exp/Cntr=0.3,0.1

Type RM Length L Ch R = 1,25145,334,334,334
BEGIN DESCRIPTION:
Grassy Creek 48.0
END DESCRIPTION:
XS GIS Cut Line= 4
      1566960.03       932434.67      1566414.76       932771.12
      1566281.35       933061.15      1566327.75       933217.75
#Sta/Elev= 30
  4455.6  906.66  4472.2  906.72  4487.8  904.75  4516.5  903.18  4584.5  896.34
  4634.4  889.16  4741.0  869.43  4783.6  862.38  4843.4  856.53  4925.7  853.18
  4970.0  853.86  4989.7  850.61  4992.7  845.61  5007.3  845.61  5010.3  850.61
  5026.3  855.63  5043.4  858.49  5060.9  862.71  5180.1  875.76  5254.6  881.46
  5266.2  883.08  5295.3  883.86  5337.6  888.82  5353.3  889.89  5363.5  892.38
  5400.6  896.16  5468.0  899.13  5485.8  900.34  5552.1  907.58  5578.9  908.11
#Mann=5,-1,0
  4455.6    0.13       0  4783.6    0.07       0  4970.0    0.13       0
  4989.7    0.05       0  5010.3    0.13       0
Bank Sta=4989.7,5010.3
XS Rating Curve= 0
Exp/Cntr=0.3,0.1

Type RM Length L Ch R = 1,24811,488,488,488
BEGIN DESCRIPTION:
Grassy Creek 47.0
END DESCRIPTION:
XS GIS Cut Line= 4
      1566234.93       932376.64      1566339.35       932794.32
      1566269.74       933055.35      1566327.76       933241.01
#Sta/Elev= 30
  4790.0  930.20  4852.8  917.45  4886.4  904.96  4892.2  902.49  4908.9  892.54
  4938.9  879.38  4978.4  853.15  4989.7  848.34  4992.7  843.34  5007.3  843.34
  5010.3  848.34  5021.2  850.01  5030.7  853.03  5040.6  852.06  5047.1  851.35
  5093.7  853.44  5105.1  852.92  5136.9  854.76  5241.5  873.23  5276.3  877.58
  5288.0  877.97  5302.0  880.31  5313.4  880.84  5329.9  883.55  5412.6  891.88
  5490.7  897.52  5550.0  899.09  5633.2  906.85  5663.9  907.85  5685.2  907.12
#Mann=5,-1,0
  4790.0    0.13       0  4989.7    0.05       0  5010.3    0.13       0
  5040.6    0.07       0  5136.9    0.13       0
Bank Sta=4989.7,5010.3
XS Rating Curve= 0
Exp/Cntr=0.3,0.1

Type RM Length L Ch R = 1,24323,961,961,961
BEGIN DESCRIPTION:
Grassy Creek 46.0
END DESCRIPTION:
XS GIS Cut Line= 2
      1565834.69       932341.89      1565840.49       933385.98
#Sta/Elev= 30
  4646.7  917.84  4668.1  915.60  4713.3  908.67  4726.2  904.23  4768.3  892.98
  4782.5  887.14  4796.6  883.71  4825.7  869.59  4840.8  860.78  4858.6  853.74
  4879.0  850.02  4896.0  849.14  4980.7  850.16  4989.7  845.69  4992.7  840.69
  5007.3  840.69  5010.3  845.69  5035.5  848.80  5043.9  851.09  5083.3  850.91
  5107.4  849.03  5173.7  849.59  5212.3  851.28  5261.0  865.34  5299.6  874.34
  5382.1  888.32  5432.4  895.52  5556.1  907.64  5634.1  911.26  5690.8  917.35
#Mann=7,-1,0
  4646.7    0.13       0  4668.1    0.15       0  4858.6    0.13       0
  4989.7    0.05       0  5010.3    0.13       0  5107.4    0.07       0
  5212.3    0.13       0
Bank Sta=4989.7,5010.3
XS Rating Curve= 0
Exp/Cntr=0.3,0.1

Type RM Length L Ch R = 1,23362,917,917,917
BEGIN DESCRIPTION:
Grassy Creek 45.0
END DESCRIPTION:
XS GIS Cut Line= 4
      1565794.09       932301.26      1565434.44       932289.66
      1564981.99       932562.29      1564755.77       932852.31
#Sta/Elev= 30
  4203.0  916.65  4219.8  914.97  4260.6  909.82  4295.5  902.18  4311.0  900.33
  4441.4  875.17  4526.0  860.25  4553.5  857.04  4574.8  856.86  4628.1  848.68
  4659.2  846.90  4882.3  845.24  4936.3  843.90  4950.3  842.41  4957.2  844.01
  4976.0  846.98  4989.7  842.13  4992.7  837.13  5007.3  837.13  5010.3  842.13
  5019.3  846.42  5034.2  846.35  5051.1  849.60  5072.2  850.74  5087.8  855.76
  5120.5  860.10  5149.4  866.71  5279.5  887.41  5426.6  904.80  5458.9  907.01
#Mann=6,-1,0
  4203.0    0.13       0  4219.8    0.15       0  4526.0    0.07       0
  4957.2    0.13       0  4989.7    0.05       0  5010.3    0.13       0
Bank Sta=4989.7,5010.3
XS Rating Curve= 0
Exp/Cntr=0.3,0.1

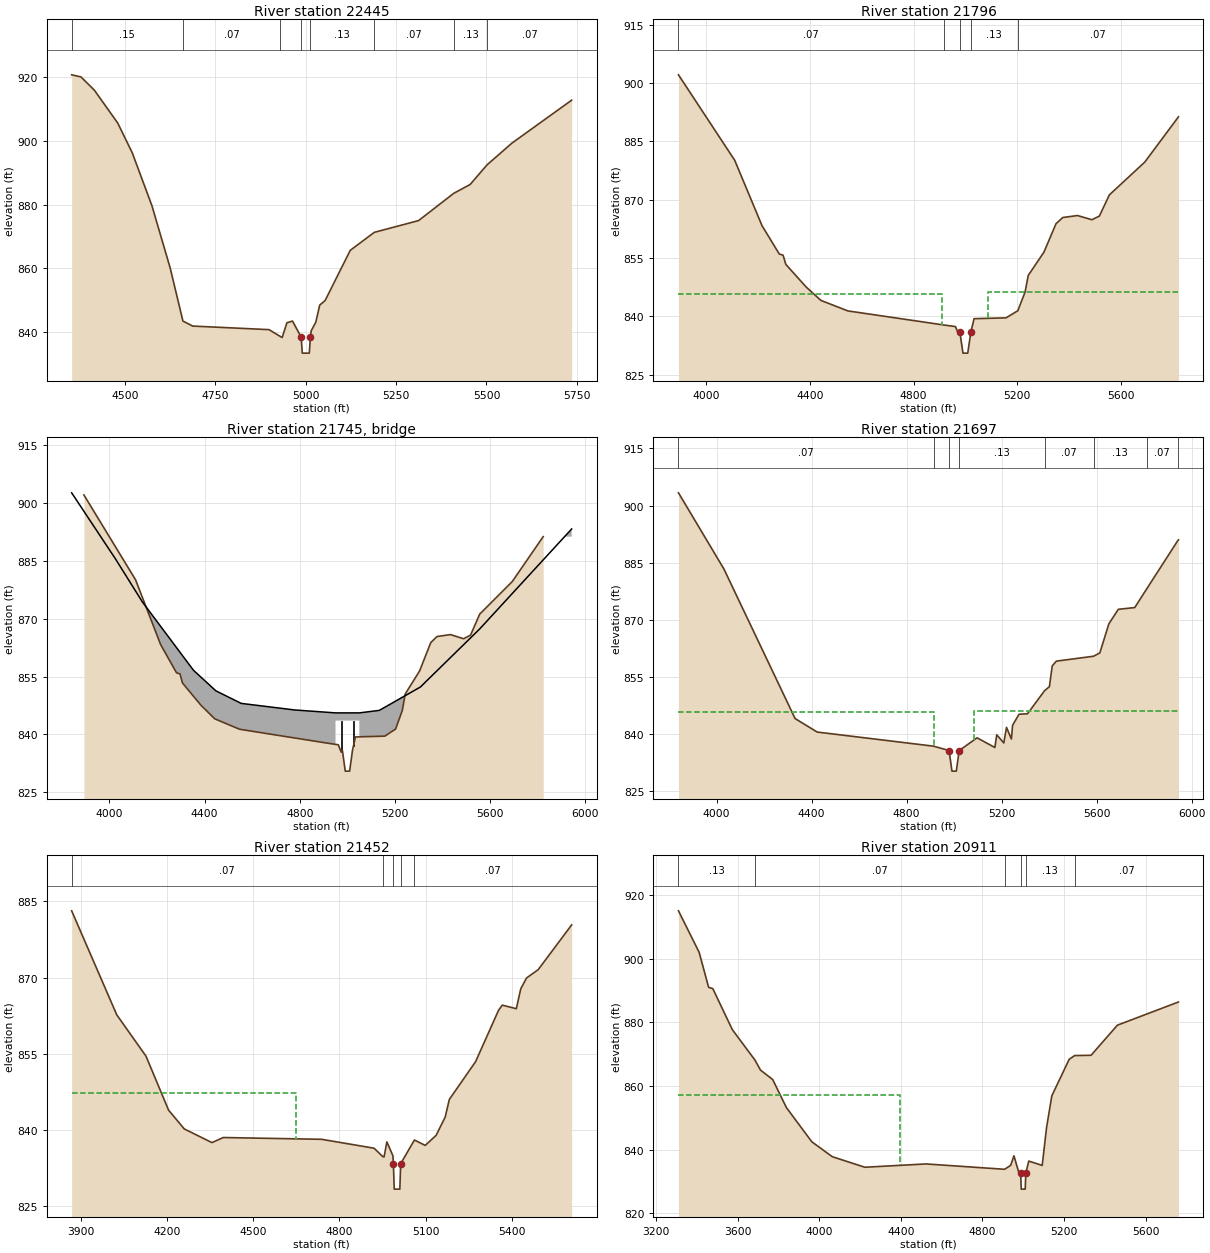
Type RM Length L Ch R = 1,22445,649,649,649
BEGIN DESCRIPTION:
Grassy Creek 44.0
END DESCRIPTION:
XS GIS Cut Line= 4
      1565428.68       931657.38      1564604.94       931715.39
      1564355.51       931692.18      1564053.92       931750.18
#Sta/Elev= 30
  4352.2  920.77  4378.0  920.11  4415.1  915.94  4479.7  905.61  4519.8  896.29
  4574.2  879.68  4624.7  860.13  4660.1  843.40  4687.2  841.83  4898.2  840.71
  4929.2  838.59  4934.7  838.25  4947.8  842.88  4963.3  843.40  4987.3  838.33
  4990.3  833.33  5009.7  833.33  5012.7  838.33  5015.0  840.34  5027.8  843.08
  5038.5  848.41  5053.6  849.87  5123.0  865.62  5189.6  871.28  5312.1  874.97
  5409.3  883.53  5454.7  886.31  5501.6  892.49  5570.4  899.31  5735.6  912.80
#Mann=8,-1,0
  4352.2    0.15       0  4660.1    0.07       0  4929.2    0.13       0
  4987.3    0.05       0  5012.7    0.13       0  5189.6    0.07       0
  5409.3    0.13       0  5501.6    0.07       0
Bank Sta=4987.3,5012.7
XS Rating Curve= 0
Exp/Cntr=0.5,0.3

Type RM Length L Ch R = 1,21796,99,99,99
BEGIN DESCRIPTION:
Stony Ridge Rd (GC) us
END DESCRIPTION:
XS GIS Cut Line= 5
      1565815.18       931141.36      1565433.18       931051.30
      1565169.23       931051.30      1564467.42       931097.88
      1564004.74       931430.14
#Sta/Elev= 30
  3892.9  902.10  4109.9  880.11  4215.4  863.28  4281.9  856.00  4296.7  855.69
  4307.1  853.34  4385.5  847.52  4442.6  844.06  4546.6  841.36  4916.8  837.74
  4961.7  837.33  4973.8  835.44  4978.8  835.90  4990.8  830.50  5009.2  830.50
  5021.2  835.90  5033.6  839.36  5156.9  839.57  5202.3  841.40  5230.4  846.21
  5242.7  850.50  5303.2  856.48  5349.9  863.81  5376.1  865.39  5432.7  865.90
  5488.1  864.82  5517.2  865.76  5555.7  871.21  5692.4  879.65  5822.3  891.29
#Mann=5,-1,0
  3892.9    0.07       0  4916.8    0.13       0  4978.8    0.05       0
  5021.2    0.13       0  5202.3    0.07       0
#XS Ineff=2,0
    0.00 4911.50  845.77 5088.50    0.00  846.25
Permanent Ineff=
       F       F
Bank Sta=4978.8,5021.2
XS Rating Curve= 0
Exp/Cntr=0.5,0.3

Type RM Length L Ch R =3,21745,,,
BEGIN DESCRIPTION:
Stony Ridge Rd (GC) TOR
Structure ID: LDS_GC_04
Approximate Survey Structure
END DESCRIPTION:
Bridge Culvert--1,0,-1,-1,0
Deck Dist Width WeirC Skew NumUp NumDn MinLoCord MaxHiCord MaxSubmerge Is_Ogee
38.5,25,3,,15,15,,,0.95,0,1,1,,,
  3841.5  4025.4  4138.7  4353.3  4447.2  4553.8  4777.8  4950.0  4950.0  5050.0
  5050.0  5133.9  5306.5  5555.8  5941.8
  902.65  885.53  874.35  856.64  851.32  848.06  846.36  845.60  845.60  845.60
  845.60  846.25  852.31  867.38  893.28
  810.50  810.50  810.50  810.50  810.50  810.50  810.50  810.50  843.60  843.60
  810.50  810.50  810.50  810.50  810.50
  3841.5  4025.4  4138.7  4353.3  4447.2  4553.8  4777.8  4950.0  4950.0  5050.0
  5050.0  5133.9  5306.5  5555.8  5941.8
  902.65  885.53  874.35  856.64  851.32  848.06  846.36  845.60  845.60  845.60
  845.60  846.25  852.31  867.38  893.28
  810.50  810.50  810.50  810.50  810.50  810.50  810.50  810.50  843.60  843.60
  810.50  810.50  810.50  810.50  810.50
Pier Skew, UpSta & Num, DnSta & Num=,4975,2,4975,2,0,0,0,0,0
       1       1
  837.16  843.60
       1       1
  836.91  843.60
Pier Skew, UpSta & Num, DnSta & Num=,5025,2,5025,2,0,0,0,0,0
       1       1
  837.16  843.60
       1       1
  836.91  843.60
Abutment Skew #Up #Dn=,2,2
  4950.0  4962.5
  843.60  837.25
  4950.0  4962.5
  843.60  834.07
Abutment Skew #Up #Dn=,2,2
  5037.5  5050.0
  839.35  843.60
  5037.5  5050.0
  835.53  843.60
BR Coef=1,1,0,1.25,0,,,0.8,0,2,0,
WSPro=,,,, 1 ,,,, 0 ,,,, 0 ,,,,-1 ,-1 ,-1 , 0 , 0 , 0 , 0 , 0
BC Design=,,0,,0,,,,,,

Type RM Length L Ch R = 1,21697,245,245,245
BEGIN DESCRIPTION:
Stony Ridge Rd (GC) ds
END DESCRIPTION:
XS GIS Cut Line= 6
      1565849.28       931051.30      1565333.81       930948.82
      1564777.96       930976.77      1564473.63       931007.83
      1564312.16       931069.93      1563896.07       931420.81
#Sta/Elev= 30
  3839.2  903.33  4030.4  883.35  4330.2  844.06  4423.3  840.51  4913.7  836.80
  4978.8  835.65  4990.8  830.25  5009.2  830.25  5021.2  835.65  5096.6  839.00
  5171.6  836.45  5179.4  839.79  5209.1  837.65  5220.6  841.73  5241.1  838.69
  5246.2  842.30  5273.3  845.19  5309.1  845.32  5381.1  851.39  5401.1  852.42
  5413.1  857.89  5430.5  859.13  5587.2  860.42  5613.5  861.29  5651.5  868.91
  5691.3  872.74  5760.5  873.20  5811.1  878.12  5941.8  890.78  5944.6  890.99
#Mann=8,-1,0
  3839.2    0.07       0  4913.7    0.13       0  4978.8    0.05       0
  5021.2    0.13       0  5381.1    0.07       0  5587.2    0.13       0
  5811.1    0.07       0  5941.8    0.13       0
#XS Ineff=2,0
    0.00 4914.50  845.67 5085.50    0.00  846.17
Permanent Ineff=
       F       F
Bank Sta=4978.8,5021.2
XS Rating Curve= 0
Exp/Cntr=0.5,0.3

Type RM Length L Ch R = 1,21452,541,541,541
BEGIN DESCRIPTION:
Grassy Creek 43.5
END DESCRIPTION:
XS GIS Cut Line= 5
      1565800.68       930835.28      1565396.91       930743.92
      1564993.14       930720.34      1564341.82       930764.55
      1564076.52       930788.13
#Sta/Elev= 30
  3869.2  883.12  4026.0  862.66  4127.6  854.53  4206.1  843.91  4260.6  840.22
  4356.9  837.53  4396.1  838.53  4737.8  838.18  4920.1  836.43  4950.1  834.80
  4954.8  834.71  4964.7  837.67  4985.9  834.91  4987.3  833.38  4990.3  828.38
  5009.7  828.38  5012.7  833.38  5060.3  838.04  5098.0  836.98  5135.7  838.95
  5167.4  842.56  5181.8  846.03  5273.1  853.46  5353.0  863.58  5365.8  864.57
  5414.6  863.87  5429.9  867.77  5449.9  869.90  5490.6  871.55  5606.8  880.35
#Mann=5,-1,0
  3869.2    0.07       0  4950.1    0.13       0  4987.3    0.05       0
  5012.7    0.13       0  5060.3    0.07       0
#XS Ineff=2,0
    0.00 4650.10  847.38               0
Permanent Ineff=
       F       F
Bank Sta=4987.3,5012.7
XS Rating Curve= 0
Exp/Cntr=0.3,0.1

Type RM Length L Ch R = 1,20911,521,521,521
BEGIN DESCRIPTION:
Grassy Creek 43.0
END DESCRIPTION:
XS GIS Cut Line= 4
      1566211.76       930665.47      1565620.06       930387.03
      1564459.92       930213.01      1563937.86       930555.25
#Sta/Elev= 30
  3309.8  914.98  3411.3  901.93  3457.5  890.97  3478.1  890.55  3573.7  877.69
  3684.6  868.13  3711.8  864.98  3771.9  861.99  3838.9  853.20  3963.7  842.45
  4063.9  837.77  4223.7  834.46  4523.0  835.50  4908.7  833.82  4938.5  835.05
  4954.5  838.06  4977.1  833.12  4987.3  832.59  4990.3  827.59  5009.7  827.59
  5012.7  832.59  5027.1  836.40  5093.1  835.04  5114.5  846.95  5140.3  856.89
  5225.5  868.36  5252.3  869.53  5332.8  869.62  5461.7  879.07  5761.1  886.35
#Mann=6,-1,0
  3309.8    0.13       0  3684.6    0.07       0  4908.7    0.13       0
  4987.3    0.05       0  5012.7    0.13       0  5252.3    0.07       0
#XS Ineff=2,0
    0.00 4394.80  857.28               0
Permanent Ineff=
       F       F
Bank Sta=4987.3,5012.7
XS Rating Curve= 0
Exp/Cntr=0.3,0.1

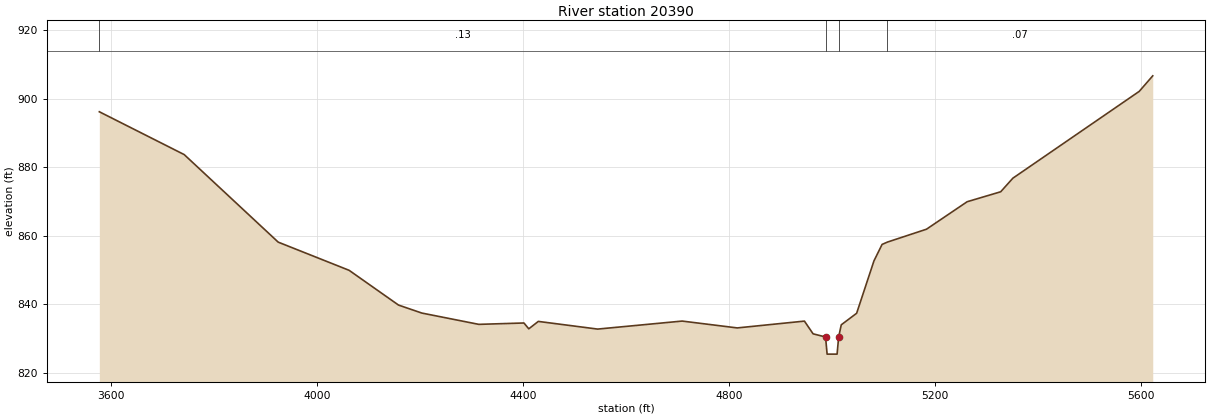
Type RM Length L Ch R = 1,20390,972,972,972
BEGIN DESCRIPTION:
Grassy Creek 42.0
END DESCRIPTION:
XS GIS Cut Line= 4
      1566083.85       930260.66      1565808.96       929957.01
      1564738.36       929789.55      1564210.52       929632.94
#Sta/Elev= 30
  3578.3  896.17  3743.0  883.66  3925.4  858.10  4062.9  849.88  4158.8  839.73
  4204.0  837.40  4314.5  834.10  4402.1  834.50  4411.5  832.80  4430.0  834.96
  4545.1  832.72  4709.1  835.06  4816.0  833.06  4946.3  835.05  4963.1  831.34
  4987.3  830.41  4990.3  825.41  5009.7  825.41  5012.7  830.41  5017.8  833.97
  5047.6  837.34  5081.2  852.63  5097.0  857.44  5107.3  858.12  5183.1  861.88
  5262.0  869.90  5327.1  872.81  5350.7  876.77  5595.9  902.12  5622.1  906.66
#Mann=4,-1,0
  3578.3    0.13       0  4987.3    0.05       0  5012.7    0.13       0
  5107.3    0.07       0
Bank Sta=4987.3,5012.7
XS Rating Curve= 0
Exp/Cntr=0.3,0.1