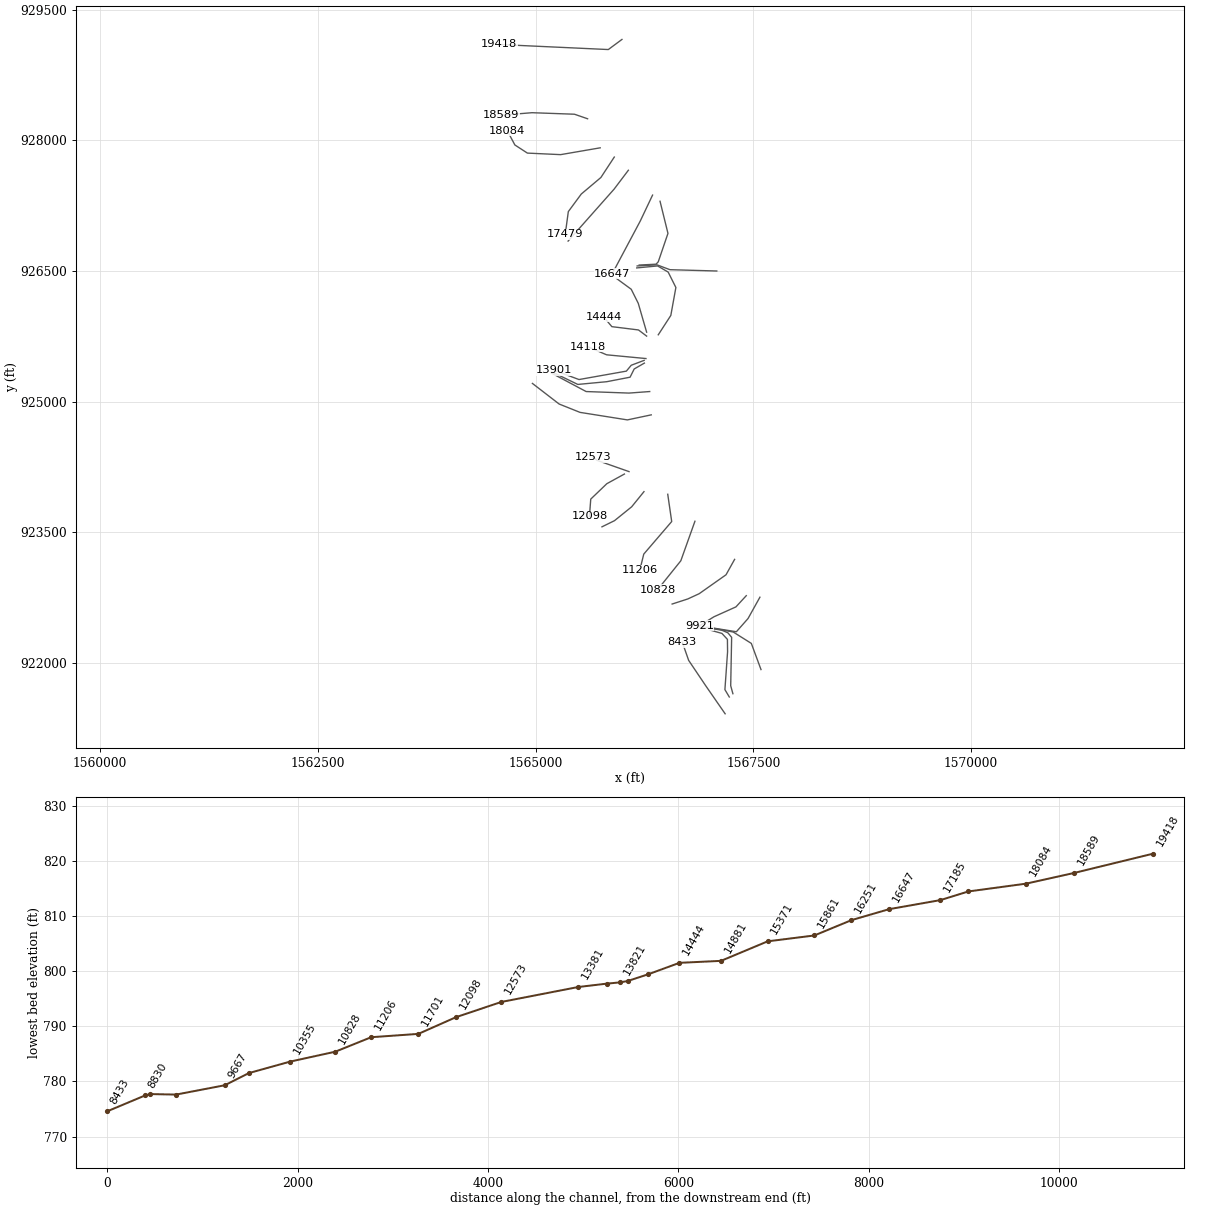
HEC-RAS study Grassy Creek.prj: Grassy Creek Limited Detail Study

--- Grassy Creek.g01 (geometry) --- (continued)

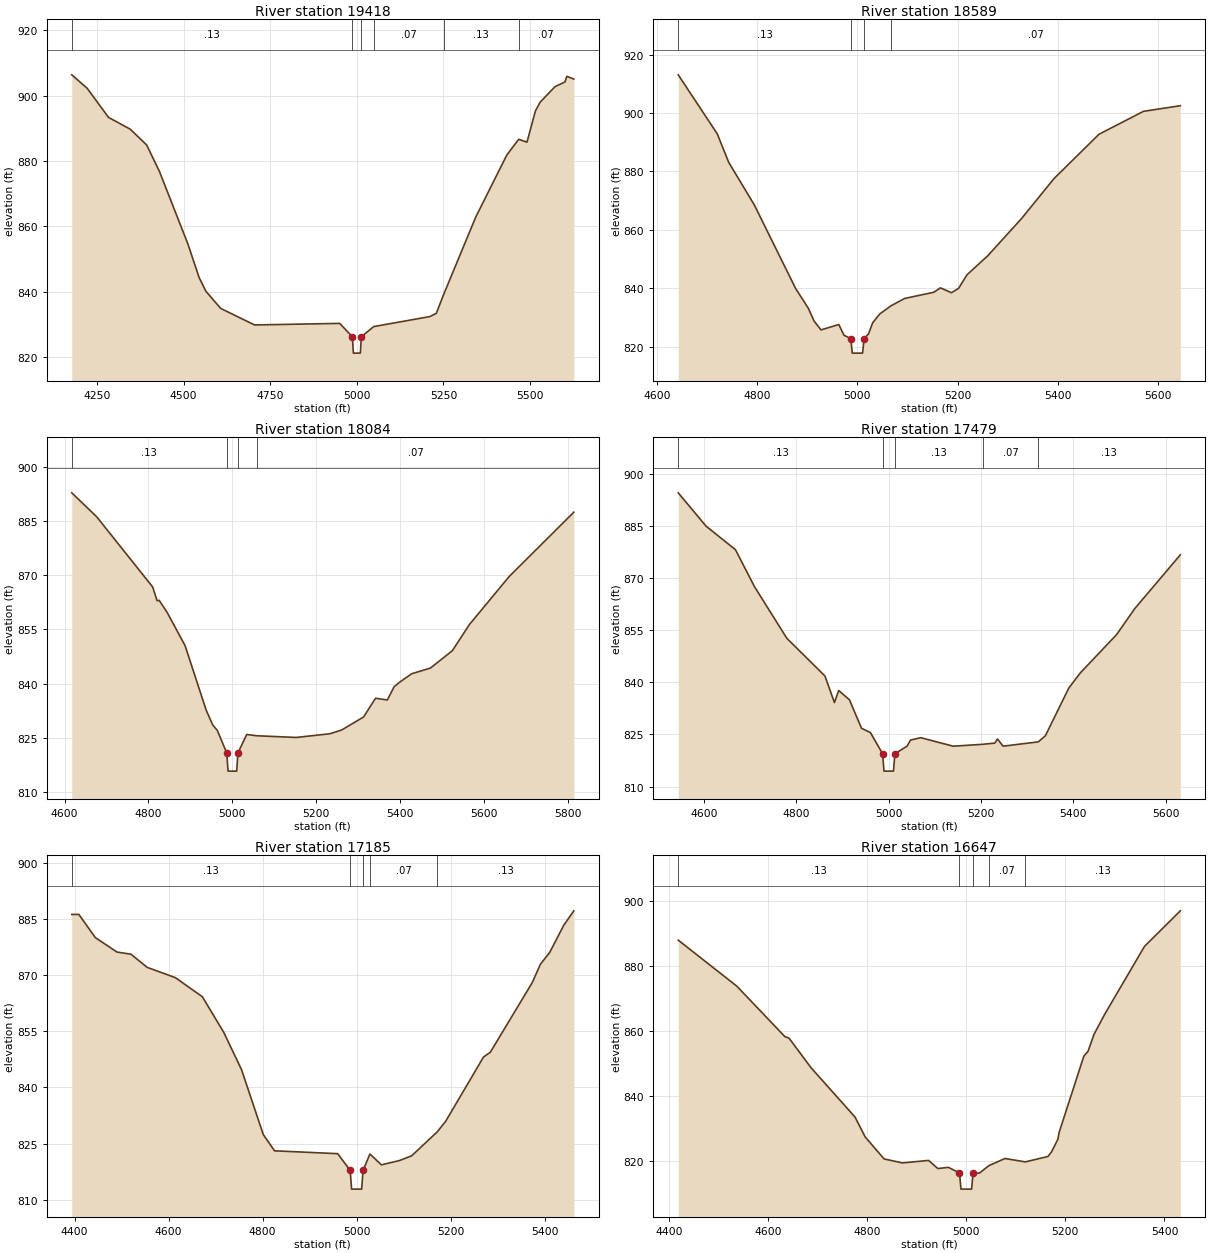
Type RM Length L Ch R = 1,19418,829,829,829
BEGIN DESCRIPTION:
Grassy Creek 41.0
END DESCRIPTION:
XS GIS Cut Line= 3
      1565991.34       929157.30      1565834.69       929041.26
      1564581.77       929099.27
#Sta/Elev= 30
  4177.1  906.33  4221.7  902.21  4283.2  893.32  4345.8  889.72  4393.2  884.90
  4429.9  876.87  4512.2  854.66  4544.7  844.37  4564.4  840.15  4607.1  834.93
  4704.8  829.88  4950.5  830.36  4987.0  826.27  4990.0  821.27  5010.0  821.27
  5013.0  826.27  5048.5  829.38  5210.7  832.44  5229.4  833.45  5250.4  839.17
  5343.6  862.96  5432.7  881.79  5467.0  886.62  5491.1  885.76  5515.4  895.30
  5529.2  897.99  5572.2  902.74  5600.7  904.15  5606.1  905.88  5626.3  905.04
#Mann=6,-1,0
  4177.1    0.13       0  4987.0    0.05       0  5013.0    0.13       0
  5048.5    0.07       0  5250.4    0.13       0  5467.0    0.07       0
Bank Sta=4987,5013
XS Rating Curve= 0
Exp/Cntr=0.3,0.1

Type RM Length L Ch R = 1,18589,505,505,505
BEGIN DESCRIPTION:
Grassy Creek 40.0
END DESCRIPTION:
XS GIS Cut Line= 4
      1565596.90       928246.55      1565446.04       928298.77
      1564958.78       928316.18      1564604.98       928287.18
#Sta/Elev= 30
  4642.3  913.05  4720.2  892.85  4743.1  883.08  4794.3  868.47  4876.6  839.91
  4901.9  833.17  4913.3  828.81  4927.3  825.73  4962.8  827.58  4973.2  823.89
  4986.7  822.78  4989.7  817.78  5010.3  817.78  5013.3  822.78  5022.2  824.37
  5030.3  828.13  5044.3  831.15  5067.3  834.01  5094.3  836.50  5152.6  838.62
  5165.6  840.13  5187.6  838.46  5202.0  839.96  5218.7  844.60  5260.0  851.09
  5327.9  863.91  5392.4  877.53  5482.1  892.70  5571.0  900.55  5644.5  902.48
#Mann=4,-1,0
  4642.3    0.13       0  4986.7    0.05       0  5013.3    0.13       0
  5067.3    0.07       0
Bank Sta=4986.7,5013.3
XS Rating Curve= 0
Exp/Cntr=0.3,0.1

Type RM Length L Ch R = 1,18084,605,605,605
BEGIN DESCRIPTION:
Grassy Creek 39.0
END DESCRIPTION:
XS GIS Cut Line= 5
      1565741.70       927913.01      1565287.19       927834.73
      1564905.86       927852.41      1564761.92       927945.84
      1564676.09       928107.41
#Sta/Elev= 30
  4617.0  892.77  4676.5  886.14  4810.1  866.73  4820.5  862.95  4825.5  863.06
  4845.1  859.59  4887.3  850.52  4937.7  832.66  4953.3  828.59  4964.1  827.10
  4986.7  820.84  4989.7  815.84  5010.3  815.84  5013.3  820.84  5034.2  825.97
  5059.0  825.61  5152.6  825.15  5232.8  826.17  5260.4  827.19  5313.0  830.80
  5341.5  835.99  5369.7  835.51  5386.0  839.19  5398.4  840.37  5427.8  842.76
  5472.5  844.33  5524.7  849.12  5565.4  856.36  5660.1  869.61  5814.5  887.42
#Mann=4,-1,0
  4617.0    0.13       0  4986.7    0.05       0  5013.3    0.13       0
  5059.0    0.07       0
Bank Sta=4986.7,5013.3
XS Rating Curve= 0
Exp/Cntr=0.3,0.1

Type RM Length L Ch R = 1,17479,294,294,294
BEGIN DESCRIPTION:
Grassy Creek 38.0
END DESCRIPTION:
XS GIS Cut Line= 5
      1565903.37       927806.96      1565749.32       927572.10
      1565524.57       927382.70      1565375.58       927180.67
      1565340.22       926920.58
#Sta/Elev= 30
  4543.7  894.62  4604.0  885.02  4667.7  878.25  4708.9  867.60  4779.2  852.69
  4861.7  841.85  4882.3  834.19  4891.5  837.66  4914.8  834.99  4941.0  826.78
  4960.4  825.52  4986.7  819.43  4989.7  814.43  5010.3  814.43  5013.3  819.43
  5039.7  821.62  5047.1  823.38  5069.5  824.06  5139.8  821.61  5203.5  822.16
  5229.9  822.51  5235.7  823.70  5247.8  821.62  5324.1  822.86  5339.5  824.61
  5390.1  838.32  5415.1  842.71  5494.0  853.79  5533.2  861.25  5632.0  876.75
#Mann=5,-1,0
  4543.7    0.13       0  4986.7    0.05       0  5013.3    0.13       0
  5203.5    0.07       0  5324.1    0.13       0
Bank Sta=4986.7,5013.3
XS Rating Curve= 0
Exp/Cntr=0.3,0.1

Type RM Length L Ch R = 1,17185,538,538,538
BEGIN DESCRIPTION:
Grassy Creek 37.0
END DESCRIPTION:
XS GIS Cut Line= 4
      1566064.99       927655.43      1565900.84       927438.25
      1565527.09       927016.52      1565373.06       926842.29
#Sta/Elev= 30
  4393.9  886.13  4408.9  886.16  4444.1  879.96  4490.2  876.11  4519.8  875.54
  4554.3  872.03  4614.5  869.27  4671.8  864.18  4717.2  854.71  4755.2  844.71
  4801.4  827.42  4825.4  823.08  4959.7  822.32  4986.3  817.86  4989.3  812.86
  5010.7  812.86  5013.7  817.86  5028.3  822.23  5052.7  819.34  5091.4  820.49
  5117.1  821.75  5171.8  828.17  5189.7  831.00  5269.9  848.09  5284.5  849.38
  5373.7  867.96  5391.1  872.86  5410.9  876.02  5440.9  883.30  5462.2  887.11
#Mann=5,-1,0
  4393.9    0.13       0  4986.3    0.05       0  5013.7    0.13       0
  5028.3    0.07       0  5171.8    0.13       0
Bank Sta=4986.3,5013.7
XS Rating Curve= 0
Exp/Cntr=0.3,0.1

Type RM Length L Ch R = 1,16647,396,396,396
BEGIN DESCRIPTION:
Grassy Creek 36.0
END DESCRIPTION:
XS GIS Cut Line= 3
      1566342.80       927370.11      1566201.36       927072.08
      1565880.24       926468.70
#Sta/Elev= 30
  4418.6  887.97  4536.9  873.77  4633.8  858.24  4642.3  857.75  4686.4  848.69
  4775.4  833.44  4795.9  827.31  4834.2  820.52  4871.2  819.30  4923.9  820.07
  4942.6  817.56  4963.9  817.93  4986.3  816.22  4989.3  811.22  5010.7  811.22
  5013.7  816.22  5026.2  816.13  5045.6  818.46  5078.1  820.66  5119.2  819.62
  5164.8  821.28  5172.1  822.71  5185.0  826.62  5187.4  828.68  5237.2  852.17
  5245.8  853.71  5257.7  858.90  5279.5  865.14  5359.7  886.04  5432.0  897.00
#Mann=5,-1,0
  4418.6    0.13       0  4986.3    0.05       0  5013.7    0.13       0
  5045.6    0.07       0  5119.2    0.13       0
Bank Sta=4986.3,5013.7
XS Rating Curve= 0
Exp/Cntr=0.3,0.1

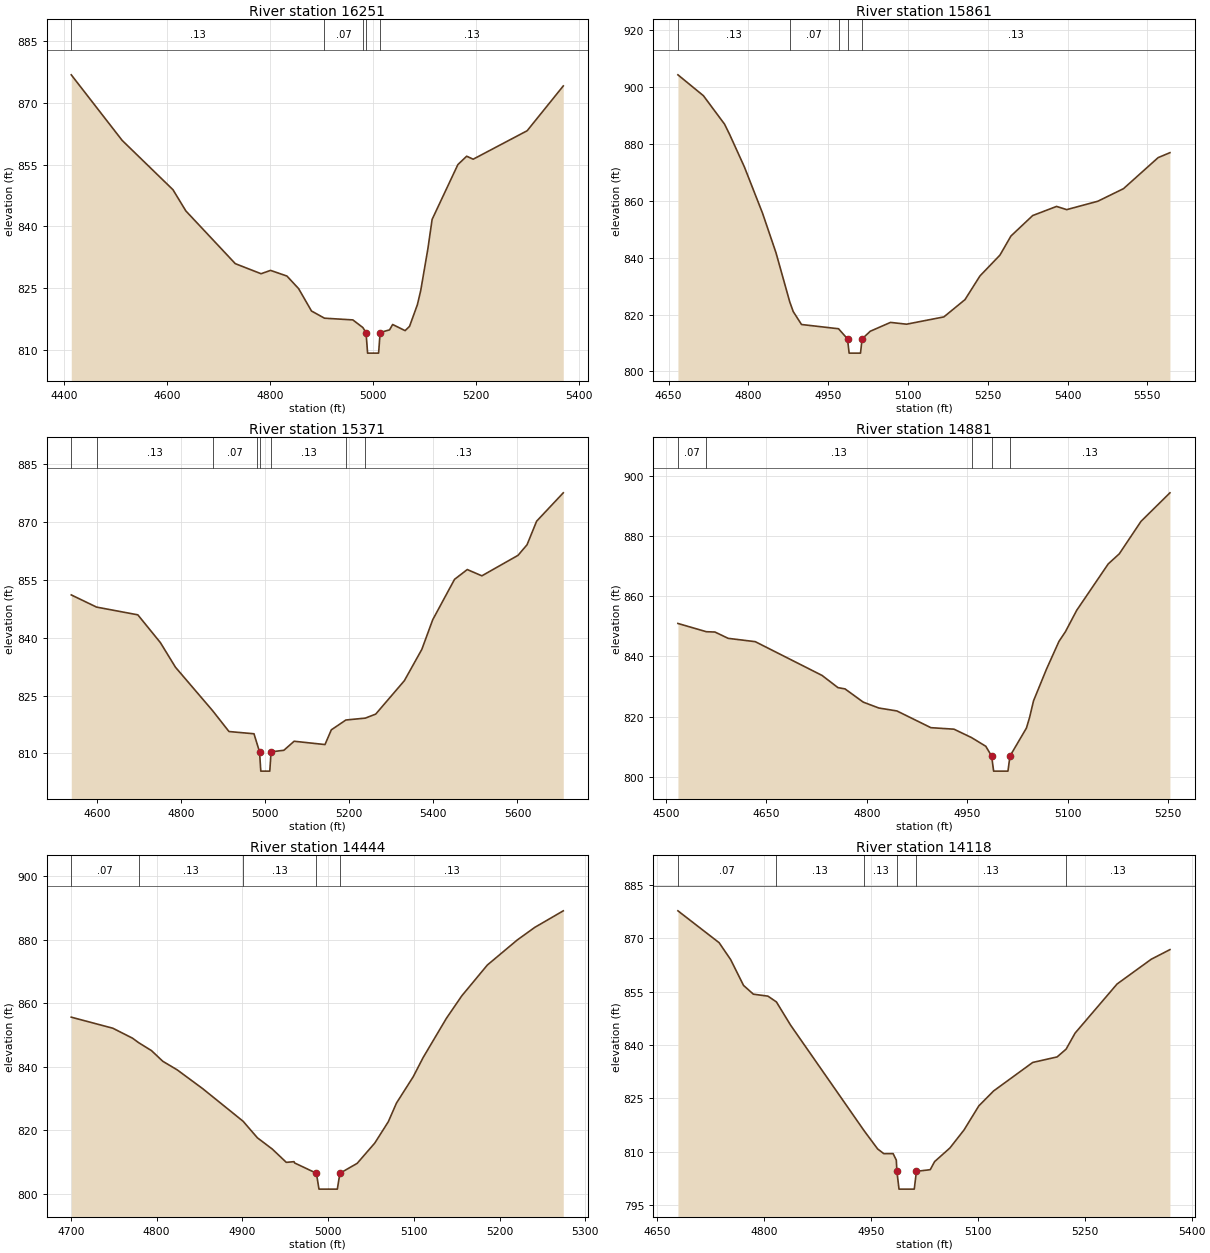
Type RM Length L Ch R = 1,16251,390,390,390
BEGIN DESCRIPTION:
Grassy Creek 35.0
END DESCRIPTION:
XS GIS Cut Line= 5
      1566428.63       927299.39      1566519.55       926930.66
      1566408.43       926604.90      1566383.18       926577.12
      1566188.75       926567.02
#Sta/Elev= 30
  4413.4  876.77  4512.3  860.86  4611.1  848.88  4636.1  843.74  4732.2  830.94
  4782.3  828.50  4800.7  829.31  4832.5  827.94  4855.2  824.89  4880.3  819.45
  4905.5  817.71  4960.7  817.29  4980.0  815.45  4986.3  814.23  4989.3  809.23
  5010.7  809.23  5013.7  814.23  5032.0  814.88  5038.0  816.18  5062.2  814.69
  5070.8  815.72  5086.1  820.99  5092.6  824.45  5106.5  834.57  5114.7  841.68
  5164.8  854.99  5181.9  857.02  5194.5  856.29  5299.4  863.20  5369.6  874.07
#Mann=5,-1,0
  4413.4    0.13       0  4905.5    0.07       0  4980.0    0.13       0
  4986.3    0.05       0  5013.7    0.13       0
Bank Sta=4986.3,5013.7
XS Rating Curve= 0
Exp/Cntr=0.3,0.1

Type RM Length L Ch R = 1,15861,490,490,490
BEGIN DESCRIPTION:
Grassy Creek 34.0
END DESCRIPTION:
XS GIS Cut Line= 4
      1567080.18       926498.83      1566542.28       926513.98
      1566393.28       926569.54      1566165.96       926556.91
#Sta/Elev= 30
  4667.5  904.18  4715.4  896.85  4755.1  886.87  4764.5  883.32  4792.5  871.80
  4826.5  855.61  4851.8  841.72  4877.8  824.38  4884.2  821.06  4899.8  816.50
  4969.4  815.01  4986.3  811.45  4989.3  806.45  5010.7  806.45  5013.7  811.45
  5029.0  814.13  5067.1  817.24  5097.2  816.61  5167.4  819.17  5207.1  825.24
  5235.2  833.55  5272.8  840.87  5293.5  847.58  5334.3  854.76  5379.2  857.97
  5398.3  856.84  5456.8  859.79  5505.0  864.20  5570.1  875.10  5592.3  876.84
#Mann=5,-1,0
  4667.5    0.13       0  4877.8    0.07       0  4969.4    0.13       0
  4986.3    0.05       0  5013.7    0.13       0
Bank Sta=4986.3,5013.7
XS Rating Curve= 0
Exp/Cntr=0.3,0.1

Type RM Length L Ch R = 1,15371,490,490,490
BEGIN DESCRIPTION:
Grassy Creek 33.0
END DESCRIPTION:
XS GIS Cut Line= 6
      1566408.42       925766.47      1566552.38       925988.72
      1566610.46       926309.43      1566522.07       926486.21
      1566400.86       926556.91      1566161.00       926534.19
#Sta/Elev= 30
  4538.3  851.10  4598.5  847.94  4696.7  845.93  4750.2  838.75  4786.4  832.32
  4874.7  821.06  4913.6  815.66  4973.1  815.08  4979.2  812.91  4986.3  810.39
  4989.3  805.39  5010.7  805.39  5013.7  810.39  5044.2  810.80  5068.6  813.14
  5142.0  812.28  5157.1  816.10  5191.7  818.65  5237.9  819.14  5262.7  820.18
  5330.9  828.85  5372.5  836.98  5398.4  844.67  5450.3  855.14  5480.6  857.68
  5515.3  856.05  5601.4  861.37  5622.8  864.11  5645.6  870.22  5709.0  877.58
#Mann=8,-1,0
  4538.3    0.07       0  4598.5    0.13       0  4874.7    0.07       0
  4979.2    0.13       0  4986.3    0.05       0  5013.7    0.13       0
  5191.7    0.07       0  5237.9    0.13       0
Bank Sta=4986.3,5013.7
XS Rating Curve= 0
Exp/Cntr=0.3,0.1

Type RM Length L Ch R = 1,14881,437,437,437
BEGIN DESCRIPTION:
Grassy Creek 32.0
END DESCRIPTION:
XS GIS Cut Line= 4
      1566274.59       925796.79      1566178.63       926127.61
      1566097.82       926289.23      1565928.60       926412.99
#Sta/Elev= 30
  4517.8  850.99  4560.3  848.24  4573.1  848.14  4592.8  846.04  4633.3  844.93
  4733.1  833.69  4756.8  829.64  4767.4  829.21  4794.6  824.81  4817.8  822.86
  4844.9  821.87  4895.6  816.31  4930.1  815.81  4956.3  813.01  4977.6  810.12
  4986.3  806.85  4989.3  801.85  5010.7  801.85  5013.7  806.85  5038.3  816.19
  5043.0  819.73  5048.9  825.25  5068.3  835.82  5086.9  845.03  5096.5  848.23
  5113.3  855.34  5160.4  870.79  5177.0  874.17  5209.4  884.97  5252.6  894.46
#Mann=5,-1,0
  4517.8    0.07       0  4560.3    0.13       0  4956.3    0.13       0
  4986.3    0.05       0  5013.7    0.13       0
Bank Sta=4986.3,5013.7
XS Rating Curve= 0
Exp/Cntr=0.3,0.1

Type RM Length L Ch R = 1,14444,326,326,326
BEGIN DESCRIPTION:
Grassy Creek 31.0
END DESCRIPTION:
XS GIS Cut Line= 4
      1566274.55       925751.36      1566181.15       925822.04
      1565875.59       925859.92      1565779.61       925973.59
#Sta/Elev= 30
  4700.4  855.65  4748.9  852.17  4771.8  849.04  4779.1  847.60  4794.0  845.11
  4807.1  841.77  4824.0  839.05  4853.8  833.11  4900.8  822.87  4917.5  817.65
  4934.8  814.12  4951.2  809.92  4960.2  810.14  4960.9  809.73  4986.3  806.49
  4989.3  801.49  5010.7  801.49  5013.7  806.49  5033.8  809.60  5054.4  816.01
  5070.2  822.74  5079.7  828.61  5099.2  836.89  5110.8  842.95  5137.9  855.29
  5155.9  862.39  5185.7  872.09  5220.6  879.98  5241.0  883.94  5274.2  889.15
#Mann=5,-1,0
  4700.4    0.07       0  4779.1    0.13       0  4900.8    0.13       0
  4986.3    0.05       0  5013.7    0.13       0
Bank Sta=4986.3,5013.7
XS Rating Curve= 0
Exp/Cntr=0.3,0.1

Type RM Length L Ch R = 1,14118,217,217,217
BEGIN DESCRIPTION:
Grassy Creek 30.0
END DESCRIPTION:
XS GIS Cut Line= 3
      1566267.00       925493.75      1565814.98       925536.68
      1565597.79       925630.13
#Sta/Elev= 30
  4679.0  877.69  4736.8  868.73  4753.0  863.98  4771.1  856.71  4784.9  854.25
  4805.3  853.70  4817.2  852.08  4837.1  845.55  4940.5  815.80  4959.3  810.73
  4968.0  809.40  4981.0  809.42  4985.5  807.58  4986.3  804.43  4989.3  799.43
  5010.7  799.43  5013.7  804.43  5033.1  804.90  5039.3  807.18  5060.7  811.00
  5080.5  816.06  5101.3  822.84  5122.0  827.03  5176.9  835.05  5211.2  836.61
  5223.8  838.80  5236.4  843.30  5295.3  857.11  5343.3  864.08  5369.5  866.78
#Mann=6,-1,0
  4679.0    0.07       0  4817.2    0.13       0  4940.5    0.13       0
  4986.3    0.05       0  5013.7    0.13       0  5223.8    0.13       0
Bank Sta=4986.3,5013.7
XS Rating Curve= 0
Exp/Cntr=0.5,0.3

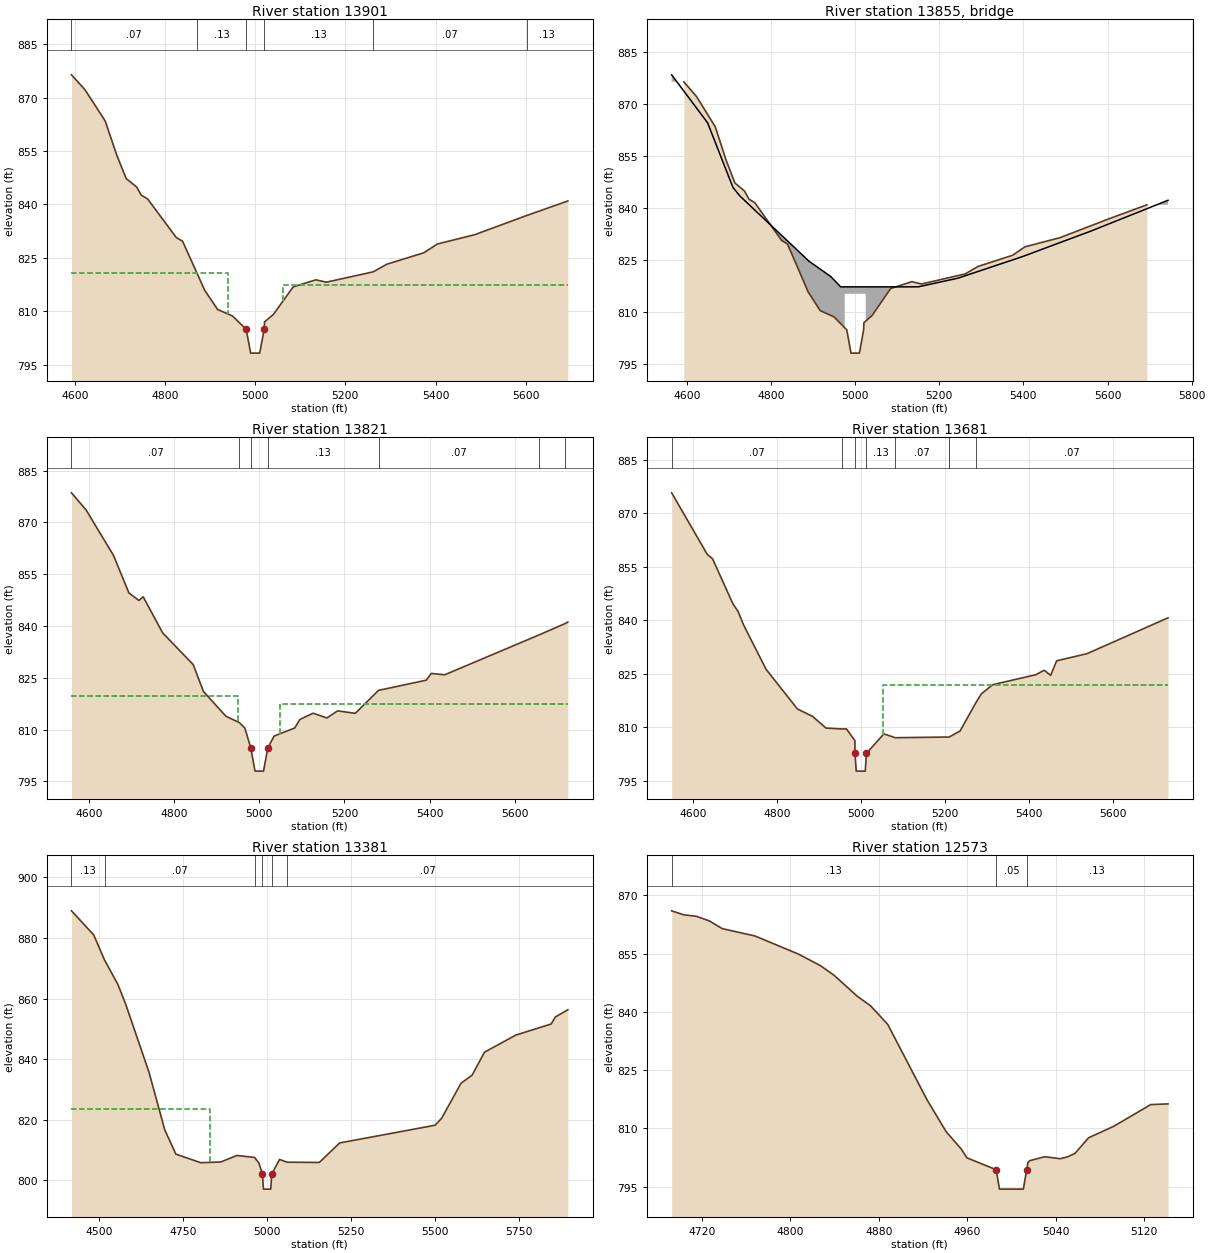
Type RM Length L Ch R = 1,13901,80,80,80
BEGIN DESCRIPTION:
Grassy Creek Rd (GC) us
END DESCRIPTION:
XS GIS Cut Line= 5
      1566246.43       925472.94      1566098.14       925416.77
      1566041.96       925349.36      1565498.16       925252.73
      1565215.06       925358.33
#Sta/Elev= 30
  4592.6  876.37  4622.6  872.17  4667.3  863.42  4692.8  853.89  4713.9  847.23
  4736.8  844.91  4747.4  842.57  4761.3  841.54  4825.1  830.66  4838.9  829.65
  4870.2  820.88  4887.9  815.89  4916.8  810.44  4949.4  808.67  4980.0  804.90
  4990.0  798.20  5010.0  798.20  5020.0  804.90  5020.7  806.97  5040.3  809.05
  5084.2  816.80  5134.6  818.79  5157.7  818.12  5261.6  821.03  5292.3  823.19
  5374.2  826.39  5403.8  828.84  5487.2  831.48  5602.1  836.85  5693.4  840.93
#Mann=6,-1,0
  4592.6    0.07       0  4870.2    0.13       0  4980.0    0.05       0
  5020.0    0.13       0  5261.6    0.07       0  5602.1    0.13       0
#XS Ineff=2,0
    0.00 4939.00  820.58 5061.00    0.00  817.30
Permanent Ineff=
       F       F
Bank Sta=4980,5020
XS Rating Curve= 0
Exp/Cntr=0.5,0.3

Type RM Length L Ch R =3,13855,,,
BEGIN DESCRIPTION:
Grassy Creek Rd (GC) TOR
Structure ID: LDS_GC_03
Approximate Survey Structure
END DESCRIPTION:
Bridge Culvert--1,0,-1,-1,0
Deck Dist Width WeirC Skew NumUp NumDn MinLoCord MaxHiCord MaxSubmerge Is_Ogee
36,20,3,,16,16,,,0.95,0,1,1,,,
  4563.6  4649.1  4709.3  4726.0  4890.2  4941.9  4965.4  4975.0  4975.0  5025.0
  5025.0  5149.7  5244.6  5395.9  5560.8  5743.8
  878.40  864.56  845.96  843.46  824.68  820.28  817.30  817.30  817.30  817.30
  817.30  817.30  819.81  825.94  833.39  842.25
  778.20  778.20  778.20  778.20  778.20  778.20  778.20  778.20  815.30  815.30
  778.20  778.20  778.20  778.20  778.20  778.20
  4563.6  4649.1  4709.3  4726.0  4890.2  4941.9  4965.4  4975.0  4975.0  5025.0
  5025.0  5149.7  5244.6  5395.9  5560.8  5743.8
  878.40  864.56  845.96  843.46  824.68  820.28  817.30  817.30  817.30  817.30
  817.30  817.30  819.81  825.94  833.39  842.25
  778.20  778.20  778.20  778.20  778.20  778.20  778.20  778.20  815.30  815.30
  778.20  778.20  778.20  778.20  778.20  778.20
BR Coef=1,1,0,1.25,0,,,0.8,0,2,0,
WSPro=,,,, 1 ,,,, 0 ,,,, 0 ,,,,-1 ,-1 ,-1 , 0 , 0 , 0 , 0 , 0
BC Design=,,0,,0,,,,,,

Type RM Length L Ch R = 1,13821,140,140,140
BEGIN DESCRIPTION:
Grassy Creek Rd (GC) ds
END DESCRIPTION:
XS GIS Cut Line= 6
      1566248.68       925441.48      1566131.84       925374.07
      1566084.65       925279.70      1565817.25       925228.01
      1565484.68       925196.55      1565197.06       925335.87
#Sta/Elev= 30
  4558.7  878.55  4592.9  873.61  4657.5  860.42  4693.6  849.57  4717.2  847.37
  4727.2  848.44  4772.9  838.00  4844.8  828.79  4868.8  821.02  4921.6  813.85
  4953.3  811.99  4966.2  810.41  4980.0  804.65  4990.0  797.95  5010.0  797.95
  5020.0  804.65  5035.0  808.11  5083.3  810.44  5095.3  812.90  5126.5  814.73
  5159.0  813.35  5184.0  815.40  5225.6  814.69  5280.3  821.34  5392.4  824.29
  5404.2  826.24  5435.8  825.85  5658.2  837.44  5718.6  840.68  5725.1  841.13
#Mann=7,-1,0
  4558.7    0.07       0  4953.3    0.13       0  4980.0    0.05       0
  5020.0    0.13       0  5280.3    0.07       0  5658.2    0.13       0
  5718.6    0.07       0
#XS Ineff=2,0
    0.00 4951.00  819.79 5049.00    0.00  817.30
Permanent Ineff=
       F       F
Bank Sta=4980,5020
XS Rating Curve= 0
Exp/Cntr=0.5,0.3

Type RM Length L Ch R = 1,13681,300,300,300
BEGIN DESCRIPTION:
Grassy Creek 29.0
END DESCRIPTION:
XS GIS Cut Line= 4
      1566309.97       925114.95      1566072.57       925097.28
      1565580.13       925114.95      1565181.13       925327.08
#Sta/Elev= 30
  4549.5  875.73  4634.3  858.48  4646.9  857.25  4695.6  844.58  4707.6  842.51
  4720.7  838.74  4774.4  826.27  4849.2  815.14  4885.1  813.08  4917.2  809.79
  4954.7  809.54  4966.0  809.55  4986.1  806.27  4986.3  802.72  4989.3  797.72
  5010.7  797.72  5013.7  802.72  5055.2  808.16  5082.0  807.09  5210.6  807.28
  5236.6  808.95  5274.3  816.88  5287.7  819.43  5314.7  821.95  5416.8  824.73
  5437.2  826.00  5452.5  824.56  5466.9  828.65  5538.7  830.62  5732.2  840.69
#Mann=7,-1,0
  4549.5    0.07       0  4954.7    0.13       0  4986.3    0.05       0
  5013.7    0.13       0  5082.0    0.07       0  5210.6    0.13       0
  5274.3    0.07       0
#XS Ineff=2,0
       0                 5053.10    0.00  821.88
Permanent Ineff=
       F       F
Bank Sta=4986.3,5013.7
XS Rating Curve= 0
Exp/Cntr=0.3,0.1

Type RM Length L Ch R = 1,13381,808,808,808
BEGIN DESCRIPTION:
Grassy Creek 28.0
END DESCRIPTION:
XS GIS Cut Line= 5
      1566327.62       924847.27      1566053.50       924789.40
      1565510.08       924875.70      1565270.34       924971.60
      1564963.44       925208.17
#Sta/Elev= 30
  4418.3  888.94  4484.4  880.99  4516.7  872.69  4556.2  864.68  4579.8  858.06
  4649.1  835.58  4695.7  816.66  4728.7  808.66  4802.9  805.83  4862.5  806.07
  4910.2  808.22  4962.8  807.57  4975.8  805.69  4986.2  802.11  4989.2  797.11
  5010.8  797.11  5013.8  802.11  5037.2  806.90  5059.9  806.00  5155.3  805.91
  5215.8  812.35  5499.4  818.19  5518.8  820.44  5576.8  832.05  5609.7  834.73
  5646.6  842.30  5739.9  847.95  5844.7  851.59  5857.3  853.91  5894.4  856.30
#Mann=6,-1,0
  4418.3    0.13       0  4516.7    0.07       0  4962.8    0.13       0
  4986.2    0.05       0  5013.8    0.13       0  5059.9    0.07       0
#XS Ineff=2,0
    0.00 4830.10  823.62               0
Permanent Ineff=
       F       F
Bank Sta=4986.2,5013.8
XS Rating Curve= 0
Exp/Cntr=0.3,0.1

Type RM Length L Ch R = 1,12573,475,475,475
BEGIN DESCRIPTION:
Grassy Creek 27.0
END DESCRIPTION:
XS GIS Cut Line= 3
      1566072.56       924195.73      1565706.39       924324.53
      1565659.23       924362.64
#Sta/Elev= 30
  4692.8  866.00  4703.7  864.97  4715.2  864.59  4726.8  863.41  4738.5  861.42
  4768.1  859.53  4807.5  854.86  4827.4  851.88  4839.6  849.43  4860.8  843.98
  4872.6  841.58  4888.2  836.77  4923.5  817.48  4941.0  809.17  4954.5  804.77
  4959.7  802.46  4986.2  799.40  4989.2  794.40  5010.8  794.40  5013.8  799.40
  5014.9  801.22  5016.6  801.72  5030.2  802.74  5044.2  802.22  5050.6  802.70
  5057.5  803.58  5069.7  807.60  5092.4  810.55  5126.0  816.15  5141.6  816.33
#Mann=3,-1,0
  4692.8    0.13       0  4986.2    0.05       0  5013.8    0.13       0
Bank Sta=4986.2,5013.8
XS Rating Curve= 0
Exp/Cntr=0.3,0.1

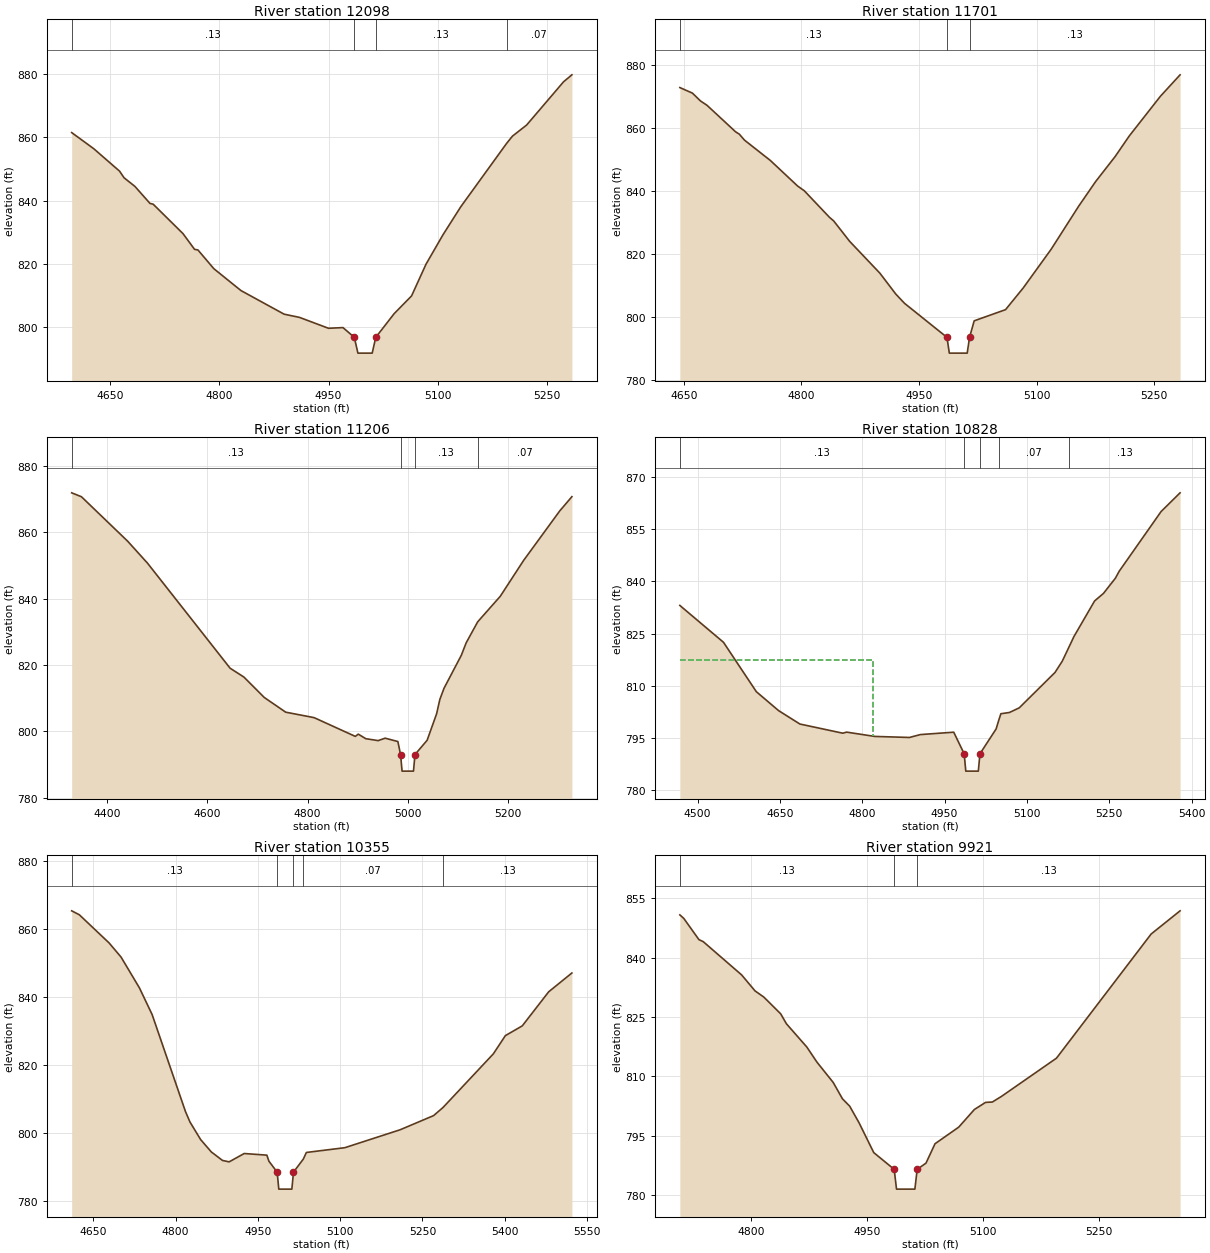
Type RM Length L Ch R = 1,12098,397,397,397
BEGIN DESCRIPTION:
Grassy Creek 26.0
END DESCRIPTION:
XS GIS Cut Line= 4
      1566019.58       924167.98      1565817.51       924056.84
      1565633.16       923880.07      1565618.01       923680.57
#Sta/Elev= 30
  4597.6  861.52  4627.8  856.43  4663.3  849.30  4669.4  847.22  4684.4  844.46
  4705.0  839.09  4709.4  838.83  4750.3  829.51  4766.1  824.54  4770.8  824.33
  4792.6  818.40  4829.8  811.47  4889.0  803.99  4910.1  802.97  4949.9  799.52
  4969.7  799.74  4985.3  796.65  4990.2  791.65  5009.8  791.65  5014.7  796.65
  5039.9  804.15  5063.8  809.78  5083.6  819.82  5106.8  829.11  5131.3  838.03
  5194.1  858.08  5202.2  860.40  5221.6  863.91  5272.3  877.62  5283.7  879.82
#Mann=4,-1,0
  4597.6    0.13       0  4985.3    0.05       0  5014.7    0.13       0
  5194.1    0.07       0
Bank Sta=4985.3,5014.7
XS Rating Curve= 0
Exp/Cntr=0.3,0.1

Type RM Length L Ch R = 1,11701,495,495,495
BEGIN DESCRIPTION:
Grassy Creek 25.0
END DESCRIPTION:
XS GIS Cut Line= 4
      1566244.29       923965.93      1566102.87       923791.68
      1565905.89       923632.59      1565761.94       923561.87
#Sta/Elev= 30
  4644.9  872.79  4660.9  871.04  4671.2  868.55  4679.5  867.18  4715.9  858.79
  4720.8  858.01  4727.2  856.16  4760.3  849.69  4795.2  841.56  4803.7  840.06
  4835.8  831.64  4841.0  830.55  4861.5  824.04  4900.0  813.96  4920.4  807.31
  4931.4  804.41  4985.6  793.61  4988.6  788.61  5011.4  788.61  5014.4  793.61
  5020.3  798.85  5060.3  802.39  5082.9  809.29  5118.4  821.51  5153.6  835.20
  5175.3  843.03  5200.0  850.90  5218.1  857.45  5257.8  870.03  5282.9  876.83
#Mann=3,-1,0
  4644.9    0.13       0  4985.6    0.05       0  5014.4    0.13       0
Bank Sta=4985.6,5014.4
XS Rating Curve= 0
Exp/Cntr=0.3,0.1

Type RM Length L Ch R = 1,11206,378,378,378
BEGIN DESCRIPTION:
Grassy Creek 24.0
END DESCRIPTION:
XS GIS Cut Line= 4
      1566517.02       923935.63      1566562.48       923622.48
      1566241.76       923248.74      1566196.30       923064.37
#Sta/Elev= 30
  4328.9  871.91  4348.4  870.73  4440.8  857.31  4480.3  850.71  4645.3  819.03
  4672.8  816.37  4713.5  810.21  4756.3  805.78  4812.9  804.14  4895.3  798.48
  4901.1  799.16  4916.2  797.79  4940.9  797.21  4954.8  797.94  4980.2  796.94
  4985.6  793.01  4988.6  788.01  5011.4  788.01  5014.4  793.01  5038.6  797.30
  5057.6  805.31  5064.0  809.60  5072.3  812.97  5106.9  822.93  5116.6  826.69
  5139.6  833.02  5184.7  840.72  5231.2  851.51  5303.4  866.45  5327.7  870.75
#Mann=4,-1,0
  4328.9    0.13       0  4985.6    0.05       0  5014.4    0.13       0
  5139.6    0.07       0
Bank Sta=4985.6,5014.4
XS Rating Curve= 0
Exp/Cntr=0.3,0.1

Type RM Length L Ch R = 1,10828,473,473,473
BEGIN DESCRIPTION:
Grassy Creek 23.0
END DESCRIPTION:
XS GIS Cut Line= 3
      1566829.26       923625.91      1566667.15       923171.99
      1566398.35       922837.13
#Sta/Elev= 30
  4467.6  833.08  4547.1  822.47  4607.0  808.24  4647.5  802.80  4686.3  798.94
  4764.5  796.30  4771.4  796.61  4822.7  795.37  4886.0  795.07  4905.8  795.90
  4966.6  796.59  4985.6  790.38  4988.6  785.38  5011.4  785.38  5014.4  790.38
  5043.9  797.54  5048.2  799.80  5052.5  801.90  5068.2  802.27  5085.9  803.59
  5151.2  813.80  5164.4  817.05  5176.1  820.94  5185.5  824.09  5223.3  834.38
  5239.4  836.54  5261.1  840.91  5268.1  842.93  5344.4  860.11  5379.0  865.50
#Mann=5,-1,0
  4467.6    0.13       0  4985.6    0.05       0  5014.4    0.13       0
  5048.2    0.07       0  5176.1    0.13       0
#XS Ineff=2,0
    0.00 4820.30  817.27               0
Permanent Ineff=
       F       F
Bank Sta=4985.6,5014.4
XS Rating Curve= 0
Exp/Cntr=0.3,0.1

Type RM Length L Ch R = 1,10355,434,434,434
BEGIN DESCRIPTION:
Grassy Creek 22.0
END DESCRIPTION:
XS GIS Cut Line= 5
      1567284.72       923188.12      1567186.23       923011.36
      1566878.14       922794.18      1566746.83       922733.57
      1566567.52       922675.48
#Sta/Elev= 30
  4610.3  865.34  4624.2  864.19  4678.6  855.90  4700.4  851.75  4733.9  842.70
  4757.0  834.89  4817.8  806.41  4826.0  803.33  4845.5  798.15  4865.1  794.50
  4885.4  792.02  4897.5  791.60  4925.0  794.05  4966.3  793.57  4970.1  791.79
  4985.1  788.59  4988.1  783.59  5011.9  783.59  5014.9  788.59  5032.8  792.41
  5038.4  794.36  5108.5  795.76  5209.3  801.02  5270.5  805.19  5287.8  807.60
  5379.5  823.34  5401.3  828.67  5432.2  831.55  5480.4  841.56  5522.7  847.08
#Mann=5,-1,0
  4610.3    0.13       0  4985.1    0.05       0  5014.9    0.13       0
  5032.8    0.07       0  5287.8    0.13       0
Bank Sta=4985.1,5014.9
XS Rating Curve= 0
Exp/Cntr=0.3,0.1

Type RM Length L Ch R = 1,9921,254,254,254
BEGIN DESCRIPTION:
Grassy Creek 21.0
END DESCRIPTION:
XS GIS Cut Line= 4
      1567418.57       922771.45      1567299.87       922642.66
      1567047.34       922529.02      1566880.65       922425.47
#Sta/Elev= 30
  4707.3  850.81  4712.3  849.95  4732.0  844.57  4737.6  844.05  4787.4  835.64
  4804.7  831.61  4816.1  830.05  4838.0  825.81  4845.4  823.30  4871.9  817.41
  4885.0  813.60  4906.0  808.48  4918.1  804.32  4927.4  802.48  4939.6  798.26
  4958.6  790.74  4985.1  786.51  4988.1  781.51  5011.9  781.51  5014.9  786.51
  5026.3  788.08  5038.0  792.98  5068.7  797.17  5089.0  801.63  5103.5  803.43
  5112.3  803.52  5124.1  804.94  5195.4  814.60  5318.1  845.98  5355.6  851.84
#Mann=3,-1,0
  4707.3    0.13       0  4985.1    0.05       0  5014.9    0.13       0
Bank Sta=4985.1,5014.9
XS Rating Curve= 0
Exp/Cntr=0.3,0.1

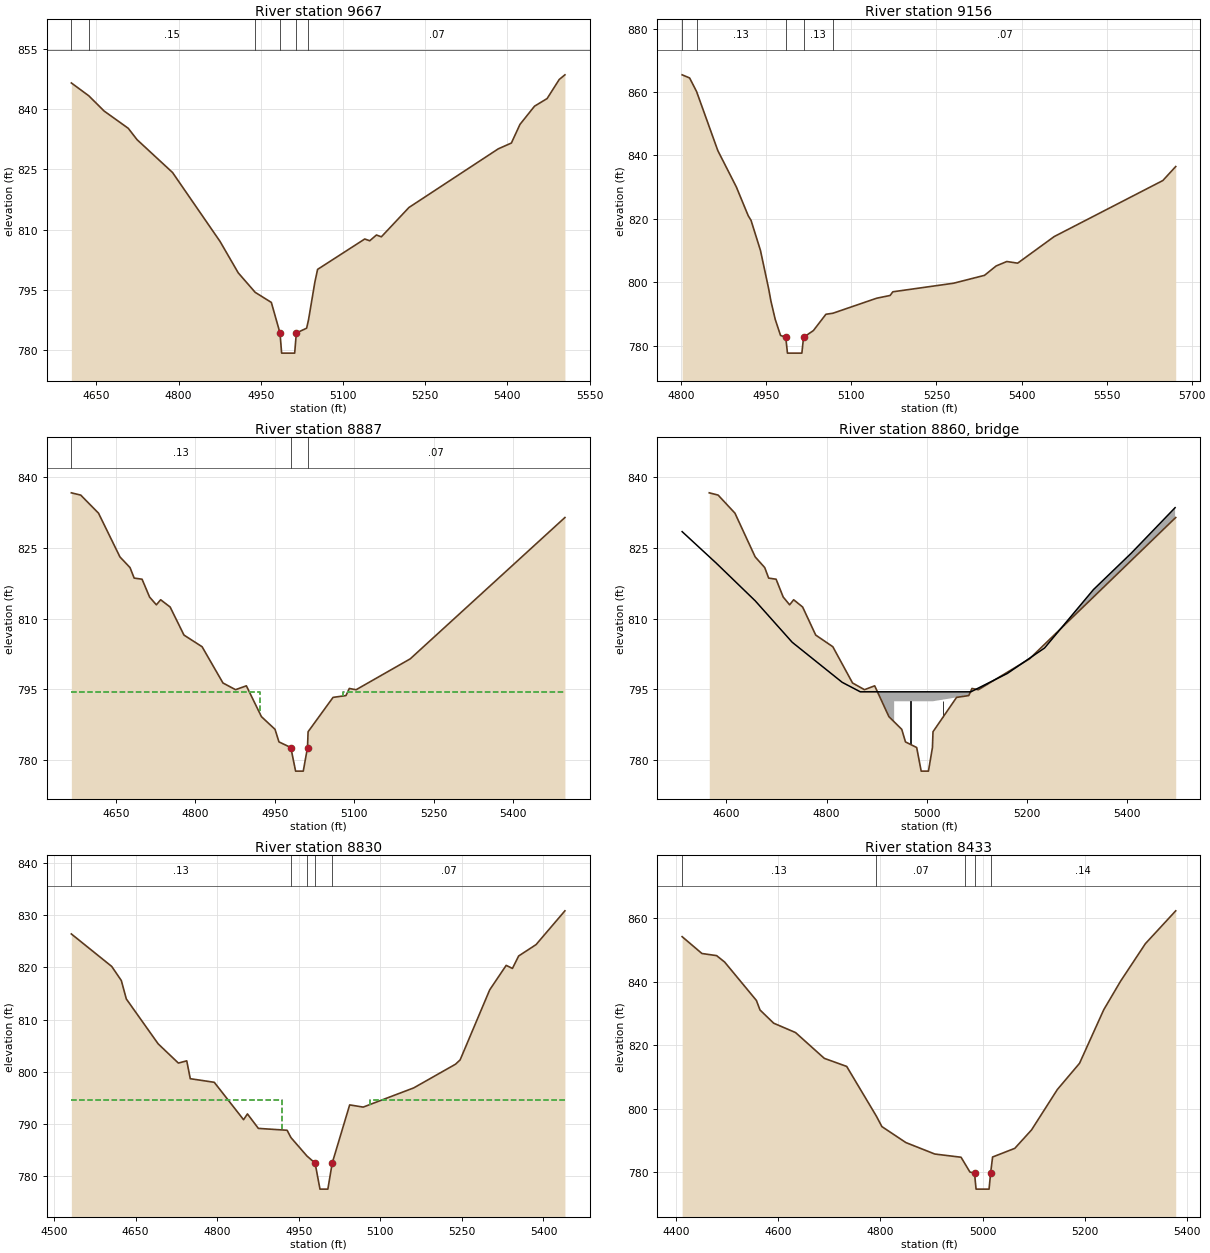
Type RM Length L Ch R = 1,9667,511,511,511
BEGIN DESCRIPTION:
Grassy Creek 20.0
END DESCRIPTION:
XS GIS Cut Line= 5
      1567575.15       922753.80      1567438.77       922508.81
      1567304.93       922357.30      1566989.26       922407.80
      1566890.73       922405.28
#Sta/Elev= 30
  4604.3  846.48  4636.2  843.28  4664.1  839.50  4708.2  835.20  4724.2  832.38
  4789.0  824.21  4875.7  807.07  4908.9  799.26  4939.8  794.42  4969.3  791.91
  4985.1  784.30  4988.1  779.30  5011.9  779.30  5014.9  784.30  5033.7  785.50
  5037.1  787.54  5048.7  796.91  5053.7  800.12  5139.8  807.68  5148.9  807.24
  5161.1  808.67  5170.1  808.22  5220.5  815.52  5383.5  830.10  5407.4  831.54
  5423.0  836.16  5449.6  840.70  5472.6  842.60  5494.7  847.34  5505.1  848.50
#Mann=6,-1,0
  4604.3    0.13       0  4636.2    0.15       0  4939.8    0.13       0
  4985.1    0.05       0  5014.9    0.13       0  5037.1    0.07       0
Bank Sta=4985.1,5014.9
XS Rating Curve= 0
Exp/Cntr=0.3,0.1

Type RM Length L Ch R = 1,9156,269,269,269
BEGIN DESCRIPTION:
Grassy Creek 19.0
END DESCRIPTION:
XS GIS Cut Line= 5
      1567587.74       921922.98      1567476.65       922223.45
      1567268.65       922354.21      1567067.31       922391.96
      1566968.48       922402.74
#Sta/Elev= 30
  4801.6  865.46  4814.8  864.47  4827.1  860.17  4864.5  841.55  4897.2  830.06
  4918.1  820.99  4923.1  819.52  4939.7  810.04  4954.4  797.72  4958.1  794.08
  4965.7  788.29  4975.1  783.20  4984.3  782.61  4987.3  777.61  5012.7  777.61
  5015.7  782.61  5033.0  784.72  5055.1  789.87  5067.6  790.21  5144.7  794.95
  5168.3  795.81  5173.1  796.97  5280.1  799.67  5334.7  802.16  5355.3  805.13
  5374.1  806.53  5393.2  806.01  5457.7  814.41  5649.2  832.09  5671.9  836.51
#Mann=5,-1,0
  4801.6    0.07       0  4827.1    0.13       0  4984.3    0.05       0
  5015.7    0.13       0  5067.6    0.07       0
Bank Sta=4984.3,5015.7
XS Rating Curve= 0
Exp/Cntr=0.5,0.3

Type RM Length L Ch R = 1,8887,57,57,57
BEGIN DESCRIPTION:
Hauser Rd (GC) us
END DESCRIPTION:
XS GIS Cut Line= 6
      1567265.04       921645.96      1567239.88       921737.60
      1567250.67       922293.08      1567207.53       922345.22
      1567135.62       922375.78      1567002.56       922397.35
#Sta/Elev= 30
  4565.7  836.65  4583.4  836.17  4617.0  832.34  4657.4  823.08  4676.5  820.81
  4684.3  818.59  4699.2  818.35  4713.4  814.57  4726.2  812.93  4734.3  814.00
  4752.2  812.46  4778.3  806.52  4812.5  804.05  4851.9  796.37  4875.7  794.95
  4896.1  795.77  4924.5  789.24  4950.2  786.55  4957.6  783.89  4980.0  782.70
  4989.0  777.70  5003.5  777.70  5011.5  782.70  5012.6  786.04  5059.7  793.32
  5084.1  793.70  5090.4  795.21  5103.2  794.94  5205.4  801.48  5497.4  831.42
#Mann=3,-1,0
  4565.7    0.13       0  4980.0    0.05       0  5011.5    0.07       0
#XS Ineff=2,0
    0.00 4922.00  794.50 5078.00    0.00  794.50
Permanent Ineff=
       F       F
Bank Sta=4980,5011.5
XS Rating Curve= 0
Exp/Cntr=0.5,0.3

Type RM Length L Ch R =3,8860,,,
BEGIN DESCRIPTION:
Hauser Rd (GC) TOR
Structure ID: LDS_GC_02
Approximate Survey Structure
END DESCRIPTION:
Bridge Culvert--1,0,-1,-1,0
Deck Dist Width WeirC Skew NumUp NumDn MinLoCord MaxHiCord MaxSubmerge Is_Ogee
13,28,3,,16,16,,,0.95,0,1,1,,,
  4511.5  4579.8  4657.6  4731.4  4831.2  4867.4  4935.0  4935.0  5065.0  5065.0
  5088.3  5160.9  5235.4  5333.2  5408.6  5496.2
  828.43  821.74  813.76  804.99  796.51  794.50  794.50  794.50  794.50  794.50
  794.50  798.38  803.78  816.17  823.87  833.51
  757.70  757.70  757.70  757.70  757.70  757.70  757.70  792.50  792.50  757.70
  757.70  757.70  757.70  757.70  757.70  757.70
  4511.5  4579.8  4657.6  4731.4  4831.2  4867.4  4935.0  4935.0  5065.0  5065.0
  5088.3  5160.9  5235.4  5333.2  5408.6  5496.2
  828.43  821.74  813.76  804.99  796.51  794.50  794.50  794.50  794.50  794.50
  794.50  798.38  803.78  816.17  823.87  833.51
  757.70  757.70  757.70  757.70  757.70  757.70  757.70  792.50  792.50  757.70
  757.70  757.70  757.70  757.70  757.70  757.70
Pier Skew, UpSta & Num, DnSta & Num=,4967.5,2,4967.5,2,0,0,0,0,0
       1       1
  780.71  792.50
       1       1
  784.23  792.50
Pier Skew, UpSta & Num, DnSta & Num=,5032.5,2,5032.5,2,0,0,0,0,0
       1       1
  787.56  792.50
       1       1
  785.48  792.50
Abutment Skew #Up #Dn=,2,2
  4935.0  4952.5
  792.50  785.72
  4935.0  4952.5
  792.50  783.76
Abutment Skew #Up #Dn=,2,2
  5047.5  5065.0
  791.34  792.50
  5047.5  5065.0
  793.23  792.50
BR Coef=1,1,0,1.25,0,,,0.8,0,2,0,
WSPro=,,,, 1 ,,,, 0 ,,,, 0 ,,,,-1 ,-1 ,-1 , 0 , 0 , 0 , 0 , 0
BC Design=,,0,,0,,,,,,

Type RM Length L Ch R = 1,8830,397,397,397
BEGIN DESCRIPTION:
Hauser Rd (GC) ds
END DESCRIPTION:
XS GIS Cut Line= 6
      1567223.69       921608.20      1567173.37       921692.66
      1567203.93       922127.70      1567202.13       922269.71
      1567139.21       922338.03      1567006.19       922375.78
#Sta/Elev= 30
  4531.8  826.44  4606.0  820.21  4623.7  817.50  4632.9  813.96  4691.4  805.35
  4728.6  801.65  4744.0  802.08  4750.5  798.65  4794.6  797.96  4848.5  790.78
  4855.6  791.89  4875.7  789.11  4928.6  788.75  4935.5  787.36  4964.9  783.82
  4980.0  782.45  4989.0  777.45  5003.5  777.45  5011.5  782.45  5043.6  793.62
  5068.5  793.20  5161.5  796.89  5238.2  801.43  5246.7  802.26  5301.1  815.71
  5331.4  820.41  5342.9  819.82  5354.3  822.21  5386.3  824.39  5439.4  830.88
#Mann=5,-1,0
  4531.8    0.13       0  4935.5    0.07       0  4964.9    0.14       0
  4980.0    0.05       0  5011.5    0.07       0
#XS Ineff=2,0
    0.00 4919.00  794.50 5081.00    0.00  794.50
Permanent Ineff=
       F       F
Bank Sta=4980,5011.5
XS Rating Curve= 0
Exp/Cntr=0.5,0.3

Type RM Length L Ch R = 1,8433,498,498,498
BEGIN DESCRIPTION:
Grassy Creek 18.0
END DESCRIPTION:
XS GIS Cut Line= 4
      1567176.11       921415.38      1566953.90       921736.06
      1566756.93       922029.00      1566683.69       922238.63
#Sta/Elev= 30
  4412.5  854.21  4451.2  848.90  4479.9  848.23  4495.6  846.21  4557.7  834.10
  4564.8  831.08  4591.5  826.92  4634.3  823.96  4690.5  815.83  4734.3  813.28
  4792.4  797.58  4803.1  794.31  4850.1  789.26  4906.6  785.65  4957.9  784.64
  4966.4  782.36  4975.2  779.99  4984.3  779.58  4987.3  774.58  5012.7  774.58
  5015.7  779.58  5019.6  784.71  5063.0  787.44  5095.7  793.24  5146.2  805.99
  5189.6  814.26  5236.9  831.14  5269.8  840.15  5318.4  852.00  5377.7  862.36
#Mann=5,-1,0
  4412.5    0.13       0  4792.4    0.07       0  4966.4    0.14       0
  4984.3    0.05       0  5015.7    0.14       0
Bank Sta=4984.3,5015.7
XS Rating Curve= 0
Exp/Cntr=0.3,0.1