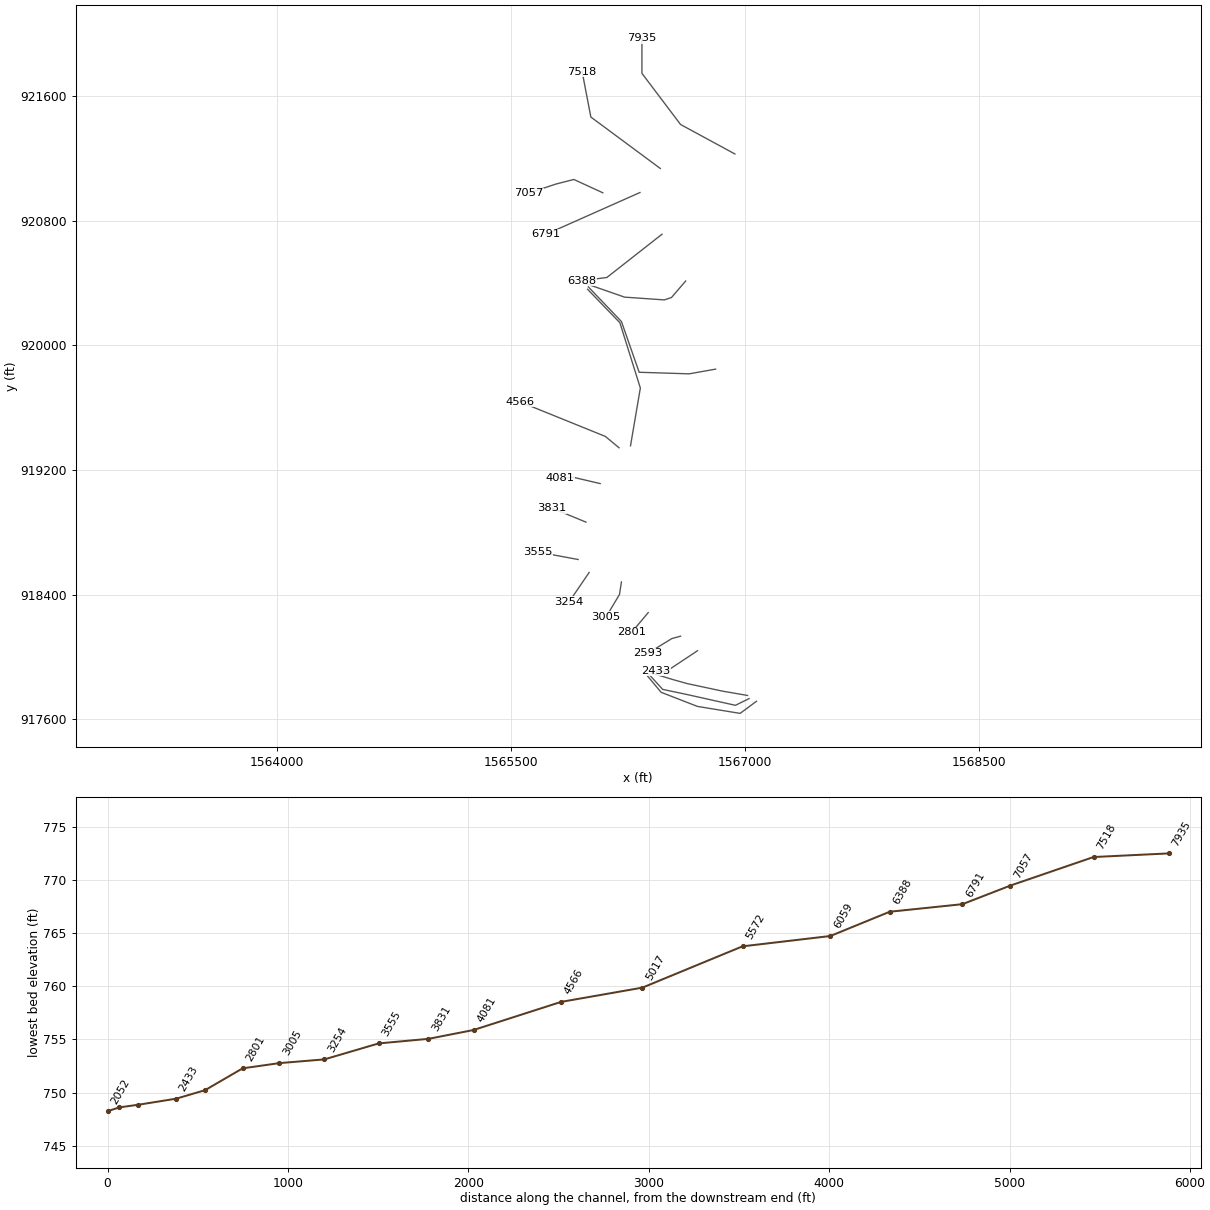
HEC-RAS study Grassy Creek.prj: Grassy Creek Limited Detail Study

--- Grassy Creek.g01 (geometry) --- (continued)

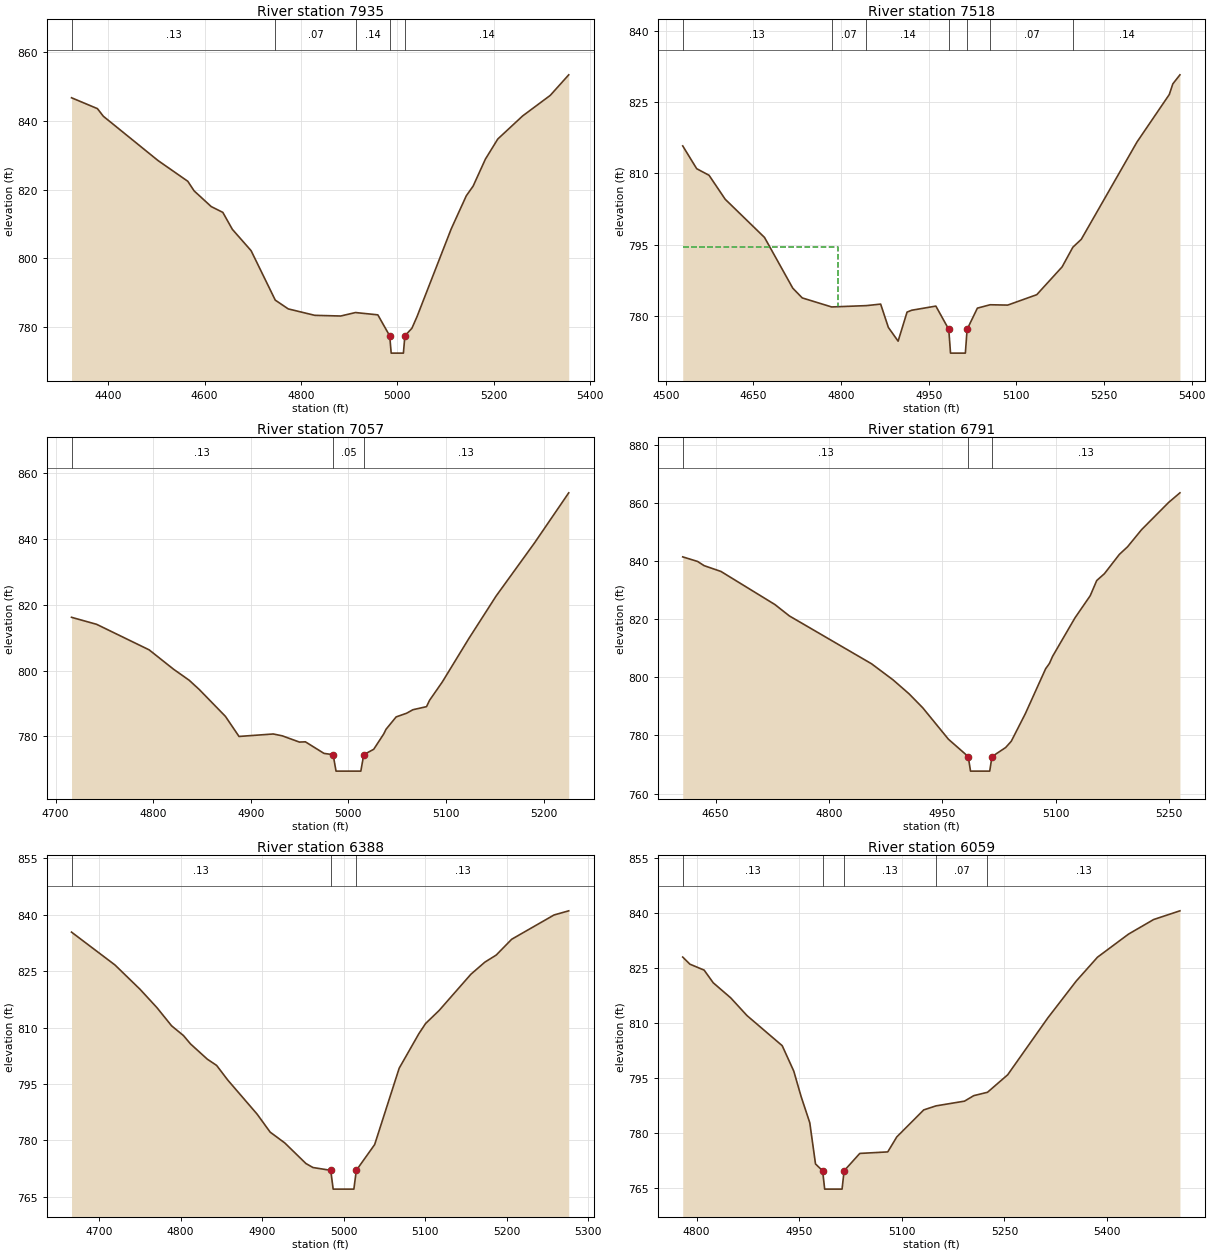
Type RM Length L Ch R = 1,7935,417,417,417
BEGIN DESCRIPTION:
Grassy Creek 17.0
END DESCRIPTION:
XS GIS Cut Line= 4
      1566936.25       921228.46      1566587.73       921417.87
      1566340.25       921746.17      1566340.25       921970.88
#Sta/Elev= 30
  4323.5  846.73  4377.3  843.57  4389.6  841.35  4503.0  828.49  4565.0  822.44
  4578.0  819.67  4613.6  815.09  4637.7  813.40  4657.5  808.47  4696.4  802.27
  4746.6  787.89  4773.5  785.34  4828.6  783.47  4882.4  783.27  4913.2  784.28
  4959.6  783.61  4984.3  777.48  4987.3  772.48  5012.7  772.48  5015.7  777.48
  5030.4  779.73  5041.1  783.14  5112.0  808.62  5143.3  818.23  5157.5  821.05
  5183.0  828.90  5208.7  834.74  5260.3  841.45  5317.6  847.42  5356.0  853.40
#Mann=5,-1,0
  4323.5    0.13       0  4746.6    0.07       0  4913.2    0.14       0
  4984.3    0.05       0  5015.7    0.14       0
Bank Sta=4984.3,5015.7
XS Rating Curve= 0
Exp/Cntr=0.3,0.1

Type RM Length L Ch R = 1,7518,461,461,461
BEGIN DESCRIPTION:
Grassy Creek 16.5
END DESCRIPTION:
XS GIS Cut Line= 3
      1566457.88       921135.50      1566012.87       921465.57
      1565956.88       921757.30
#Sta/Elev= 30
  4528.9  815.76  4552.8  810.96  4574.0  809.57  4601.6  804.53  4668.9  796.49
  4717.3  785.81  4733.5  783.76  4783.8  781.86  4843.4  782.14  4867.7  782.46
  4880.9  777.55  4897.6  774.66  4912.9  780.78  4921.0  781.17  4962.2  782.04
  4984.3  777.14  4987.3  772.14  5012.7  772.14  5015.7  777.14  5033.3  781.61
  5055.1  782.32  5085.2  782.25  5134.9  784.44  5178.3  790.29  5196.7  794.43
  5211.1  796.09  5306.5  816.58  5361.8  826.58  5367.8  828.81  5380.0  830.72
#Mann=7,-1,0
  4528.9    0.13       0  4783.8    0.07       0  4843.4    0.14       0
  4984.3    0.05       0  5015.7    0.14       0  5055.1    0.07       0
  5196.7    0.14       0
#XS Ineff=2,0
    0.00 4795.10  794.39               0
Permanent Ineff=
       F       F
Bank Sta=4984.3,5015.7
XS Rating Curve= 0
Exp/Cntr=0.3,0.1

Type RM Length L Ch R = 1,7057,266,266,266
BEGIN DESCRIPTION:
Grassy Creek 16.0
END DESCRIPTION:
XS GIS Cut Line= 4
      1566089.49       920979.29      1565903.83       921064.75
      1565788.89       921035.28      1565612.10       920976.35
#Sta/Elev= 30
  4716.3  816.17  4742.0  814.04  4795.8  806.29  4820.9  800.39  4836.8  797.07
  4847.2  794.24  4874.0  786.08  4887.9  779.99  4923.0  780.74  4932.3  780.17
  4949.8  778.28  4955.9  778.36  4975.0  774.84  4984.3  774.46  4987.3  769.46
  5012.7  769.46  5015.7  774.46  5025.9  776.09  5036.2  780.77  5038.5  782.16
  5048.9  785.93  5059.6  787.04  5066.0  788.10  5080.0  789.04  5083.1  790.96
  5096.2  796.55  5123.4  809.74  5151.3  822.63  5190.5  838.70  5225.7  853.97
#Mann=3,-1,0
  4716.3    0.13       0  4984.3    0.05       0  5015.7    0.13       0
Bank Sta=4984.3,5015.7
XS Rating Curve= 0
Exp/Cntr=0.3,0.1

Type RM Length L Ch R = 1,6791,403,403,403
BEGIN DESCRIPTION:
Grassy Creek 15.0
END DESCRIPTION:
XS GIS Cut Line= 2
      1566327.60       920980.98      1565726.61       920713.31
#Sta/Elev= 30
  4606.5  841.50  4626.2  839.92  4634.8  838.48  4657.1  836.48  4728.5  825.08
  4747.7  821.15  4856.4  804.67  4884.9  799.12  4906.0  794.33  4924.1  789.52
  4958.1  778.69  4984.3  772.71  4987.3  767.71  5012.7  767.71  5015.7  772.71
  5033.8  775.84  5041.2  777.99  5059.8  787.48  5086.7  802.97  5091.7  804.79
  5095.9  807.25  5125.5  820.49  5145.7  828.13  5154.3  833.35  5164.5  835.72
  5184.2  842.34  5195.1  844.98  5213.6  850.86  5249.4  860.24  5264.4  863.56
#Mann=3,-1,0
  4606.5    0.13       0  4984.3    0.05       0  5015.7    0.13       0
Bank Sta=4984.3,5015.7
XS Rating Curve= 0
Exp/Cntr=0.3,0.1

Type RM Length L Ch R = 1,6388,329,329,329
BEGIN DESCRIPTION:
Grassy Creek 14.0
END DESCRIPTION:
XS GIS Cut Line= 3
      1566469.06       920713.32      1566115.50       920435.52
      1565956.42       920415.32
#Sta/Elev= 30
  4666.3  835.40  4719.6  826.66  4750.4  820.18  4771.1  815.30  4789.1  810.46
  4803.7  807.86  4812.3  805.64  4833.0  801.57  4844.3  799.93  4858.2  795.97
  4894.0  786.96  4910.0  782.17  4927.9  779.30  4953.9  773.81  4962.5  772.75
  4984.3  772.00  4987.3  767.00  5012.7  767.00  5015.7  772.00  5038.2  778.86
  5068.3  799.19  5092.5  808.39  5100.7  811.08  5117.3  814.55  5156.3  824.20
  5173.4  827.41  5187.3  829.29  5206.3  833.50  5258.3  839.97  5276.3  841.07
#Mann=3,-1,0
  4666.3    0.13       0  4984.3    0.05       0  5015.7    0.13       0
Bank Sta=4984.3,5015.7
XS Rating Curve= 0
Exp/Cntr=0.3,0.1

Type RM Length L Ch R = 1,6059,487,487,487
BEGIN DESCRIPTION:
Grassy Creek 13.0
END DESCRIPTION:
XS GIS Cut Line= 5
      1566620.54       920412.77      1566529.65       920306.73
      1566484.19       920291.58      1566229.14       920309.26
      1565961.42       920402.70
#Sta/Elev= 30
  4779.8  828.05  4790.3  826.11  4811.1  824.49  4824.4  821.03  4850.0  816.91
  4873.7  812.09  4925.2  803.87  4942.1  796.94  4952.8  790.02  4965.5  782.85
  4973.9  771.59  4984.3  769.72  4987.3  764.72  5012.7  764.72  5015.7  769.72
  5038.6  774.46  5079.5  774.88  5092.7  778.97  5132.1  786.34  5150.0  787.44
  5191.7  788.73  5205.2  790.23  5225.3  791.15  5254.8  795.92  5313.3  811.40
  5355.0  821.50  5386.1  828.02  5431.4  834.31  5468.2  838.30  5506.6  840.67
#Mann=5,-1,0
  4779.8    0.13       0  4984.3    0.05       0  5015.7    0.13       0
  5150.0    0.07       0  5225.3    0.13       0
Bank Sta=4984.3,5015.7
XS Rating Curve= 0
Exp/Cntr=0.3,0.1

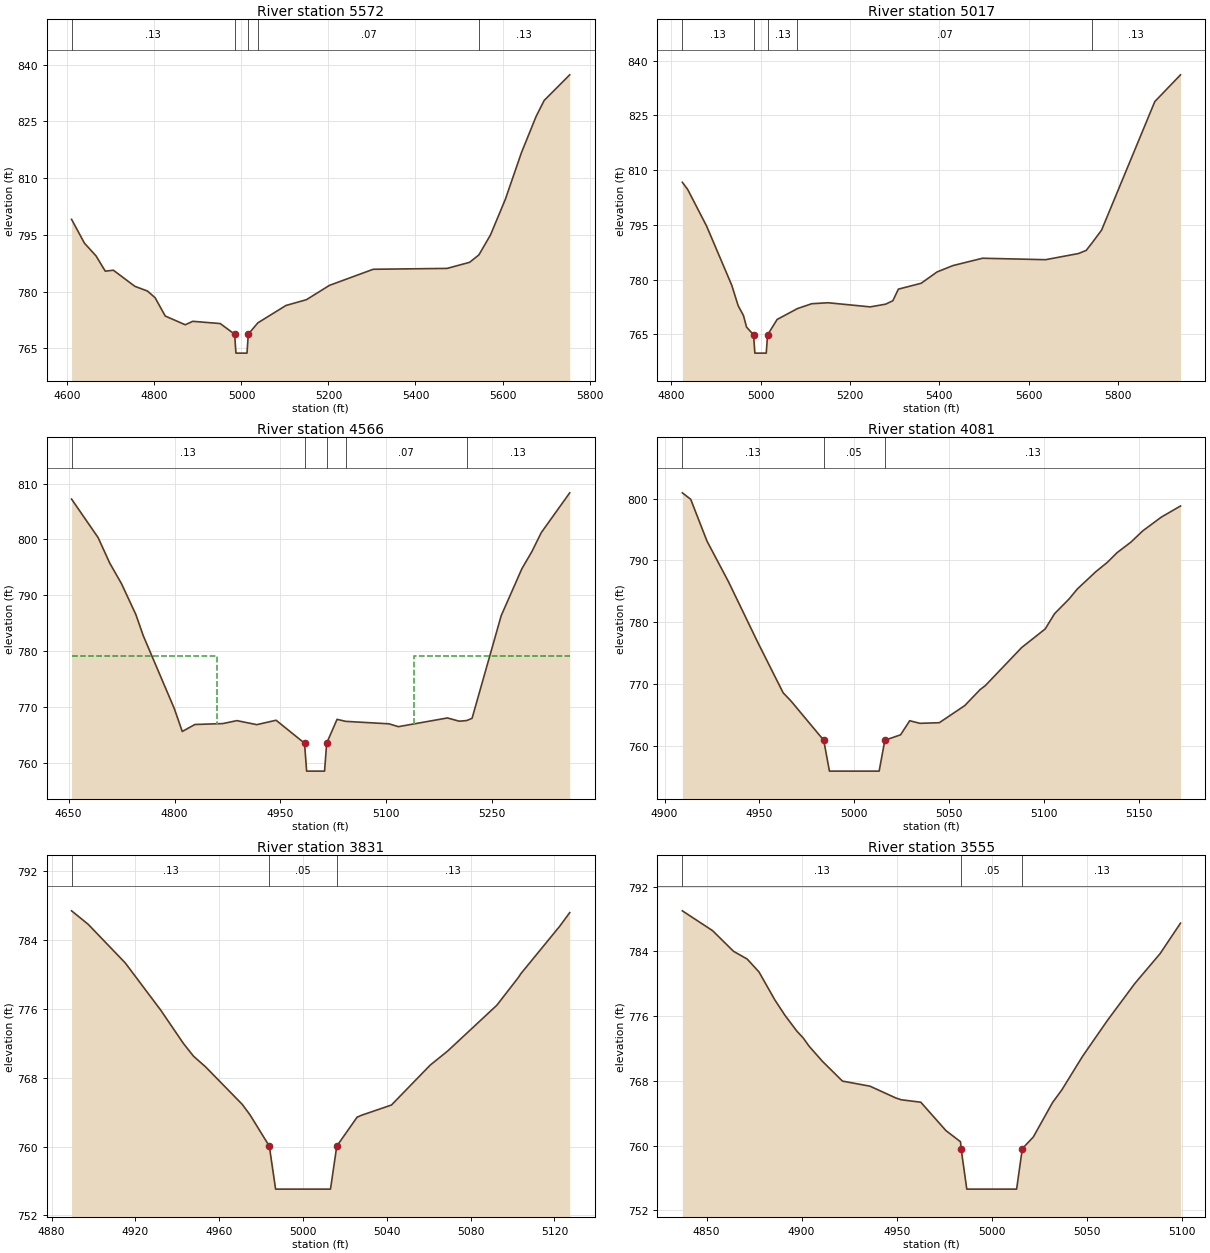
Type RM Length L Ch R = 1,5572,555,555,555
BEGIN DESCRIPTION:
Grassy Creek 12.0
END DESCRIPTION:
XS GIS Cut Line= 5
      1566812.47       919847.12      1566643.29       919816.82
      1566322.57       919826.92      1566208.93       920152.68
      1565996.80       920374.92
#Sta/Elev= 30
  4609.5  799.12  4639.1  792.82  4665.7  789.46  4687.0  785.42  4705.6  785.67
  4755.0  781.41  4784.0  780.16  4801.5  778.40  4824.8  773.56  4870.8  771.25
  4888.0  772.16  4951.2  771.57  4984.3  768.75  4987.3  763.75  5012.7  763.75
  5015.7  768.75  5037.7  771.76  5102.3  776.35  5149.4  777.88  5202.3  781.67
  5302.8  785.92  5472.6  786.15  5524.4  787.76  5545.8  789.73  5572.4  795.00
  5606.6  804.44  5643.4  816.71  5677.2  826.32  5695.8  830.56  5754.5  837.33
#Mann=5,-1,0
  4609.5    0.13       0  4984.3    0.05       0  5015.7    0.13       0
  5037.7    0.07       0  5545.8    0.13       0
Bank Sta=4984.3,5015.7
XS Rating Curve= 0
Exp/Cntr=0.3,0.1

Type RM Length L Ch R = 1,5017,451,451,451
BEGIN DESCRIPTION:
Grassy Creek 11.0
END DESCRIPTION:
XS GIS Cut Line= 4
      1566267.01       919354.63      1566330.15       919725.90
      1566198.83       920145.11      1565991.79       920359.73
#Sta/Elev= 30
  4825.1  806.67  4836.9  804.74  4879.3  794.68  4935.6  778.47  4949.9  772.87
  4961.8  770.16  4968.6  767.02  4984.3  764.87  4987.3  759.87  5012.7  759.87
  5015.7  764.87  5037.1  769.10  5082.6  772.08  5114.5  773.41  5151.3  773.67
  5245.3  772.54  5279.9  773.29  5295.9  774.23  5308.2  777.40  5359.1  779.01
  5394.7  782.11  5430.0  783.85  5496.5  785.87  5637.3  785.47  5711.1  787.16
  5728.4  788.03  5741.2  790.04  5762.7  793.58  5881.7  828.79  5939.2  836.12
#Mann=5,-1,0
  4825.1    0.13       0  4984.3    0.05       0  5015.7    0.13       0
  5082.6    0.07       0  5741.2    0.13       0
Bank Sta=4984.3,5015.7
XS Rating Curve= 0
Exp/Cntr=0.3,0.1

Type RM Length L Ch R = 1,4566,485,485,485
BEGIN DESCRIPTION:
Grassy Creek 10.0
END DESCRIPTION:
XS GIS Cut Line= 3
      1566193.76       919342.08      1566105.39       919415.29
      1565557.39       919637.52
#Sta/Elev= 30
  4654.1  807.23  4691.7  800.34  4708.3  795.75  4724.8  792.10  4745.2  786.57
  4755.8  782.75  4799.7  769.73  4811.0  765.63  4828.9  766.88  4868.4  767.04
  4888.4  767.57  4916.7  766.85  4944.0  767.64  4984.3  763.53  4987.3  758.53
  5012.7  758.53  5015.7  763.53  5030.4  767.80  5042.7  767.44  5104.0  767.00
  5117.4  766.49  5186.9  768.05  5203.6  767.47  5214.1  767.58  5221.8  767.99
  5263.1  786.37  5292.5  794.79  5306.3  797.77  5319.9  801.23  5360.2  808.35
#Mann=5,-1,0
  4654.1    0.13       0  4984.3    0.05       0  5015.7    0.13       0
  5042.7    0.07       0  5214.1    0.13       0
#XS Ineff=2,0
    0.00 4860.60  779.08 5139.40    0.00  779.08
Permanent Ineff=
       F       F
Bank Sta=4984.3,5015.7
XS Rating Curve= 0
Exp/Cntr=0.3,0.1

Type RM Length L Ch R = 1,4081,250,250,250
BEGIN DESCRIPTION:
Grassy Creek 9.0
END DESCRIPTION:
XS GIS Cut Line= 3
      1566072.53       919112.26      1565900.84       919152.66
      1565815.06       919145.09
#Sta/Elev= 30
  4909.4  800.95  4913.8  799.90  4922.4  793.12  4933.8  786.50  4949.3  776.64
  4962.5  768.58  4966.6  767.26  4983.9  760.89  4986.9  755.89  5013.1  755.89
  5016.1  760.89  5024.4  761.77  5029.2  764.05  5034.6  763.63  5044.8  763.73
  5058.2  766.50  5066.4  769.12  5069.0  769.72  5088.2  775.90  5100.6  778.91
  5105.5  781.37  5113.2  783.77  5117.5  785.37  5127.2  788.16  5133.4  789.71
  5138.5  791.27  5145.7  792.95  5152.0  794.79  5161.8  797.02  5171.9  798.82
#Mann=3,-1,0
  4909.4    0.13       0  4983.9    0.05       0  5016.1    0.13       0
Bank Sta=4983.9,5016.1
XS Rating Curve= 0
Exp/Cntr=0.3,0.1

Type RM Length L Ch R = 1,3831,276,276,276
BEGIN DESCRIPTION:
Grassy Creek 8.0
END DESCRIPTION:
XS GIS Cut Line= 2
      1565981.66       918864.76      1565761.93       918955.69
#Sta/Elev= 24
  4889.5  787.42  4897.4  785.86  4915.1  781.37  4932.1  775.86  4942.8  772.03
  4947.7  770.52  4953.5  769.27  4971.0  764.91  4974.7  763.69  4983.9  760.06
  4986.9  755.06  5013.1  755.06  5016.1  760.06  5025.9  763.46  5026.3  763.47
  5027.8  763.64  5042.2  764.84  5060.7  769.48  5069.0  771.11  5092.5  776.44
  5103.0  779.74  5103.9  780.09  5122.4  785.59  5127.3  787.21
#Mann=3,-1,0
  4889.5    0.13       0  4983.9    0.05       0  5016.1    0.13       0
Bank Sta=4983.9,5016.1
XS Rating Curve= 0
Exp/Cntr=0.3,0.1

Type RM Length L Ch R = 1,3555,301,301,301
BEGIN DESCRIPTION:
Grassy Creek 7.0
END DESCRIPTION:
XS GIS Cut Line= 2
      1565931.16       918624.86      1565673.59       918672.84
#Sta/Elev= 30
  4837.3  789.02  4853.2  786.57  4864.2  784.02  4871.4  783.06  4877.6  781.47
  4885.9  778.03  4891.2  776.13  4897.5  774.16  4901.0  773.27  4903.9  772.31
  4910.9  770.44  4921.5  767.98  4936.0  767.35  4949.6  765.89  4952.5  765.67
  4962.7  765.37  4975.9  761.87  4983.6  760.48  4983.9  759.63  4986.9  754.63
  5013.1  754.63  5016.1  759.63  5021.9  761.08  5032.0  765.33  5036.9  766.90
  5047.8  771.05  5060.9  775.49  5075.3  780.05  5088.6  783.74  5099.3  787.50
#Mann=3,-1,0
  4837.3    0.13       0  4983.9    0.05       0  5016.1    0.13       0
Bank Sta=4983.9,5016.1
XS Rating Curve= 0
Exp/Cntr=0.3,0.1

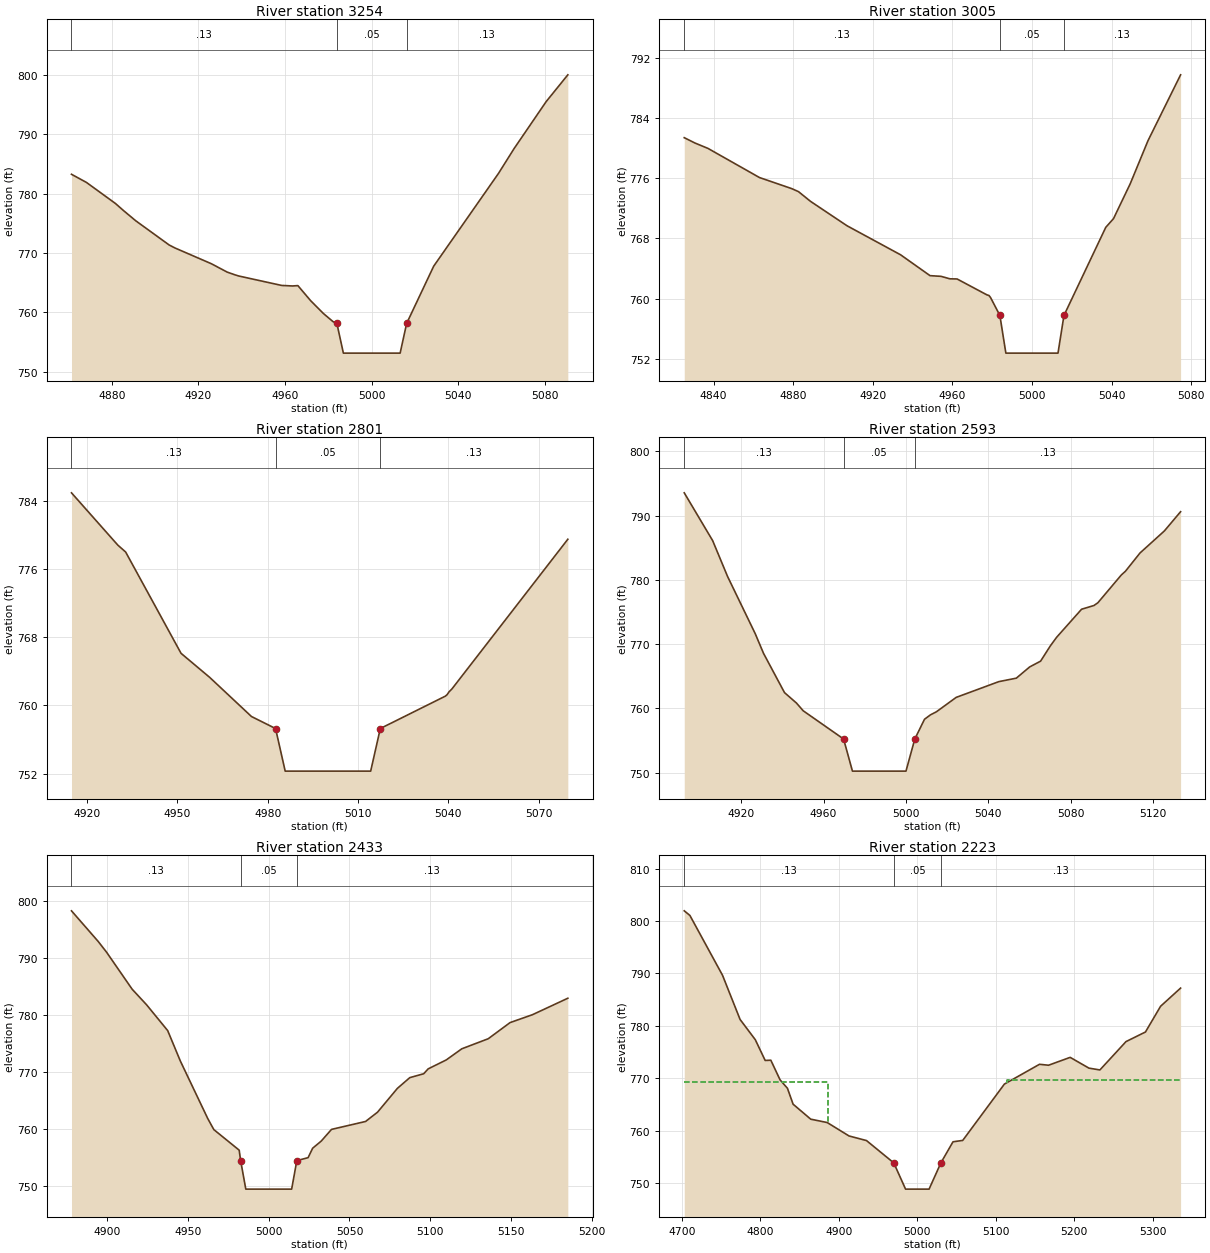
Type RM Length L Ch R = 1,3254,249,249,249
BEGIN DESCRIPTION:
Grassy Creek 6.0
END DESCRIPTION:
XS GIS Cut Line= 2
      1566001.86       918541.54      1565873.04       918352.09
#Sta/Elev= 26
  4861.4  783.25  4868.3  781.88  4881.7  778.33  4885.5  777.11  4891.1  775.41
  4906.5  771.34  4909.1  770.85  4926.0  768.18  4933.3  766.77  4936.9  766.31
  4938.6  766.12  4958.4  764.53  4963.4  764.44  4965.9  764.50  4971.8  761.96
  4977.6  759.83  4982.1  758.44  4983.9  758.13  4986.9  753.13  5013.1  753.13
  5016.1  758.13  5028.6  767.78  5058.5  783.40  5065.7  787.58  5080.5  795.49
  5090.5  800.00
#Mann=3,-1,0
  4861.4    0.13       0  4983.9    0.05       0  5016.1    0.13       0
Bank Sta=4983.9,5016.1
XS Rating Curve= 0
Exp/Cntr=0.3,0.1

Type RM Length L Ch R = 1,3005,204,204,204
BEGIN DESCRIPTION:
Grassy Creek 5.0
END DESCRIPTION:
XS GIS Cut Line= 3
      1566208.93       918480.92      1566196.31       918400.11
      1566110.44       918256.16
#Sta/Elev= 25
  4825.3  781.37  4830.6  780.67  4837.2  779.95  4863.1  776.08  4879.3  774.61
  4882.7  774.21  4888.8  772.91  4907.1  769.68  4934.0  765.83  4948.8  763.06
  4954.3  762.97  4958.8  762.64  4962.4  762.62  4977.4  760.51  4978.4  760.43
  4979.2  760.16  4983.9  757.78  4986.9  752.78  5013.1  752.78  5016.1  757.78
  5037.1  769.47  5041.0  770.63  5049.4  775.26  5058.3  780.96  5074.7  789.71
#Mann=3,-1,0
  4825.3    0.13       0  4983.9    0.05       0  5016.1    0.13       0
Bank Sta=4983.9,5016.1
XS Rating Curve= 0
Exp/Cntr=0.3,0.1

Type RM Length L Ch R = 1,2801,208,208,208
BEGIN DESCRIPTION:
Grassy Creek 4.0
END DESCRIPTION:
XS GIS Cut Line= 2
      1566380.66       918283.95      1566274.60       918157.68
#Sta/Elev= 15
  4914.8  784.96  4930.2  778.82  4932.8  778.01  4951.2  766.12  4960.7  763.30
  4974.6  758.70  4982.6  757.29  4985.8  752.29  5014.2  752.29  5017.4  757.29
  5039.0  761.09  5039.6  761.27  5040.2  761.58  5041.2  761.94  5079.7  779.51
#Mann=3,-1,0
  4914.8    0.13       0  4982.6    0.05       0  5017.4    0.13       0
Bank Sta=4982.6,5017.4
XS Rating Curve= 0
Exp/Cntr=0.3,0.1

Type RM Length L Ch R = 1,2593,160,160,160
BEGIN DESCRIPTION:
Grassy Creek 3.0
END DESCRIPTION:
XS GIS Cut Line= 3
      1566587.71       918132.42      1566532.17       918117.27
      1566375.70       918021.36
#Sta/Elev= 30
  4892.3  793.56  4906.1  786.12  4913.3  780.57  4926.8  771.62  4930.8  768.58
  4941.0  762.46  4946.8  760.84  4950.1  759.63  4969.7  755.24  4974.0  750.24
  5000.0  750.24  5004.3  755.24  5009.0  758.31  5011.9  759.00  5014.8  759.48
  5024.4  761.72  5045.1  764.17  5053.6  764.71  5060.1  766.46  5065.4  767.36
  5070.2  769.77  5073.2  771.08  5085.3  775.44  5091.3  776.02  5093.2  776.44
  5104.6  780.77  5106.6  781.35  5113.7  784.20  5125.5  787.62  5133.4  790.62
#Mann=3,-1,0
  4892.3    0.13       0  4969.7    0.05       0  5004.3    0.13       0
Bank Sta=4969.7,5004.3
XS Rating Curve= 0
Exp/Cntr=0.3,0.1

Type RM Length L Ch R = 1,2433,210,210,210
BEGIN DESCRIPTION:
Grassy Creek 2.0
END DESCRIPTION:
XS GIS Cut Line= 3
      1566696.28       918038.96      1566493.03       917903.88
      1566429.89       917910.20
#Sta/Elev= 30
  4877.8  798.31  4894.3  792.95  4899.5  791.06  4915.4  784.54  4924.3  781.82
  4937.4  777.28  4945.3  771.90  4962.2  761.85  4966.0  759.89  4981.7  756.28
  4982.6  754.44  4985.8  749.44  5014.2  749.44  5017.4  754.44  5024.4  754.97
  5027.2  756.62  5032.5  757.87  5038.9  759.93  5060.0  761.32  5067.4  762.95
  5079.7  767.13  5087.4  769.02  5096.0  769.70  5098.8  770.56  5110.0  772.13
  5119.6  774.08  5136.0  775.85  5149.5  778.68  5163.4  780.07  5185.3  782.96
#Mann=3,-1,0
  4877.8    0.13       0  4982.6    0.05       0  5017.4    0.13       0
Bank Sta=4982.6,5017.4
XS Rating Curve= 0
Exp/Cntr=0.5,0.3

Type RM Length L Ch R = 1,2223,106,106,106
BEGIN DESCRIPTION:
Railroad (GC) us
END DESCRIPTION:
XS GIS Cut Line= 5
      1567017.19       917751.97      1566858.96       917779.30
      1566630.29       917828.20      1566538.25       917854.09
      1566401.60       917895.80
#Sta/Elev= 30
  4702.8  801.95  4710.0  801.07  4751.6  789.66  4774.0  781.23  4793.4  777.37
  4806.0  773.41  4813.2  773.46  4825.0  769.71  4834.4  768.10  4841.6  765.07
  4864.1  762.21  4885.1  761.57  4912.9  759.01  4935.2  758.13  4970.0  753.87
  4985.0  748.87  5015.0  748.87  5030.0  753.87  5045.5  757.90  5057.9  758.16
  5111.0  768.90  5155.8  772.68  5167.3  772.50  5194.9  774.00  5218.8  771.95
  5232.8  771.60  5266.1  777.01  5290.9  778.84  5310.2  783.75  5335.7  787.21
#Mann=3,-1,0
  4702.8    0.13       0  4970.0    0.05       0  5030.0    0.13       0
#XS Ineff=2,0
    0.00 4886.00  769.22 5114.00    0.00  769.64
Permanent Ineff=
       F       F
Bank Sta=4970,5030
XS Rating Curve= 0
Exp/Cntr=0.5,0.3

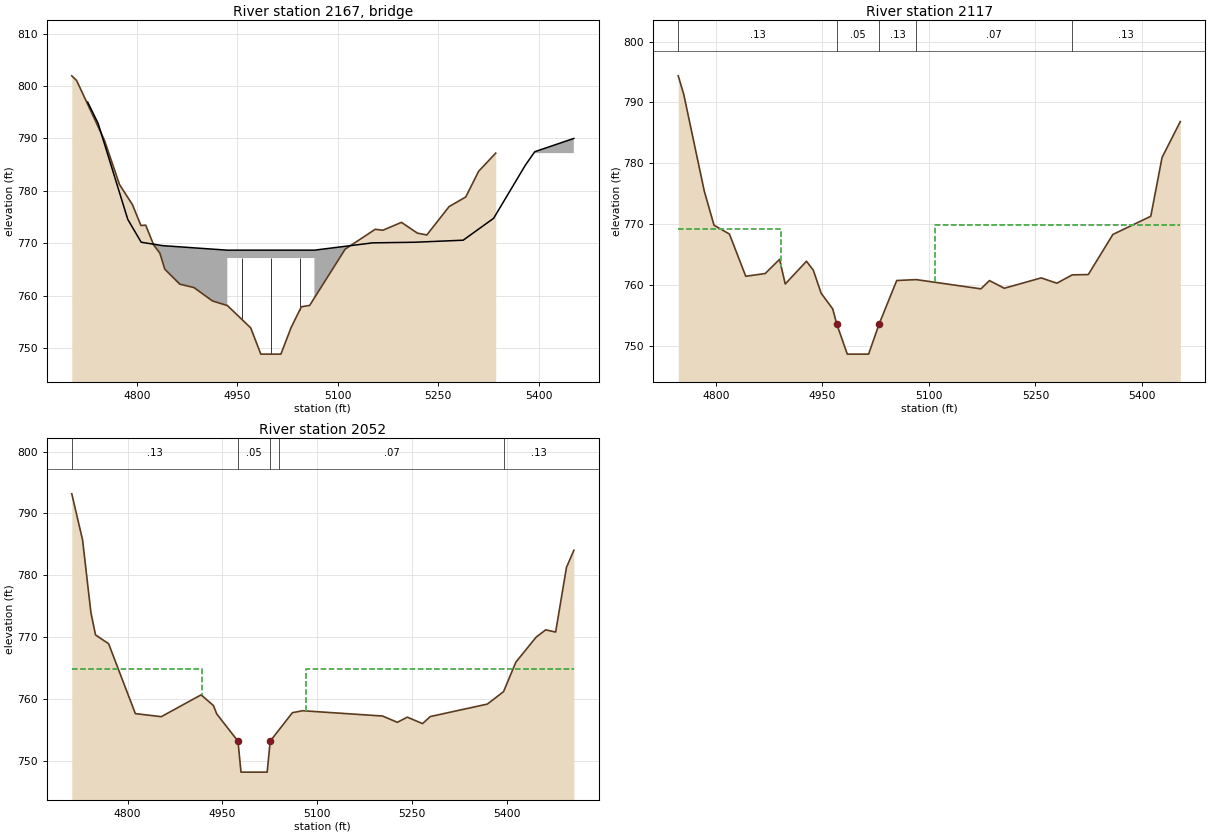
Type RM Length L Ch R =3,2167,,,
BEGIN DESCRIPTION:
Railroad (GC) TOR
Structure ID: GC_RR_estimate
Approximate Survey Structure
END DESCRIPTION:
Bridge Culvert--1,0,-1,-1,0
Deck Dist Width WeirC Skew NumUp NumDn MinLoCord MaxHiCord MaxSubmerge Is_Ogee
49,14,3,,17,17,,,0.95,0,1,1,,,
  4726.5  4742.1  4786.4  4806.4  4837.9  4891.1  4935.0  4935.0  5065.0  5065.0
  5151.8  5215.3  5287.1  5332.5  5380.0  5394.0  5452.3
  796.95  792.89  774.57  770.21  769.57  769.09  768.70  768.70  768.70  768.70
  770.09  770.21  770.60  774.77  784.92  787.48  790.01
  728.87  728.87  728.87  728.87  728.87  728.87  728.87  767.20  767.20  728.87
  728.87  728.87  728.87  728.87  728.87  728.87  728.87
  4726.5  4742.1  4786.4  4806.4  4837.9  4891.1  4935.0  4935.0  5065.0  5065.0
  5151.8  5215.3  5287.1  5332.5  5380.0  5394.0  5452.3
  796.95  792.89  774.57  770.21  769.57  769.09  768.70  768.70  768.70  768.70
  770.09  770.21  770.60  774.77  784.92  787.48  790.01
  728.87  728.87  728.87  728.87  728.87  728.87  728.87  767.20  767.20  728.87
  728.87  728.87  728.87  728.87  728.87  728.87  728.87
Pier Skew, UpSta & Num, DnSta & Num=,4956.7,2,4956.7,2,0,0,0,0,0
       1       1
  748.00  767.20
       1       1
  748.00  767.20
Pier Skew, UpSta & Num, DnSta & Num=,5000,2,5000,2,0,0,0,0,0
       1       1
  748.00  767.20
       1       1
  748.00  767.20
Pier Skew, UpSta & Num, DnSta & Num=,5043.3,2,5043.3,2,0,0,0,0,0
       1       1
  748.00  767.20
       1       1
  748.00  767.20
Abutment Skew #Up #Dn=,2,2
  4935.0  4940.0
  767.20  757.52
  4935.0  4940.0
  767.20  761.44
Abutment Skew #Up #Dn=,2,2
  5060.0  5065.0
  758.63  767.20
  5060.0  5065.0
  760.54  767.20
BR Coef=1,1,0,1.25,0,,,0.8,0,2,0,
WSPro=,,,, 1 ,,,, 0 ,,,, 0 ,,,,-1 ,-1 ,-1 , 0 , 0 , 0 , 0 , 0
BC Design=,,0,,0,,,,,,

Type RM Length L Ch R = 1,2117,65,65,65
BEGIN DESCRIPTION:
Railroad (GC) ds
END DESCRIPTION:
XS GIS Cut Line= 5
      1567027.19       917731.83      1566939.49       917688.70
      1566617.35       917760.61      1566473.54       917790.81
      1566384.36       917888.61
#Sta/Elev= 30
  4746.9  794.37  4754.6  791.36  4783.6  775.41  4797.3  769.81  4819.0  768.36
  4842.0  761.42  4869.4  761.87  4889.6  764.20  4897.6  760.15  4927.5  763.89
  4937.1  762.43  4948.2  758.63  4964.5  756.05  4970.0  753.62  4985.0  748.62
  5015.0  748.62  5030.0  753.62  5054.6  760.72  5082.1  760.87  5173.2  759.35
  5185.2  760.71  5206.1  759.45  5258.0  761.15  5280.2  760.28  5301.8  761.65
  5324.4  761.70  5359.1  768.30  5412.4  771.28  5428.3  780.95  5454.0  786.85
#Mann=5,-1,0
  4746.9    0.13       0  4970.0    0.05       0  5030.0    0.13       0
  5082.1    0.07       0  5301.8    0.13       0
#XS Ineff=2,0
    0.00 4892.00  769.12 5108.00    0.00  769.90
Permanent Ineff=
       F       F
Bank Sta=4970,5030
XS Rating Curve= 0
Exp/Cntr=0.5,0.3

Type RM Length L Ch R = 1,2052,0,0,0
BEGIN DESCRIPTION:
Grassy Creek 1.0
END DESCRIPTION:
XS GIS Cut Line= 5
      1567074.66       917714.58      1566969.69       917636.93
      1566696.45       917681.51      1566463.47       917772.11
      1566375.75       917877.08
#Sta/Elev= 30
  4711.6  793.17  4728.7  785.73  4741.9  773.98  4749.2  770.40  4769.9  768.98
  4812.2  757.70  4853.2  757.21  4916.2  760.73  4935.7  759.00  4941.0  757.64
  4974.5  753.26  4979.3  748.26  5020.7  748.26  5025.5  753.26  5040.1  755.17
  5060.6  757.85  5076.8  758.17  5203.3  757.31  5226.6  756.30  5242.4  757.13
  5266.4  756.09  5278.8  757.23  5369.0  759.24  5394.6  761.25  5414.1  766.01
  5446.2  770.05  5461.3  771.22  5477.0  770.86  5494.1  781.29  5505.8  784.05
#Mann=5,-1,0
  4711.6    0.13       0  4974.5    0.05       0  5025.5    0.13       0
  5040.1    0.07       0  5394.6    0.13       0
#XS Ineff=2,0
    0.00 4917.10  764.83 5082.90    0.00  764.83
Permanent Ineff=
       F       F
Bank Sta=4974.5,5025.5
XS Rating Curve= 0
Exp/Cntr=0.3,0.1

Chan Stop Cuts=-1