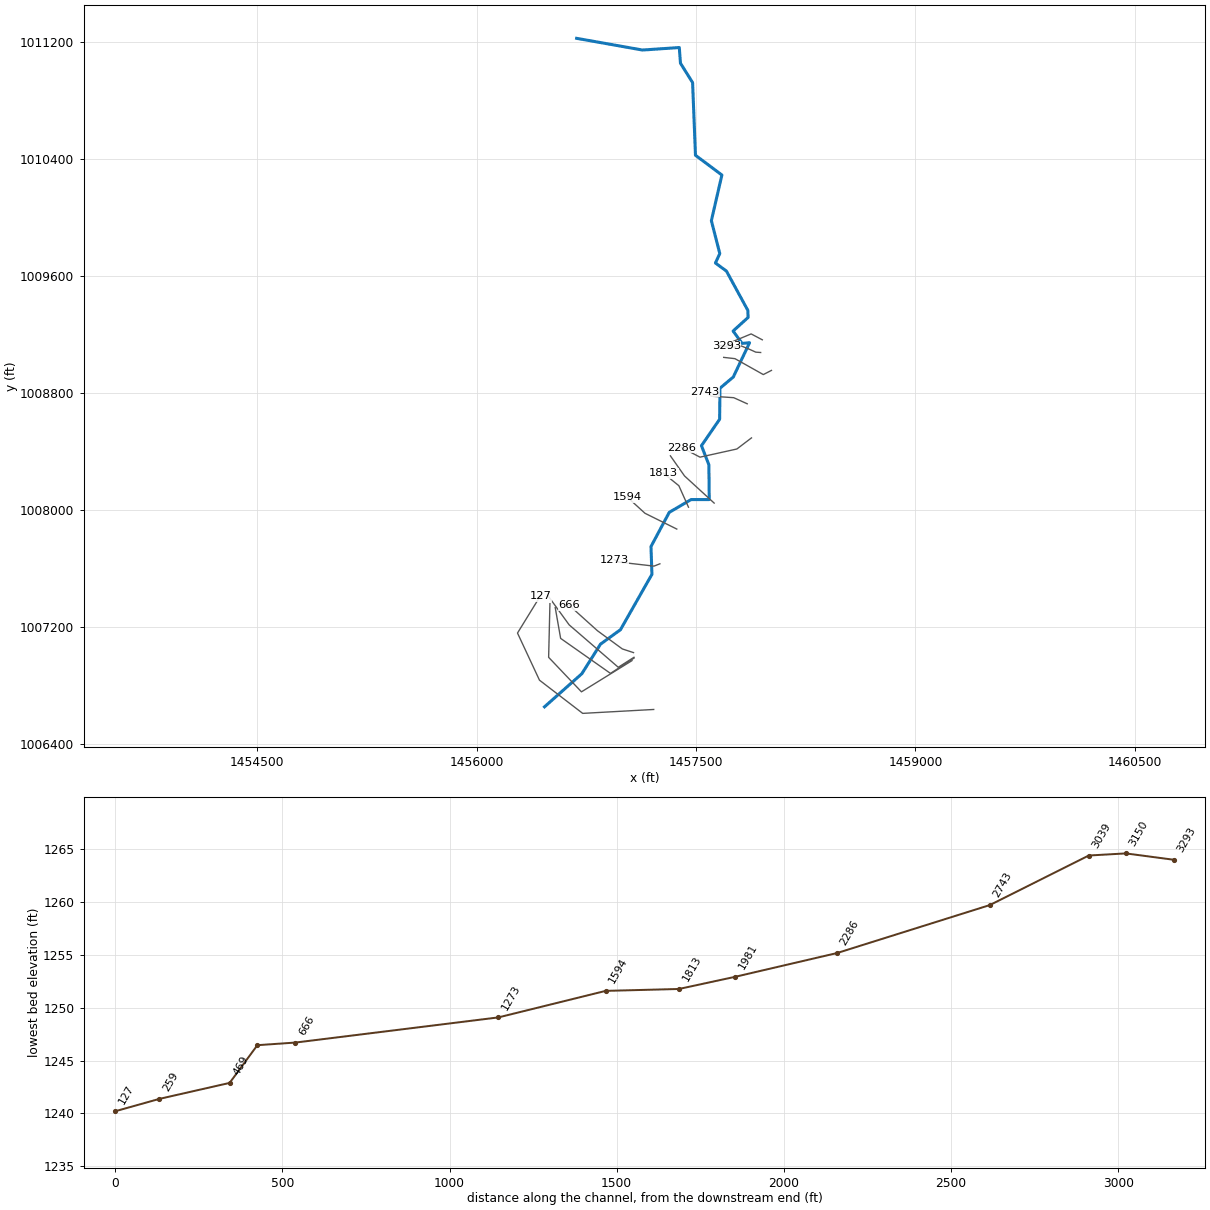
--- Camp Branch.prj (project) ---

Proj Title=Camp Branch Limited Detail Study
Current Plan=p01
Default Exp/Contr=0.3,0.1
English Units
Geom File=g01
Flow File=f01
Plan File=p01
Y Axis Title=Elevation
X Axis Title(PF)=Main Channel Distance
X Axis Title(XS)=Station
BEGIN DESCRIPTION:
Camp Branch
END DESCRIPTION:
DSS Export Rating Curves= 0
DSS Export Rating Curve Sorted= 0
DSS Export Volume Flow Curves= 0
DXF OffsetX= 0
DXF OffsetY= 0
DXF ScaleX= 1
DXF ScaleY= 10

--- Camp Branch.p01 (plan) ---

Plan Title=Floodway Run
Program Version=3.12
Short Identifier=Floodway
Geom File=g01
Flow File=f01
Subcritical Flow
K Sum by GR= 0
Std Step Tol= 0.01
Critical Tol= 0.01
Num of Std Step Trials= 20
Max Error Tol= 0.3
Flow Tol Ratio= 0.001
Split Flow NTrial= 30
Split Flow Tol= 0.02
Split Flow Ratio= 0.02
Log Output Level= 0
Friction Slope Method= 1
Unsteady Friction Slope Method= 2
Unsteady Bridges Friction Slope Method= 1
Parabolic Critical Depth
Global Vel Dist= 0 , 0 , 0
Global Log Level= 0
CheckData=True
Encroach Param=-1 ,0,0, 2
Encroach River=Camp Branch
Encroach Reach=Reach-1
Encroach Node=3293
       1  4889.7  5029.2
Encroach Node=3150
       1    4975    5025
Encroach Node=3039
       1    4975    5025
Encroach Node=2743
       1 4919.79  5013.1
Encroach Node=2286
       1 4942.74  5010.2
Encroach Node=1981
       1  4990.1    5042
Encroach Node=1813
       1  4990.1    5060
Encroach Node=1594
       1  4979.7    5100
Encroach Node=1273
       1    4987    5170
Encroach Node=666
       1    4965    5035
Encroach Node=552
       1    4965    5035
Encroach Node=469
       1    4974 5160.95
Encroach Node=259
       1 4941.29  5167.2
Encroach Node=127
       1    4900    5051
BEGIN DESCRIPTION:
Floodway Run
END DESCRIPTION:
Computation Interval=1HOUR
Output Interval=1HOUR
Run HTab= 0
Run UNet= 0
Run PostProcess= 0
UNET Theta= 1
UNET Theta Warmup= 1
UNET ZTol= 0.02
UNET ZSATol= 0.05
UNET MxIter= 20
UNET MaxInSteps= 0
UNET DtIC= 0
UNET DtMin= 0
UNET MaxCRTS= 20
UNET WFStab= 2
UNET SFStab= 1
UNET WFX= 1
UNET SFX= 1
UNET DSS MLevel= 4
UNET DZMax Abort= 100
UNET Convert EG Bridges=-1
UNET Use Existing IB Tables=-1
UNET Froude Reduction=False
UNET Froude Limit= 1
UNET Froude Power= 10
Instantaneous Interval=1HOUR
Write IC File= 0
Echo Input=False
Echo Output=False
Write Detailed= 0
Detailed Automatic Start=False, 10

--- Camp Branch.f01 (steady flow) ---

Flow Title=Floodway
Number of Profiles=2
Profile Names=100-year,100-FW
River Rch & RM= Camp Branch,Reach-1,3293
    1610    1610
River Rch & RM= Camp Branch,Reach-1,3150
    1753    1753
River Rch & RM= Camp Branch,Reach-1,2743
    1857    1857
Boundary for River Rch & Prof#=Camp Branch,Reach-1,1
Up Type=0
Dn Type=3
Dn Slope=0.009
Boundary for River Rch & Prof#=Camp Branch,Reach-1,2
Up Type=0
Dn Type=3
Dn Slope=0.009

--- Camp Branch.g01 (geometry) ---

Geom Title=Existing Conditions

River Reach=Camp Branch,Reach-1
Reach XY= 30
      1456683.50      1011226.31      1457133.75      1011146.31
      1457385.50      1011163.38      1457393.25      1011056.38
      1457476.25      1010923.88      1457495.97      1010426.62
      1457676.67      1010291.76      1457604.71      1009979.41
      1457662.27      1009754.47      1457632.43      1009689.98
      1457707.58      1009635.07      1457854.16      1009365.90
      1457855.76      1009317.92      1457753.25      1009224.94
      1457815.03      1009140.43      1457865.93      1009145.17
      1457754.50      1008910.50      1457663.50      1008833.83
      1457661.13      1008621.93      1457536.84      1008440.82
      1457587.74      1008310.60      1457590.11      1008072.66
      1457465.81      1008072.66      1457316.65      1007985.06
      1457191.75      1007751.31      1457198.27      1007561.26
      1456982.82      1007182.45      1456846.69      1007084.19
      1456718.84      1006881.77      1456463.75      1006655.44

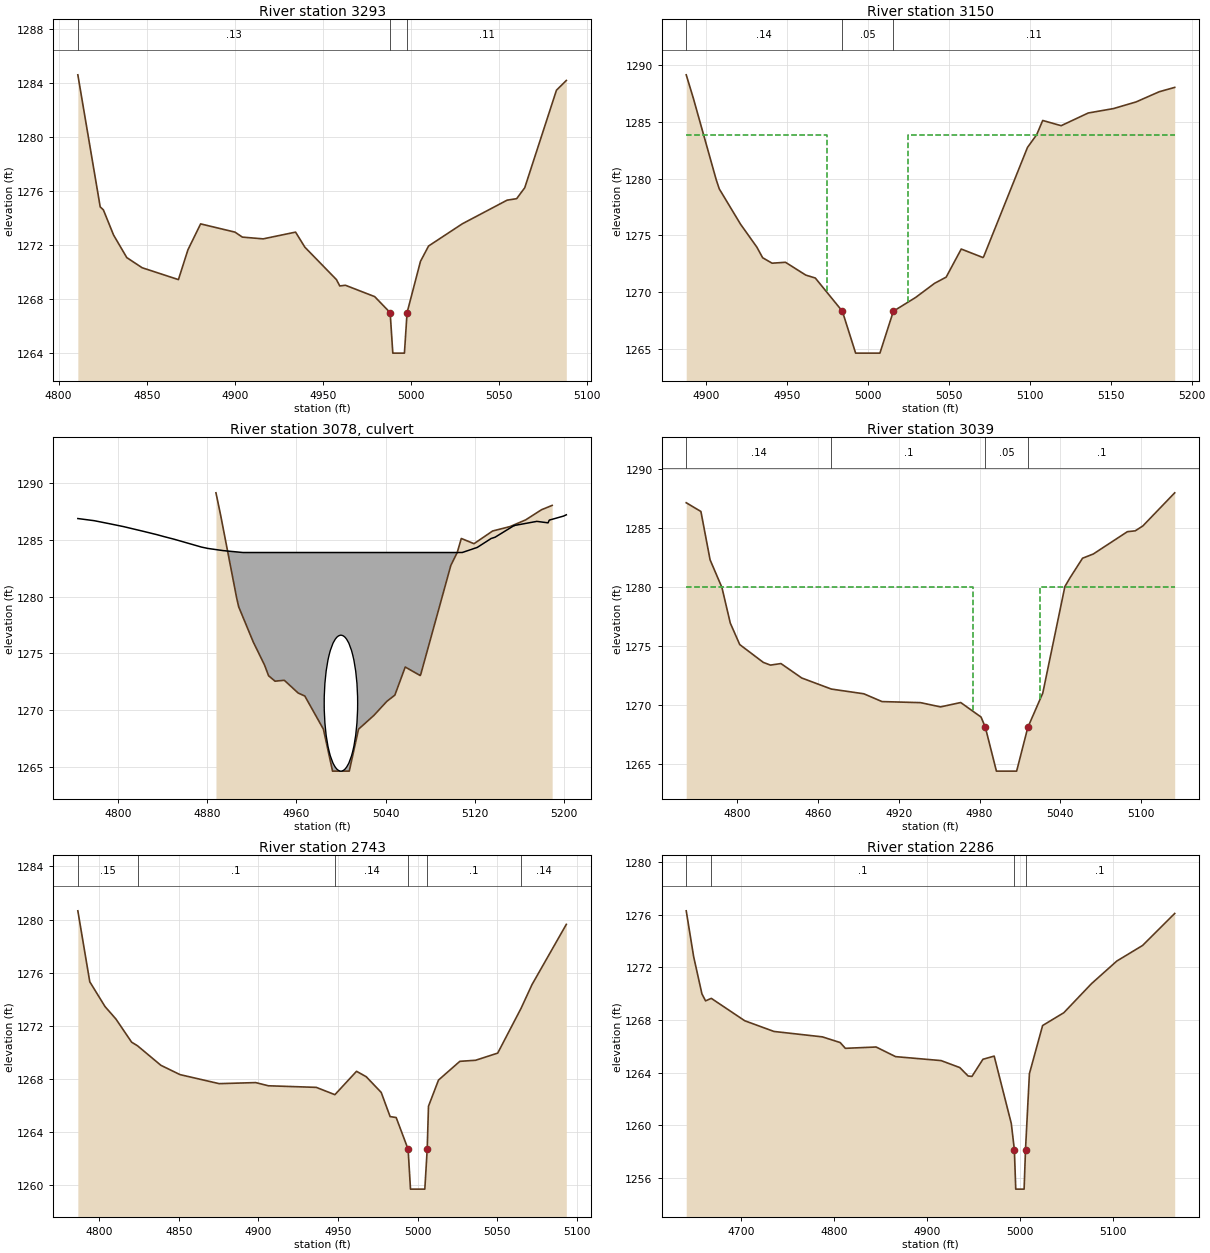
Type RM Length L Ch R = 1,3293,143,143,143
BEGIN DESCRIPTION:
Camp Branch XS 6.0
END DESCRIPTION:
XS GIS Cut Line= 4
      1457952.97      1009164.93      1457876.50      1009205.38
      1457754.92      1009154.52      1457706.24      1009121.17
#Sta/Elev= 30
  4810.9 1284.63  4823.6 1274.84  4825.4 1274.62  4831.2 1272.75  4838.7 1271.08
  4847.4 1270.33  4868.0 1269.45  4873.4 1271.66  4880.6 1273.58  4900.1 1272.97
  4904.3 1272.60  4916.1 1272.47  4934.5 1272.97  4939.8 1271.85  4957.7 1269.45
  4959.6 1268.98  4962.8 1269.03  4979.4 1268.19  4988.2 1267.00  4989.7 1264.00
  4996.3 1264.00  4997.8 1267.00  5005.4 1270.80  5010.0 1271.94  5029.2 1273.59
  5054.6 1275.34  5060.0 1275.45  5064.6 1276.26  5082.6 1283.49  5088.2 1284.21
#Mann=3,-1,0
  4810.9    0.13       0  4988.2    0.05       0  4997.8    0.11       0
Bank Sta=4988.2,4997.8
XS Rating Curve= 0
Exp/Cntr=0.5,0.3

Type RM Length L Ch R = 1,3150,111,111,111
BEGIN DESCRIPTION:
HWY-89 US
END DESCRIPTION:
XS GIS Cut Line= 6
      1457941.69      1009078.23      1457908.28      1009080.62
      1457866.17      1009099.69      1457805.78      1009124.33
      1457728.70      1009110.02      1457653.21      1009130.68
#Sta/Elev= 30
  4887.9 1289.17  4892.2 1287.15  4906.4 1279.92  4908.3 1279.10  4921.4 1275.99
  4931.5 1273.96  4935.1 1273.02  4940.9 1272.54  4949.2 1272.62  4961.7 1271.49
  4967.6 1271.23  4984.3 1268.30  4992.5 1264.60  5007.5 1264.60  5015.8 1268.30
  5029.6 1269.52  5041.2 1270.76  5048.4 1271.31  5057.7 1273.79  5071.1 1273.04
  5071.6 1273.13  5098.6 1282.76  5104.3 1283.89  5108.0 1285.14  5119.4 1284.68
  5136.1 1285.80  5151.7 1286.19  5165.7 1286.78  5180.0 1287.68  5189.5 1288.06
#Mann=3,-1,0
  4887.9    0.14       0  4984.3    0.05       0  5015.8    0.11       0
#XS Ineff=2,0
    0.00 4975.00 1283.90 5025.00    0.00 1283.90
Permanent Ineff=
       F       F
Bank Sta=4984.3,5015.8
XS Rating Curve= 0
Exp/Cntr=0.5,0.3

Type RM Length L Ch R =2,3078,,,
BEGIN DESCRIPTION:
HWY-89 TOR
Structure ID: LDS_CB_02
Approximate Survey Structure
END DESCRIPTION:
Bridge Culvert--1,0,-1,-1,0
Deck Dist Width WeirC Skew NumUp NumDn MinLoCord MaxHiCord MaxSubmerge Is_Ogee
52,40,3,,26,26,,,0.95,0,1,1,,,
  4764.0  4778.7  4791.5  4804.9  4822.4  4834.8  4841.1  4850.5  4874.9  4880.7
  4894.2  4912.1  4915.5  5108.8  5122.3  5134.8  5138.3  5155.0  5155.3  5155.5
  5155.8  5175.7  5185.8  5186.9  5199.8  5202.2
 1286.90 1286.71 1286.46 1286.19 1285.78 1285.48 1285.31 1285.07 1284.38 1284.26
 1284.07 1283.90 1283.90 1283.90 1284.35 1285.14 1285.25 1286.26 1286.27 1286.26
 1286.29 1286.65 1286.52 1286.76 1287.12 1287.23
 1244.60 1244.60 1244.60 1244.60 1244.60 1244.60 1244.60 1244.60 1244.60 1244.60
 1244.60 1244.60 1244.60 1244.60 1244.60 1244.60 1244.60 1244.60 1244.60 1244.60
 1244.60 1244.60 1244.60 1244.60 1244.60 1244.60
  4764.0  4778.7  4791.5  4804.9  4822.4  4834.8  4841.1  4850.5  4874.9  4880.7
  4894.2  4912.1  4915.5  5108.8  5122.3  5134.8  5138.3  5155.0  5155.3  5155.5
  5155.8  5175.7  5185.8  5186.9  5199.8  5202.2
 1286.90 1286.71 1286.46 1286.19 1285.78 1285.48 1285.31 1285.07 1284.38 1284.26
 1284.07 1283.90 1283.90 1283.90 1284.35 1285.14 1285.25 1286.26 1286.27 1286.26
 1286.29 1286.65 1286.52 1286.76 1287.12 1287.23
 1244.40 1244.40 1244.40 1244.40 1244.40 1244.40 1244.40 1244.40 1244.40 1244.40
 1244.40 1244.40 1244.40 1244.40 1244.40 1244.40 1244.40 1244.40 1244.40 1244.40
 1244.40 1244.40 1244.40 1244.40 1244.40 1244.40
Culvert=4,12,30,40,0.013,0.5,1,29,1,1264.6,5000,1264.4,5000,Culvert #1,0,52
Culvert Bottom n=0.013
Culvert Bottom Depth=0
Culvert Depth Blocked=0
BC Design=,,0,,0,,,,,,

Type RM Length L Ch R = 1,3039,296,296,296
BEGIN DESCRIPTION:
HWY-89 DS
END DESCRIPTION:
XS GIS Cut Line= 4
      1458015.54      1008955.86      1457959.93      1008927.26
      1457766.04      1009036.12      1457688.93      1009044.87
#Sta/Elev= 30
  4762.3 1287.13  4773.2 1286.39  4780.0 1282.30  4788.8 1279.95  4795.0 1276.94
  4802.0 1275.12  4819.5 1273.61  4824.8 1273.38  4832.6 1273.51  4848.0 1272.29
  4870.0 1271.35  4894.1 1270.95  4907.6 1270.29  4936.2 1270.20  4951.0 1269.84
  4966.0 1270.21  4981.1 1268.98  4984.3 1268.10  4992.5 1264.40  5007.5 1264.40
  5015.8 1268.10  5026.9 1271.01  5043.3 1280.03  5047.2 1280.79  5056.4 1282.43
  5064.4 1282.79  5089.7 1284.68  5095.5 1284.75  5101.2 1285.17  5124.8 1287.97
#Mann=4,-1,0
  4762.3    0.14       0  4870.0     0.1       0  4984.3    0.05       0
  5015.8     0.1       0
#XS Ineff=2,0
    0.00 4975.00 1280.00 5025.00    0.00 1280.00
Permanent Ineff=
       F       F
Bank Sta=4984.3,5015.8
XS Rating Curve= 0
Exp/Cntr=0.5,0.3

Type RM Length L Ch R = 1,2743,457,457,457
BEGIN DESCRIPTION:
Camp Branch XS 5.0
END DESCRIPTION:
XS GIS Cut Line= 4
      1457849.87      1008727.51      1457757.37      1008769.33
      1457604.06      1008779.47      1457562.22      1008809.90
#Sta/Elev= 30
  4786.5 1280.66  4794.0 1275.32  4803.6 1273.45  4810.4 1272.52  4820.3 1270.77
  4824.0 1270.50  4838.7 1269.03  4850.7 1268.33  4875.3 1267.65  4898.2 1267.73
  4906.2 1267.49  4936.3 1267.37  4948.0 1266.82  4961.6 1268.58  4967.7 1268.17
  4977.1 1266.99  4982.7 1265.17  4986.5 1265.10  4994.0 1262.71  4995.5 1259.71
  5004.5 1259.71  5006.0 1262.71  5006.8 1265.95  5013.1 1267.92  5026.5 1269.33
  5036.4 1269.41  5050.3 1269.95  5065.0 1273.33  5071.9 1275.12  5093.4 1279.64
#Mann=6,-1,0
  4786.5    0.15       0  4824.0     0.1       0  4948.0    0.14       0
  4994.0    0.05       0  5006.0     0.1       0  5065.0    0.14       0
Bank Sta=4994,5006
XS Rating Curve= 0
Exp/Cntr=0.3,0.1

Type RM Length L Ch R = 1,2286,305,305,305
BEGIN DESCRIPTION:
Camp Branch XS 4.0
END DESCRIPTION:
XS GIS Cut Line= 4
      1457878.96      1008494.37      1457778.91      1008418.38
      1457526.78      1008362.63      1457401.38      1008428.50
#Sta/Elev= 30
  4641.0 1276.28  4649.0 1272.80  4657.9 1269.98  4661.8 1269.45  4668.0 1269.64
  4704.0 1267.94  4735.4 1267.13  4787.4 1266.72  4806.6 1266.29  4812.2 1265.85
  4845.3 1265.95  4866.2 1265.22  4915.2 1264.92  4935.3 1264.39  4944.3 1263.75
  4948.4 1263.72  4960.2 1265.02  4972.3 1265.26  4990.7 1260.15  4994.0 1258.17
  4995.5 1255.17  5004.5 1255.17  5006.0 1258.17  5010.2 1263.93  5024.4 1267.58
  5047.2 1268.55  5076.9 1270.75  5104.2 1272.47  5131.9 1273.65  5166.5 1276.08
#Mann=4,-1,0
  4641.0    0.15       0  4668.0     0.1       0  4994.0    0.05       0
  5006.0     0.1       0
Bank Sta=4994,5006
XS Rating Curve= 0
Exp/Cntr=0.3,0.1

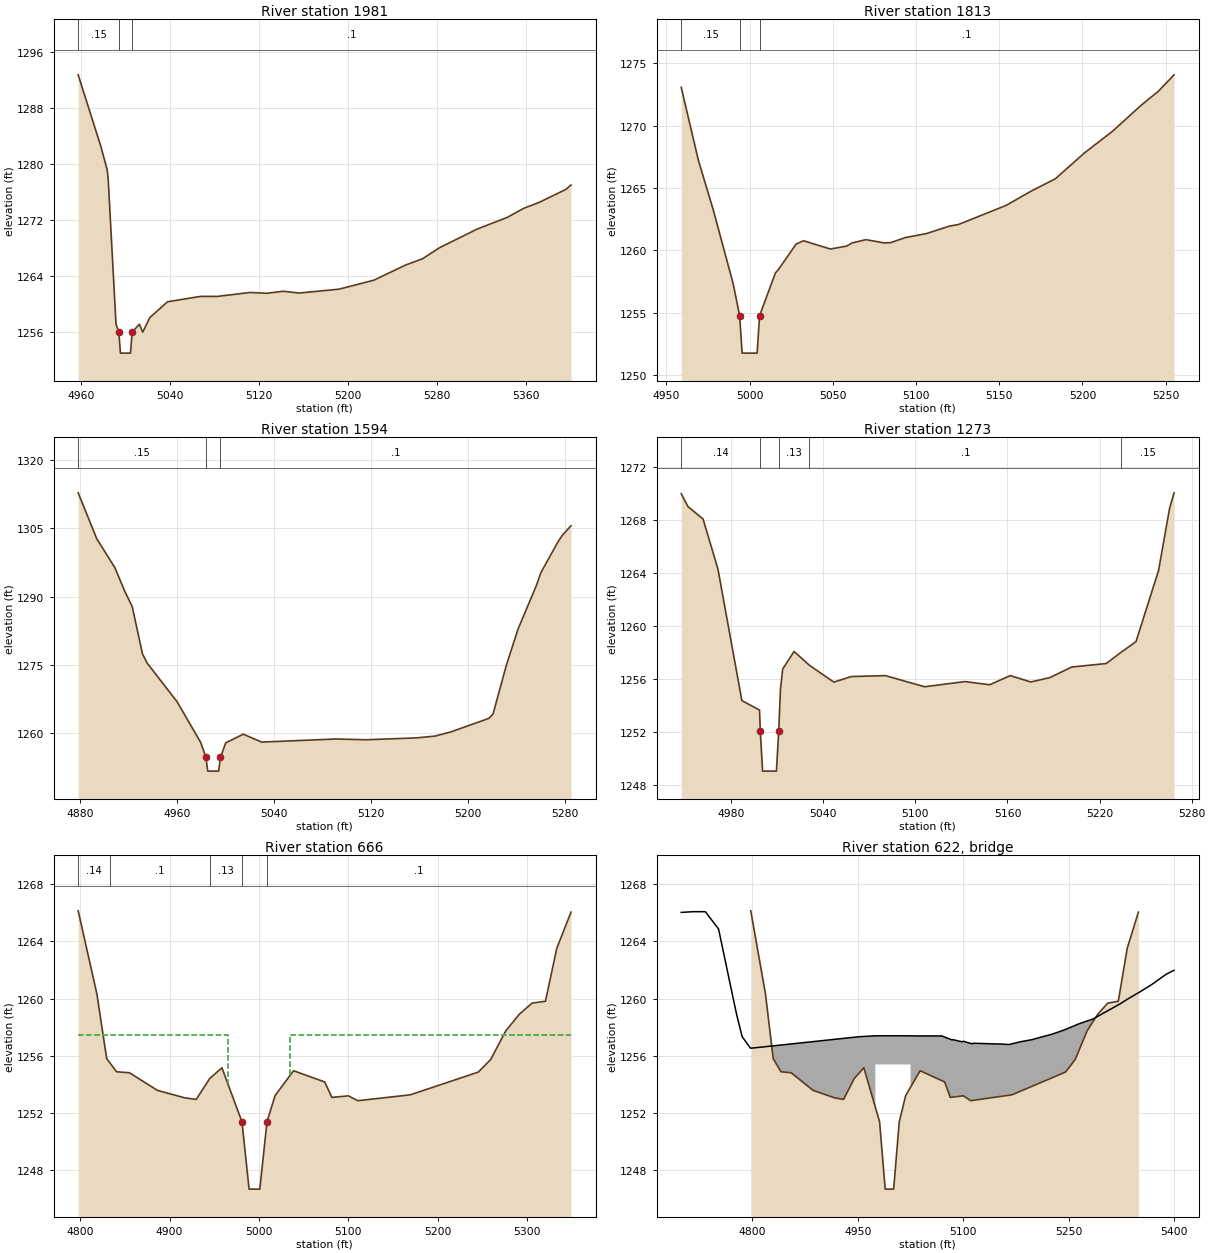
Type RM Length L Ch R = 1,1981,168,168,168
BEGIN DESCRIPTION:
Camp Branch 3.5
END DESCRIPTION:
XS GIS Cut Line= 3
      1457623.76      1008048.57      1457421.37      1008233.95
      1457324.43      1008371.71
#Sta/Elev= 30
  4957.5 1292.69  4977.8 1282.50  4983.6 1279.10  4984.5 1277.70  4991.5 1257.05
  4994.0 1255.92  4995.5 1252.92  5004.5 1252.92  5006.0 1255.92  5012.5 1257.05
  5015.5 1255.92  5021.9 1258.00  5037.8 1260.26  5067.6 1261.03  5082.3 1261.02
  5112.0 1261.59  5126.8 1261.47  5141.6 1261.76  5156.3 1261.51  5191.9 1262.06
  5223.2 1263.34  5251.8 1265.51  5266.9 1266.40  5282.3 1267.99  5316.1 1270.65
  5343.0 1272.31  5357.6 1273.59  5372.0 1274.48  5395.6 1276.30  5400.4 1276.94
#Mann=3,-1,0
  4957.5    0.15       0  4994.0    0.05       0  5006.0     0.1       0
Bank Sta=4994,5006
XS Rating Curve= 0
Exp/Cntr=0.3,0.1

Type RM Length L Ch R = 1,1813,219,219,219
BEGIN DESCRIPTION:
Camp Branch XS 3.0
END DESCRIPTION:
XS GIS Cut Line= 3
      1457448.22      1008020.56      1457382.35      1008167.52
      1457277.18      1008252.41
#Sta/Elev= 30
  4958.9 1273.06  4969.2 1267.22  4978.2 1263.22  4990.1 1257.34  4994.0 1254.77
  4995.5 1251.77  5004.5 1251.77  5006.0 1254.77  5015.5 1258.19  5017.4 1258.48
  5028.0 1260.51  5032.4 1260.77  5048.5 1260.11  5058.3 1260.34  5061.5 1260.59
  5069.9 1260.86  5080.8 1260.60  5084.8 1260.62  5093.5 1261.02  5106.4 1261.35
  5120.0 1261.94  5125.5 1262.07  5154.3 1263.61  5169.0 1264.73  5183.7 1265.73
  5201.4 1267.82  5218.3 1269.56  5235.3 1271.62  5245.8 1272.76  5255.1 1274.06
#Mann=3,-1,0
  4958.9    0.15       0  4994.0    0.05       0  5006.0     0.1       0
Bank Sta=4994,5006
XS Rating Curve= 0
Exp/Cntr=0.3,0.1

Type RM Length L Ch R = 1,1594,321,321,321
BEGIN DESCRIPTION:
Camp Branch 2.5
END DESCRIPTION:
XS GIS Cut Line= 3
      1457368.17      1007871.01      1457150.93      1007978.81
      1457029.60      1008089.27
#Sta/Elev= 30
  4878.6 1312.82  4893.9 1302.73  4908.9 1296.35  4917.1 1291.13  4923.2 1287.80
  4931.6 1277.42  4935.4 1275.40  4960.2 1266.86  4979.7 1257.89  4984.0 1254.59
  4985.5 1251.59  4994.5 1251.59  4996.0 1254.59  5000.3 1257.80  5014.8 1259.72
  5030.0 1257.98  5091.0 1258.66  5116.1 1258.49  5157.4 1258.90  5173.0 1259.30
  5186.2 1260.23  5217.4 1263.19  5220.9 1264.17  5231.8 1274.84  5241.5 1282.85
  5256.5 1292.34  5260.4 1295.28  5274.6 1302.11  5278.0 1303.47  5285.2 1305.58
#Mann=3,-1,0
  4878.6    0.15       0  4984.0    0.05       0  4996.0     0.1       0
Bank Sta=4984,4996
XS Rating Curve= 0
Exp/Cntr=0.3,0.1

Type RM Length L Ch R = 1,1273,607,607,607
BEGIN DESCRIPTION:
Camp Branch XS 2.0
END DESCRIPTION:
XS GIS Cut Line= 4
      1457252.70      1007633.42      1457212.57      1007617.66
      1456969.31      1007645.53      1456940.69      1007662.04
#Sta/Elev= 30
  4947.5 1269.99  4951.9 1269.02  4961.7 1268.09  4971.4 1264.32  4987.0 1254.40
  4998.5 1253.68  4999.0 1252.08  5000.5 1249.08  5009.5 1249.08  5011.0 1252.08
  5012.1 1255.22  5013.6 1256.78  5021.0 1258.10  5031.0 1257.06  5046.9 1255.79
  5058.3 1256.21  5080.5 1256.28  5106.0 1255.44  5132.3 1255.83  5148.4 1255.59
  5161.8 1256.28  5175.2 1255.80  5187.6 1256.13  5201.9 1256.93  5224.3 1257.19
  5234.0 1258.04  5243.7 1258.84  5258.4 1264.20  5265.6 1268.90  5268.5 1270.06
#Mann=5,-1,0
  4947.5    0.14       0  4999.0    0.05       0  5011.0    0.13       0
  5031.0     0.1       0  5234.0    0.15       0
Bank Sta=4999,5011
XS Rating Curve= 0
Exp/Cntr=0.5,0.3

Type RM Length L Ch R = 1,666,114,114,114
BEGIN DESCRIPTION:
Hidden Valley Rd US
END DESCRIPTION:
XS GIS Cut Line= 4
      1457072.25      1007026.28      1456995.92      1007051.32
      1456826.15      1007175.49      1456632.42      1007349.84
#Sta/Elev= 30
  4797.8 1266.12  4818.7 1260.33  4829.7 1255.81  4833.0 1255.53  4840.8 1254.89
  4855.2 1254.82  4886.5 1253.59  4917.0 1253.07  4929.8 1252.96  4945.0 1254.42
  4958.6 1255.17  4981.0 1251.40  4989.0 1246.70  5001.0 1246.70  5009.0 1251.40
  5018.1 1253.23  5038.7 1254.96  5073.6 1254.18  5081.6 1253.10  5100.1 1253.21
  5110.6 1252.87  5169.3 1253.28  5245.5 1254.87  5259.3 1255.75  5276.1 1257.74
  5291.2 1258.90  5305.5 1259.68  5320.5 1259.81  5333.2 1263.51  5349.1 1266.03
#Mann=5,-1,0
  4797.8    0.14       0  4833.0     0.1       0  4945.0    0.13       0
  4981.0    0.05       0  5009.0     0.1       0
#XS Ineff=2,0
    0.00 4965.00 1257.45 5035.00    0.00 1257.45
Permanent Ineff=
       F       F
Bank Sta=4981,5009
XS Rating Curve= 0
Exp/Cntr=0.5,0.3

Type RM Length L Ch R =3,622,,,
BEGIN DESCRIPTION:
Hidden Valley Rd TOR
Structure ID: LDS_CB_01
Approximate Survey Structure
END DESCRIPTION:
Bridge Culvert--1,0,-1,-1,0
Deck Dist Width WeirC Skew NumUp NumDn MinLoCord MaxHiCord MaxSubmerge Is_Ogee
31.5,25,3,,38,38,,,0.95,0,1,1,,,
  4698.9  4715.5  4733.2  4752.0  4769.4  4777.9  4785.5  4797.5  4950.9  4975.0
  4975.0  5025.0  5025.0  5033.7  5070.3  5070.8  5084.2  5085.3  5098.4  5100.0
  5112.4  5114.5  5154.8  5164.9  5182.0  5197.6  5212.3  5226.2  5242.6  5265.9
  5284.4  5323.1  5329.4  5337.5  5351.0  5368.2  5388.7  5399.8
 1266.01 1266.06 1266.06 1264.85 1260.80 1258.84 1257.34 1256.53 1257.33 1257.40
 1257.40 1257.40 1257.40 1257.39 1257.39 1257.36 1257.11 1257.13 1256.98 1257.02
 1256.84 1256.88 1256.82 1256.79 1256.99 1257.13 1257.33 1257.51 1257.79 1258.26
 1258.57 1259.63 1259.83 1260.07 1260.46 1260.98 1261.70 1261.97
 1226.70 1226.70 1226.70 1226.70 1226.70 1226.70 1226.70 1226.70 1226.70 1226.70
 1255.40 1255.40 1226.70 1226.70 1226.70 1226.70 1226.70 1226.70 1226.70 1226.70
 1226.70 1226.70 1226.70 1226.70 1226.70 1226.70 1226.70 1226.70 1226.70 1226.70
 1226.70 1226.70 1226.70 1226.70 1226.70 1226.70 1226.70 1226.70
  4698.9  4715.5  4733.2  4752.0  4769.4  4777.9  4785.5  4797.5  4950.9  4975.0
  4975.0  5025.0  5025.0  5033.7  5070.3  5070.8  5084.2  5085.3  5098.4  5100.0
  5112.4  5114.5  5154.8  5164.9  5182.0  5197.6  5212.3  5226.2  5242.6  5265.9
  5284.4  5323.1  5329.4  5337.5  5351.0  5368.2  5388.7  5399.8
 1266.01 1266.06 1266.06 1264.85 1260.80 1258.84 1257.34 1256.53 1257.33 1257.40
 1257.40 1257.40 1257.40 1257.39 1257.39 1257.36 1257.11 1257.13 1256.98 1257.02
 1256.84 1256.88 1256.82 1256.79 1256.99 1257.13 1257.33 1257.51 1257.79 1258.26
 1258.57 1259.63 1259.83 1260.07 1260.46 1260.98 1261.70 1261.97
 1226.70 1226.70 1226.70 1226.70 1226.70 1226.70 1226.70 1226.70 1226.70 1226.70
 1255.40 1255.40 1226.70 1226.70 1226.70 1226.70 1226.70 1226.70 1226.70 1226.70
 1226.70 1226.70 1226.70 1226.70 1226.70 1226.70 1226.70 1226.70 1226.70 1226.70
 1226.70 1226.70 1226.70 1226.70 1226.70 1226.70 1226.70 1226.70
BR Coef=1,1,0,1.25,0,,,0.8,0,2,0,
WSPro=,,,, 1 ,,,, 0 ,,,, 0 ,,,,-1 ,-1 ,-1 , 0 , 0 , 0 , 0 , 0
BC Design=,,0,,0,,,,,,

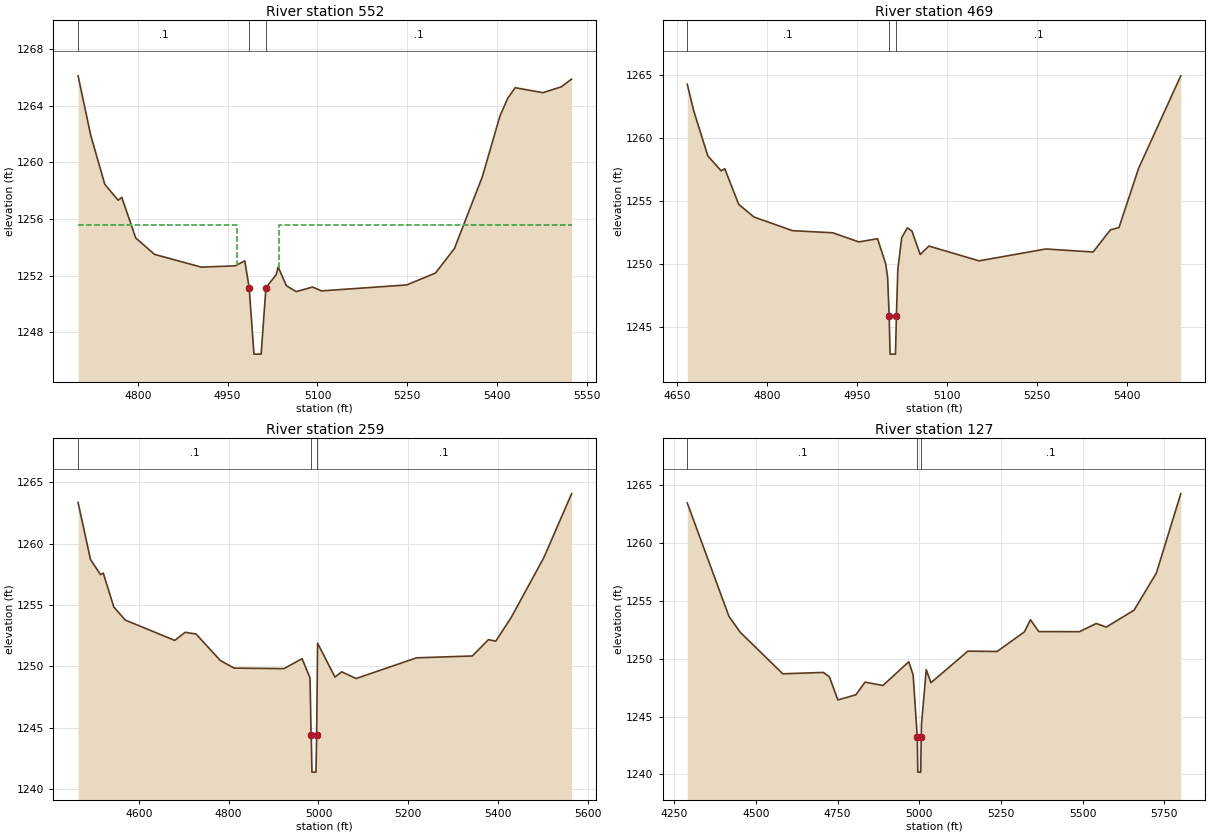
Type RM Length L Ch R = 1,552,83,83,83
BEGIN DESCRIPTION:
Hidden Valley Rd DS
END DESCRIPTION:
XS GIS Cut Line= 4
      1457075.72      1006994.30      1456968.05      1006925.89
      1456632.30      1007216.03      1456484.04      1007420.05
#Sta/Elev= 30
  4700.5 1266.12  4721.5 1261.93  4745.0 1258.46  4767.3 1257.33  4773.4 1257.53
  4796.7 1254.66  4828.1 1253.50  4906.0 1252.60  4962.7 1252.69  4978.7 1253.04
  4986.0 1251.15  4994.0 1246.45  5006.0 1246.45  5014.0 1251.15  5031.1 1252.06
  5034.3 1252.61  5048.2 1251.28  5064.4 1250.87  5091.8 1251.19  5106.8 1250.92
  5248.9 1251.34  5296.9 1252.18  5328.6 1253.92  5375.2 1259.00  5404.4 1263.27
  5417.4 1264.53  5429.9 1265.28  5476.2 1264.93  5506.8 1265.34  5524.0 1265.89
#Mann=3,-1,0
  4700.5     0.1       0  4986.0    0.05       0  5014.0     0.1       0
#XS Ineff=2,0
    0.00 4965.00 1255.60 5035.00    0.00 1255.60
Permanent Ineff=
       F       F
Bank Sta=4986,5014
XS Rating Curve= 0
Exp/Cntr=0.5,0.3

Type RM Length L Ch R = 1,469,210,210,210
BEGIN DESCRIPTION:
Camp Branch XS 1.0
END DESCRIPTION:
XS GIS Cut Line= 4
      1457075.71      1006988.72      1456914.83      1006884.08
      1456574.02      1007123.54      1456537.05      1007334.29
#Sta/Elev= 30
  4667.5 1264.24  4678.2 1262.14  4701.7 1258.57  4723.9 1257.38  4730.0 1257.55
  4753.2 1254.73  4778.6 1253.73  4842.8 1252.65  4910.0 1252.48  4953.4 1251.76
  4984.6 1252.01  4998.3 1250.01  5001.4 1248.95  5004.0 1245.88  5005.5 1242.88
  5014.5 1242.88  5016.0 1245.88  5018.4 1249.58  5024.9 1252.10  5034.3 1252.87
  5041.9 1252.62  5055.7 1250.76  5070.1 1251.43  5153.8 1250.26  5265.1 1251.20
  5343.9 1250.96  5372.6 1252.71  5387.0 1252.90  5419.6 1257.57  5489.9 1264.90
#Mann=3,-1,0
  4667.5     0.1       0  5004.0    0.05       0  5016.0     0.1       0
Bank Sta=5004,5016
XS Rating Curve= 0
Exp/Cntr=0.3,0.1

Type RM Length L Ch R = 1,259,132,132,132
BEGIN DESCRIPTION:
Camp Branch XS 0.5
END DESCRIPTION:
XS GIS Cut Line= 4
      1457061.92      1006971.46      1456716.46      1006758.01
      1456491.98      1006994.00      1456500.85      1007360.90
#Sta/Elev= 30
  4464.8 1263.35  4492.4 1258.71  4514.8 1257.47  4520.8 1257.60  4544.3 1254.84
  4569.7 1253.77  4680.0 1252.11  4703.3 1252.77  4727.5 1252.63  4781.6 1250.47
  4812.3 1249.85  4923.2 1249.81  4963.6 1250.62  4981.3 1249.04  4983.6 1244.37
  4984.0 1244.37  4985.5 1241.37  4994.5 1241.37  4996.0 1244.37  4998.1 1251.88
  5036.8 1249.12  5051.8 1249.55  5083.7 1249.00  5218.6 1250.69  5342.7 1250.84
  5378.5 1252.17  5394.8 1252.05  5428.9 1253.96  5501.9 1258.86  5563.6 1264.06
#Mann=3,-1,0
  4464.8     0.1       0  4983.6    0.05       0  4996.0     0.1       0
Bank Sta=4983.6,4996
XS Rating Curve= 0
Exp/Cntr=0.3,0.1

Type RM Length L Ch R = 1,127,0,0,0
BEGIN DESCRIPTION:
Camp Branch XS 0.25
END DESCRIPTION:
XS GIS Cut Line= 5
      1457210.59      1006637.45      1456724.83      1006610.75
      1456429.34      1006837.79      1456279.09      1007159.99
      1456434.35      1007412.07
#Sta/Elev= 30
  4289.8 1263.47  4417.5 1253.66  4451.9 1252.29  4582.3 1248.70  4706.6 1248.82
  4725.1 1248.43  4750.8 1246.44  4806.2 1246.89  4834.1 1247.98  4888.7 1247.69
  4967.9 1249.74  4981.3 1248.60  4994.0 1243.20  4995.5 1240.20  5004.5 1240.20
  5006.0 1243.20  5007.0 1244.39  5021.4 1249.06  5035.8 1247.93  5148.9 1250.66
  5238.2 1250.63  5322.1 1252.33  5340.3 1253.37  5365.9 1252.35  5490.3 1252.34
  5541.9 1253.05  5572.5 1252.74  5657.5 1254.20  5725.9 1257.41  5800.5 1264.26
#Mann=3,-1,0
  4289.8     0.1       0  4994.0    0.05       0  5006.0     0.1       0
Bank Sta=4994,5006
XS Rating Curve= 0
Exp/Cntr=0.3,0.1

Chan Stop Cuts=-1