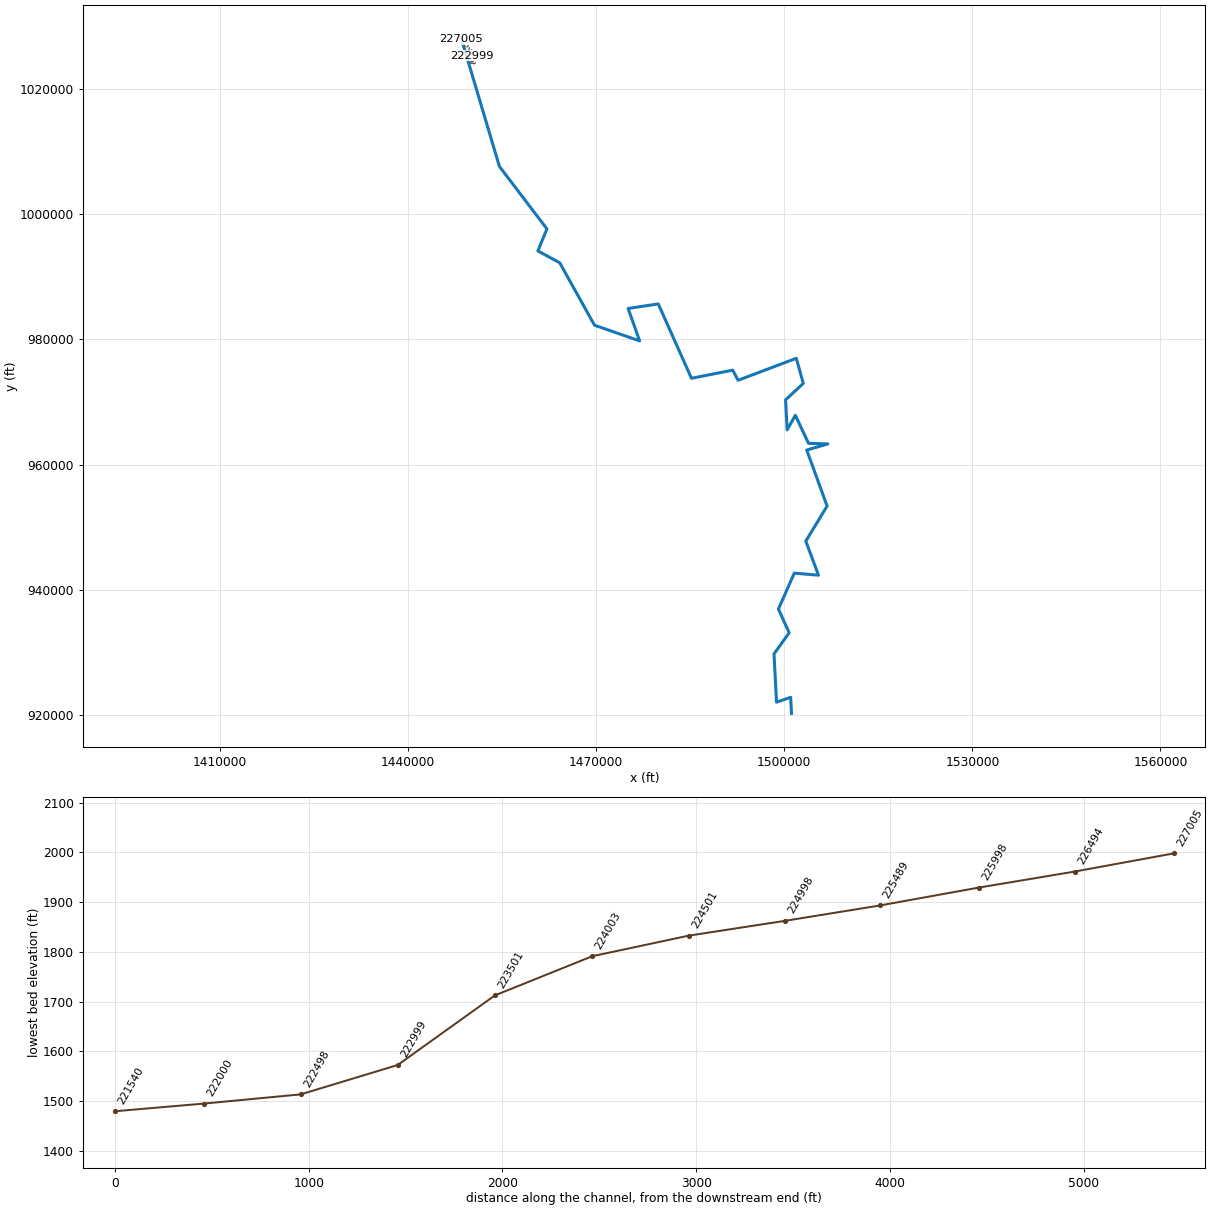
--- Fisher River.prj (project) ---

Proj Title=Fisher River Limited Detail Study
Current Plan=p01
Default Exp/Contr=0.3,0.1
English Units
Geom File=g01
Flow File=f01
Plan File=p01
Y Axis Title=Elevation
X Axis Title(PF)=Main Channel Distance
X Axis Title(XS)=Station
BEGIN DESCRIPTION:
Fisher River
END DESCRIPTION:
DSS Export Rating Curves= 0
DSS Export Rating Curve Sorted= 0
DSS Export Volume Flow Curves= 0
DXF OffsetX= 0
DXF OffsetY= 0
DXF ScaleX= 1
DXF ScaleY= 10

--- Fisher River.p01 (plan) ---

Plan Title=Floodway Run
Program Version=3.12
Short Identifier=Floodway
Geom File=g01
Flow File=f01
Subcritical Flow
K Sum by GR= 0
Std Step Tol= 0.01
Critical Tol= 0.01
Num of Std Step Trials= 20
Max Error Tol= 0.3
Flow Tol Ratio= 0.001
Split Flow NTrial= 30
Split Flow Tol= 0.02
Split Flow Ratio= 0.02
Log Output Level= 0
Friction Slope Method= 1
Unsteady Friction Slope Method= 2
Unsteady Bridges Friction Slope Method= 1
Parabolic Critical Depth
Global Vel Dist= 0 , 0 , 0
Global Log Level= 0
CheckData=True
Encroach Param=-1 ,10,10, 2
Encroach River=Fisher River
Encroach Reach=Reach-1
Encroach Node=227005
       1    4987    5009
Encroach Node=226494
       1    4991  5016.5
Encroach Node=225998
       1 4988.18    5017
Encroach Node=225489
       1 4985.45    5020
Encroach Node=224998
       1 4985.86  5016.5
Encroach Node=224501
       1    4993  5009.1
Encroach Node=224003
       1  4984.3    5013
Encroach Node=223501
       1 4981.48 5008.07
Encroach Node=222999
       1  4985.6  5017.7
Encroach Node=222498
       1  4982.8  5011.8
Encroach Node=222000
       1 4979.65 5011.56
Encroach Node=221540
       1  4949.7  5017.2
Encroach Node=221320
       1  4985.8    5014
Encroach Node=221219
       1  4985.7    5015
Encroach Node=220938
       1    4984  5017.7
Encroach Node=220497
       1 4906.42  5019.5
Encroach Node=219999
       1 4957.05 5032.34
Encroach Node=219498
       1    4962  5015.8
Encroach Node=219276
       1    4955    5050
Encroach Node=219237
       1    4955    5050
Encroach Node=219159
       1  4978.7    5078
Encroach Node=218994
       1    4962    5085
Encroach Node=218944
       1    4912    5085
Encroach Node=218720
       1    4940    5024
Encroach Node=218256
       1    4965 5025.17
Encroach Node=218202
       1    4965    5015
Encroach Node=217923
       1    4875  5005.8
Encroach Node=217503
       1 4967.95    5036
Encroach Node=217010
       1    4973  5015.5
Encroach Node=216617
       1    4945    5026
Encroach Node=216247
       1    4974    5080
Encroach Node=216191
       1    4972  5062.4
Encroach Node=215891
       1    4908    5065
Encroach Node=215419
       1  4925.2  5017.3
Encroach Node=214841
       1  4974.5  5131.5
Encroach Node=214411
       1    4966    5033
Encroach Node=214308
       1  4962.5    5043
Encroach Node=214015
       1    4980    5031
Encroach Node=213590
       1  4985.3  5143.8
Encroach Node=212999
       1    4910  5053.4
Encroach Node=212517
       1    4932  5034.5
Encroach Node=212016
       1  4954.5    5140
Encroach Node=211487
       1    4973    5236
Encroach Node=210987
       1  4923.5  5309.1
Encroach Node=210445
       1    4966    5034
Encroach Node=210315
       1    4966    5034
Encroach Node=210000
       1    4800  5024.1
Encroach Node=209505
       1 4959.39  5028.3
Encroach Node=209009
       1    4880    5040
Encroach Node=208504
       1    4982    5157
Encroach Node=208008
       1    4958    5034
Encroach Node=207493
       1    4966  5054.9
Encroach Node=207000
       1    4970    5013
Encroach Node=206493
       1    4988    5328
Encroach Node=206003
       1  4975.5    5190
Encroach Node=205500
       1    4950    5040
Encroach Node=204994
       1 4976.75 5020.66
Encroach Node=204594
       1    4970    5030
Encroach Node=204552
       1  4979.8  5019.6
Encroach Node=203929
       1    4883    5043
Encroach Node=203708
       1    4965    5035
Encroach Node=203569
       1    4965    5028
Encroach Node=203003
       1  4914.9    5035
Encroach Node=202498
       1  4958.3    5119
Encroach Node=202091
       1    4949    5051
Encroach Node=202014
       1  4966.5  5020.6
Encroach Node=201510
       1  4969.9  5045.5
Encroach Node=200989
       1    4954    5045
Encroach Node=200491
       1    4812    5285
Encroach Node=199995
       1    4888    5326
Encroach Node=199412
       1 4967.44    5096
Encroach Node=198994
       1    4836  5022.5
Encroach Node=198429
       1  4905.9  5023.1
Encroach Node=198000
       1  4870.8 5037.27
Encroach Node=197483
       1    4965    5200
Encroach Node=196982
       1  4833.5  5064.2
Encroach Node=196454
       1  4971.8  5041.7
Encroach Node=196130
       1    4950 5026.68
Encroach Node=195766
       1    4955  5025.8
Encroach Node=195406
       1  4942.3  5031.5
Encroach Node=195335
       1    4938 5027.55
Encroach Node=195072
       1 4977.25  5040.5
Encroach Node=194867
       1 4973.23    5027
Encroach Node=194496
       1 4974.03    5035
Encroach Node=193996
       1  4964.1    5046
Encroach Node=193496
       1  4964.1 5024.22
Encroach Node=193004
       1    4966 5027.83
Encroach Node=192492
       1    4955 5030.99
Encroach Node=191985
       1  4955.1  5035.9
Encroach Node=191422
       1 4955.99 5032.85
Encroach Node=191358
       1 4955.99 5032.85
Encroach Node=191000
       1  4961.1    5038
Encroach Node=190514
       1    4964  5029.7
Encroach Node=189933
       1  4969.6  5036.4
Encroach Node=189507
       1 4956.95 5031.83
Encroach Node=188993
       1    4952    5038
Encroach Node=188580
       1  4911.8  5062.7
Encroach Node=188329
       1  4942.5  5072.5
Encroach Node=188160
       1    4949 5043.61
Encroach Node=187511
       1  4963.8 5032.56
Encroach Node=186997
       1 4968.47    5073
Encroach Node=186506
       1  4863.4  5022.3
Encroach Node=186000
       1  4953.6  5058.2
Encroach Node=185477
       1  4974.5  5052.2
Encroach Node=184977
       1    4962  5040.4
Encroach Node=184486
       1  4740.2  5042.3
Encroach Node=183991
       1  4616.1    5037
Encroach Node=183607
       1  4973.5    5063
Encroach Node=183188
       1    4665    5037
Encroach Node=183006
       1    4700    5037
Encroach Node=182497
       1    4910    5037
Encroach Node=181983
       1 4899.66    5300
Encroach Node=181514
       1  4961.2    5330
Encroach Node=181024
       1    4930    5070
Encroach Node=180969
       1 4942.39    5070
Encroach Node=180771
       1  4947.8 5032.89
Encroach Node=180511
       1    4950 5045.44
Encroach Node=180441
       1    4940    5048
Encroach Node=180008
       1 4961.27  5042.9
Encroach Node=179496
       1  4965.9  5028.5
Encroach Node=178998
       1 4965.96  5039.6
Encroach Node=178495
       1 4965.74    5135
Encroach Node=178010
       1 4950.59 5040.21
Encroach Node=177511
       1  4954.2  5038.7
Encroach Node=176993
       1 4952.25  5039.7
Encroach Node=176565
       1  4960.3    5090
Encroach Node=175999
       1  4955.5  5043.5
Encroach Node=175501
       1  4963.9 5042.46
Encroach Node=175000
       1    4950  5036.9
Encroach Node=174507
       1  4952.4 5038.29
Encroach Node=173990
       1  4960.3 5137.19
Encroach Node=173534
       1  4940.3    5250
Encroach Node=173052
       1  4940.2  5117.4
Encroach Node=172608
       1    4900    5100
Encroach Node=172414
       1  4939.5    5100
Encroach Node=171951
       1 4912.23 5149.95
Encroach Node=171506
       1 4711.74 5070.44
Encroach Node=170997
       1 4892.26 5046.17
Encroach Node=170506
       1 4653.64  5039.7
Encroach Node=170019
       1  4984.5  5082.2
Encroach Node=169490
       1    4957  5039.7
Encroach Node=169002
       1  4960.3  5049.5
Encroach Node=168495
       1  4960.3  5039.7
Encroach Node=168000
       1  4958.8  5048.9
Encroach Node=167514
       1  4940.2  5041.2
Encroach Node=167002
       1  4958.8  5062.9
Encroach Node=166484
       1 4922.53  5073.2
Encroach Node=166012
       1  4947.7  5034.8
Encroach Node=165504
       1 4868.38 5040.37
Encroach Node=164993
       1 4842.11    5053
Encroach Node=164496
       1 4800.18  5044.2
Encroach Node=164013
       1 4827.58  5041.2
Encroach Node=163486
       1 4933.87 5166.33
Encroach Node=162992
       1  4723.4 5034.39
Encroach Node=162499
       1  4957.3 5077.92
Encroach Node=162012
       1  4947.1  5048.3
Encroach Node=161450
       1  4957.3  5042.7
Encroach Node=160988
       1  4951.3  5042.7
Encroach Node=160504
       1  4957.3  5042.7
Encroach Node=159999
       1    4952  5044.9
Encroach Node=159503
       1  4957.3 5031.08
Encroach Node=158998
       1  4957.3 5040.65
Encroach Node=158509
       1  4957.3  5040.5
Encroach Node=157994
       1  4957.3  5047.1
Encroach Node=157494
       1  4957.3  5042.7
Encroach Node=157003
       1 4943.64 5054.73
Encroach Node=156613
       1 4899.79 5124.21
Encroach Node=156181
       1 4615.05 5078.98
Encroach Node=155886
       1  4957.3  5042.7
Encroach Node=155493
       1 4959.68 5182.83
Encroach Node=155001
       1  4934.7  5032.8
Encroach Node=154500
       1  4951.6  5042.7
Encroach Node=154004
       1  4938.6 5057.95
Encroach Node=153502
       1  4964.3  5051.9
Encroach Node=153012
       1  4957.3  5052.8
Encroach Node=152507
       1  4949.7  5042.7
Encroach Node=151998
       1  4945.6  5042.9
Encroach Node=151504
       1  4948.9 5041.27
Encroach Node=150999
       1  4952.9  5044.4
Encroach Node=150505
       1  4952.5  5044.4
Encroach Node=150002
       1  4952.2  5049.6
Encroach Node=149486
       1  4955.6  5044.4
Encroach Node=148998
       1  4955.6  5066.3
Encroach Node=148497
       1  4955.6    5060
Encroach Node=148012
       1  4963.6  5047.3
Encroach Node=147502
       1  4955.6  5047.9
Encroach Node=146994
       1  4955.6  5051.7
Encroach Node=146524
       1  4955.6  5044.4
Encroach Node=146014
       1  4951.7    5042
Encroach Node=145501
       1  4945.8  5044.4
Encroach Node=145000
       1  4955.6  5044.4
Encroach Node=144505
       1  4955.6  5046.9
Encroach Node=144003
       1  4955.6  5049.1
Encroach Node=143519
       1  4942.1    5018
Encroach Node=143004
       1  4943.2 5300.91
Encroach Node=142496
       1  4954.6 5255.41
Encroach Node=142000
       1  4837.5  5162.5
Encroach Node=141609
       1  4962.5    5088
Encroach Node=141001
       1  4948.5  5051.5
Encroach Node=140498
       1  4945.5    5050
Encroach Node=140012
       1 4394.63  5045.4
Encroach Node=139498
       1 4736.89 5220.71
Encroach Node=138999
       1  4961.6 5306.43
Encroach Node=138500
       1  4954.6 5067.69
Encroach Node=138254
       1  4942.5  5077.5
Encroach Node=138120
       1  4922.5  5077.5
Encroach Node=137507
       1 4980.89 5157.75
Encroach Node=137002
       1 4963.32  5037.3
Encroach Node=136496
       1  4954.3  5045.7
Encroach Node=136005
       1  4944.2  5045.7
Encroach Node=135566
       1    4936  5052.8
Encroach Node=134995
       1  4952.4  5037.7
Encroach Node=134500
       1  4954.3    5060
Encroach Node=133994
       1 4940.89  5045.7
Encroach Node=133491
       1  4954.3  5030.1
Encroach Node=132997
       1  4955.7  5045.7
Encroach Node=132484
       1  4971.2  5051.1
Encroach Node=132001
       1  4954.3  5050.4
Encroach Node=131494
       1  4953.2  5045.7
Encroach Node=130987
       1  4954.3  5043.3
Encroach Node=130498
       1  4944.7  5044.8
Encroach Node=129987
       1  4954.3  5054.5
Encroach Node=129501
       1 4933.32  5045.7
Encroach Node=128988
       1 4903.87    5053
Encroach Node=128504
       1  4949.1  5049.1
Encroach Node=128008
       1    4949  5052.1
Encroach Node=127497
       1  4927.4  5066.5
Encroach Node=127031
       1 4881.92  5035.9
Encroach Node=126498
       1  4884.3  5045.7
Encroach Node=126022
       1 4951.39  5270.5
Encroach Node=125514
       1    4483  5046.4
Encroach Node=125004
       1 4435.59  5046.4
Encroach Node=124495
       1 4677.18  5121.8
Encroach Node=123996
       1 4900.66 5230.86
Encroach Node=123499
       1  4962.2 5334.84
Encroach Node=123009
       1  4970.4 5255.71
Encroach Node=122496
       1  4961.7 5060.41
Encroach Node=122000
       1 4819.57 5030.33
Encroach Node=121480
       1  4959.7    5059
Encroach Node=121000
       1  4953.6  5046.4
Encroach Node=120498
       1  4953.6  5046.4
Encroach Node=120023
       1  4953.6 5117.99
Encroach Node=119492
       1  4919.9  5052.5
Encroach Node=119005
       1  4953.6  5046.4
Encroach Node=118502
       1  4957.2    5047
Encroach Node=118011
       1  4955.9  5046.3
Encroach Node=117483
       1    4953 5037.72
Encroach Node=117005
       1  4947.5  5049.4
Encroach Node=116501
       1  4945.7    5047
Encroach Node=115999
       1  4948.9  5059.7
Encroach Node=115502
       1  4772.8 5324.98
Encroach Node=114999
       1  4946.1  5047.4
Encroach Node=114501
       1 4925.18    5047
Encroach Node=114013
       1  4745.7 5161.68
Encroach Node=113497
       1  4621.1  5036.8
Encroach Node=112988
       1  4952.2  5045.4
Encroach Node=112499
       1 4798.04 5134.26
Encroach Node=111997
       1  4944.1  5051.7
Encroach Node=111501
       1 4861.47    5047
Encroach Node=110999
       1    4958  5047.4
Encroach Node=110495
       1    4953  5072.5
Encroach Node=110003
       1  4946.6  5091.5
Encroach Node=109478
       1    4953 5039.94
Encroach Node=108997
       1  4954.5  5056.2
Encroach Node=108594
       1  4922.5  5092.8
Encroach Node=108460
       1    4895    5105
Encroach Node=107995
       1    4953    5047
Encroach Node=107285
       1    4953    5117
Encroach Node=107000
       1    4953  5059.5
Encroach Node=106486
       1 4963.35    5047
Encroach Node=106015
       1  4941.8    5073
Encroach Node=105493
       1  4933.5  5053.1
Encroach Node=104991
       1  4942.3  5051.7
Encroach Node=104496
       1    4947  5050.7
Encroach Node=104001
       1    4953    5047
Encroach Node=103500
       1    4953    5047
Encroach Node=102897
       1    4953    5037
Encroach Node=102460
       1    4953 5031.85
Encroach Node=102002
       1    4953    5047
Encroach Node=101503
       1 4964.66    5047
Encroach Node=100978
       1 4961.98 5053.12
Encroach Node=100459
       1  4928.3  5045.2
Encroach Node=99997
       1 4937.12  5052.8
Encroach Node=99496
       1 4908.15  5052.8
Encroach Node=98952
       1 4898.54  5052.9
Encroach Node=98467
       1 4646.93  5054.4
Encroach Node=98044
       1  4959.1 5187.25
Encroach Node=97508
       1  4945.6  5054.4
Encroach Node=96997
       1  4960.3 5079.61
Encroach Node=96491
       1 4907.45  5054.4
Encroach Node=96003
       1 4892.06  5054.4
Encroach Node=95549
       1 4911.35    5075
Encroach Node=95164
       1    4910  5054.4
Encroach Node=94774
       1    4890    5110
Encroach Node=94500
       1    4890    5110
Encroach Node=93986
       1    4700  5107.7
Encroach Node=93517
       1  4947.5    5333
Encroach Node=93145
       1    4922    5132
Encroach Node=92870
       1    4895    5150
Encroach Node=92717
       1    4820    5150
Encroach Node=92475
       1  4956.1    5167
Encroach Node=92000
       1  4932.3 5091.44
Encroach Node=91499
       1  4938.8 5089.66
Encroach Node=91007
       1  4940.6  5158.7
Encroach Node=90501
       1  4940.6 5063.46
Encroach Node=90005
       1  4940.6 5069.87
Encroach Node=89503
       1  4940.6 5118.73
Encroach Node=88998
       1 4939.19  5124.4
Encroach Node=88505
       1  4934.7  5053.9
Encroach Node=87996
       1 4900.11  5054.6
Encroach Node=87502
       1 4889.96  5072.7
Encroach Node=87000
       1  4925.2 5076.59
Encroach Node=86496
       1  4941.6 5100.73
Encroach Node=85991
       1  4939.9  5085.7
Encroach Node=85496
       1  4939.9 5121.16
Encroach Node=85003
       1 4926.83 5095.35
Encroach Node=84501
       1    4900 5069.04
Encroach Node=84013
       1 4811.02  5051.7
Encroach Node=83463
       1    4940  5057.7
Encroach Node=83012
       1    4940  5060.1
Encroach Node=82502
       1    4920    5080
Encroach Node=82005
       1    4890    5070
Encroach Node=81503
       1    4890    5065
Encroach Node=81000
       1    4930    5100
Encroach Node=80500
       1  4950.7    5075
Encroach Node=79998
       1    4920    5075
Encroach Node=79494
       1    4900    5080
Encroach Node=78998
       1    4900 5053.46
Encroach Node=78495
       1    4887  5073.6
Encroach Node=78002
       1    4900    5090
Encroach Node=77506
       1    4900    5085
Encroach Node=76986
       1    4850    5065
Encroach Node=76500
       1    4857    5078
Encroach Node=76012
       1    4855  5055.1
Encroach Node=75504
       1    4800  5037.6
Encroach Node=74998
       1    4808  5052.1
Encroach Node=74505
       1    4800  5052.9
Encroach Node=74012
       1    4765 5051.62
Encroach Node=73504
       1    4800    5075
Encroach Node=72998
       1    4928    5168
Encroach Node=72509
       1    4925    5165
Encroach Node=72124
       1  4890.6    5115
Encroach Node=71951
       1    4885    5115
Encroach Node=71414
       1    4950    5080
Encroach Node=70993
       1  4947.1  5049.4
Encroach Node=70486
       1  4952.5  5052.9
Encroach Node=70002
       1  4944.7  5042.8
Encroach Node=69503
       1  4957.8  5053.8
Encroach Node=69002
       1  4956.5  5055.3
Encroach Node=68503
       1  4930.4  5067.4
Encroach Node=68093
       1  4934.5 5302.74
Encroach Node=67721
       1 4817.76  5038.3
Encroach Node=67370
       1  4944.7  5050.2
Encroach Node=67014
       1  4941.6  5046.9
Encroach Node=66503
       1    4923    5068
Encroach Node=66210
       1  4944.4  5055.6
Encroach Node=65998
       1    4950 5041.31
Encroach Node=65503
       1  4944.4 5044.82
Encroach Node=64996
       1    4955  5055.6
Encroach Node=64500
       1  4944.4  5055.6
Encroach Node=63983
       1  4938.1  5049.9
Encroach Node=63488
       1 4941.34 5058.08
Encroach Node=63012
       1 4944.98 5054.67
Encroach Node=62439
       1  4944.4  5048.1
Encroach Node=61998
       1  4944.4  5055.6
Encroach Node=61496
       1  4944.4  5055.6
Encroach Node=61004
       1 4931.96  5055.6
Encroach Node=60501
       1 4917.99  5055.8
Encroach Node=60001
       1 4941.34 5138.08
Encroach Node=59504
       1 4782.64 5035.78
Encroach Node=58997
       1    4944  5050.3
Encroach Node=58502
       1  4954.1 5089.96
Encroach Node=57996
       1 4950.11 5080.08
Encroach Node=57503
       1  4953.9 5071.61
Encroach Node=56999
       1 4949.69    5056
Encroach Node=56494
       1    4944    5056
Encroach Node=55998
       1  4937.3  5052.2
Encroach Node=55501
       1    4944    5056
Encroach Node=55005
       1    4944    5056
Encroach Node=54500
       1    4850  5063.2
Encroach Node=54002
       1    4959    5075
Encroach Node=53497
       1  4948.1  5060.6
Encroach Node=52997
       1    4920    5075
Encroach Node=52508
       1  4941.4  5053.8
Encroach Node=52020
       1  4943.1  5056.9
Encroach Node=51634
       1    4915  5059.4
Encroach Node=51267
       1  4934.7  5057.5
Encroach Node=50958
       1    4895  5103.2
Encroach Node=50894
       1    4895  5086.6
Encroach Node=50497
       1  4932.2  5068.3
Encroach Node=49999
       1  4950.9    5095
Encroach Node=48993
       1    4920  5073.9
Encroach Node=48503
       1    4912  5071.3
Encroach Node=48000
       1  4933.4    5099
Encroach Node=47500
       1    4888    5128
Encroach Node=46998
       1  4950.4    5150
Encroach Node=46500
       1  4947.3    5099
Encroach Node=45996
       1    4920    5200
Encroach Node=45475
       1    4800    5130
Encroach Node=45005
       1    4722    5035
Encroach Node=44500
       1    4800    5110
Encroach Node=44010
       1    4930    5100
Encroach Node=43500
       1    4842    5075
Encroach Node=43144
       1    4885 5075.34
Encroach Node=43058
       1    4885    5085
Encroach Node=42499
       1    4820  5057.8
Encroach Node=41499
       1    4920    5130
Encroach Node=41001
       1  4951.6  5079.2
Encroach Node=40581
       1  4934.4    5130
Encroach Node=40281
       1  4914.8    5110
Encroach Node=40209
       1 4917.45    5110
Encroach Node=39989
       1  4944.6    5095
Encroach Node=39497
       1    4905 5078.76
Encroach Node=38993
       1  4944.6    5074
Encroach Node=38516
       1  4929.7  5075.8
Encroach Node=38002
       1  4946.7    5110
Encroach Node=37508
       1  4949.7  5057.8
Encroach Node=37020
       1    4891  5059.9
Encroach Node=36468
       1 4710.93 5253.16
Encroach Node=36008
       1  4931.4    5080
Encroach Node=35515
       1    4920    5065
Encroach Node=35010
       1  4924.7    5066
Encroach Node=34508
       1  4939.7  5070.7
Encroach Node=33989
       1  4934.4    5088
Encroach Node=33494
       1    4845  5063.6
Encroach Node=33000
       1  4927.7  5067.7
Encroach Node=32508
       1 4933.54  5078.6
Encroach Node=31993
       1    4927  5071.7
Encroach Node=31498
       1    4936 5068.64
Encroach Node=31003
       1 4932.19    5090
Encroach Node=30477
       1    4935    5115
Encroach Node=30014
       1  4898.5  5082.7
Encroach Node=29435
       1  4929.9  5064.4
Encroach Node=28929
       1  4902.3  5081.8
Encroach Node=28437
       1    4908  5066.1
Encroach Node=27998
       1 4938.14 5078.57
Encroach Node=27496
       1 4948.09  5065.2
Encroach Node=27010
       1    4900    5080
Encroach Node=26500
       1  4929.3  5060.8
Encroach Node=26001
       1  4935.8    5150
Encroach Node=25505
       1 4930.13    5058
Encroach Node=25012
       1    4880  5059.9
Encroach Node=24500
       1  4936.1  5072.5
Encroach Node=24007
       1  4937.8    5081
Encroach Node=23500
       1    4941  5076.5
Encroach Node=23011
       1 4920.32 5067.49
Encroach Node=22503
       1    4915    5075
Encroach Node=22015
       1    4890  5083.5
Encroach Node=21505
       1  4939.8  5072.8
Encroach Node=20995
       1  4943.7    5090
Encroach Node=20507
       1  4924.3 5075.39
Encroach Node=20010
       1    4900    5075
Encroach Node=19492
       1 4945.25    5140
Encroach Node=18989
       1  4924.5    5110
Encroach Node=18515
       1  4931.2    5170
Encroach Node=18212
       1    4865    5135
Encroach Node=18087
       1    4865    5135
Encroach Node=17755
       1    4850  5057.1
Encroach Node=17494
       1  4926.6  5056.4
Encroach Node=17004
       1 4930.62 5068.85
Encroach Node=16484
       1    4947    5180
Encroach Node=16005
       1  4936.5  5075.5
Encroach Node=15505
       1    4920 5046.73
Encroach Node=15003
       1    4895    5065
Encroach Node=14669
       1    4870 5080.27
Encroach Node=14005
       1  4928.7  5059.8
Encroach Node=13500
       1  4968.2  5120.8
Encroach Node=13009
       1  4935.6    5073
Encroach Node=12511
       1  4944.6  5082.1
Encroach Node=11988
       1  4947.4  5080.6
Encroach Node=11499
       1  4928.7  5071.3
Encroach Node=11044
       1  4928.7  5071.3
Encroach Node=10527
       1  4919.3    5076
Encroach Node=10342
       1  4928.7  5151.5
Encroach Node=9995
       1  4940.6  5082.2
Encroach Node=9726
       1  4938.1  5081.4
Encroach Node=9493
       1  4928.7  5071.3
Encroach Node=9194
       1  4932.8  5065.5
Encroach Node=9005
       1    4928  5065.8
Encroach Node=8760
       1  4928.4  5062.9
Encroach Node=8518
       1  4930.9    5072
Encroach Node=8250
       1  4925.1  5064.7
Encroach Node=7998
       1  4937.5  5062.5
Encroach Node=7508
       1  4937.5  5062.5
Encroach Node=7016
       1  4924.2    5055
Encroach Node=6557
       1    4928    5072
Encroach Node=6049
       1    4928    5072
Encroach Node=5771
       1  4932.8  5055.6
Encroach Node=5457
       1  4932.8  5067.3
Encroach Node=5000
       1    4928    5052
Encroach Node=4763
       1  4938.5    5054
Encroach Node=4499
       1  4937.5  5062.5
Encroach Node=4001
       1  4937.5  5062.5
Encroach Node=3498
       1  4937.5  5062.5
Encroach Node=3248
       1    4936  5062.5
Encroach Node=2989
       1  4930.6  5061.2
Encroach Node=2704
       1  4930.1  5062.7
Encroach Node=2500
       1  4937.3  5062.7
Encroach Node=1995
       1  4937.3  5062.7
Encroach Node=1513
       1  4932.5  5067.5
Encroach Node=1003
       1  4927.8  5072.2
Encroach Node=572
       1    4875  5113.9
Encroach Node=421
       1    4875    5125
Encroach Node=254
       1 4589.74 5471.28
BEGIN DESCRIPTION:
Floodway Run
END DESCRIPTION:
Computation Interval=1HOUR
Output Interval=1HOUR
Run HTab= 0
Run UNet= 0
Run PostProcess= 0
UNET Theta= 1
UNET Theta Warmup= 1
UNET ZTol= 0.02
UNET ZSATol= 0.05
UNET MxIter= 20
UNET MaxInSteps= 0
UNET DtIC= 0
UNET DtMin= 0
UNET MaxCRTS= 20
UNET WFStab= 2
UNET SFStab= 1
UNET WFX= 1
UNET SFX= 1
UNET DSS MLevel= 4
UNET DZMax Abort= 100
UNET Convert EG Bridges=-1
UNET Use Existing IB Tables=-1
UNET Froude Reduction=False
UNET Froude Limit= 1
UNET Froude Power= 10
Instantaneous Interval=1HOUR
Write IC File= 0
Echo Input=False
Echo Output=False
Write Detailed= 0
Detailed Automatic Start=False, 10

--- Fisher River.f01 (steady flow) ---

Flow Title=Floodway
Number of Profiles=2
Profile Names=100-year,100-FW
River Rch & RM= Fisher River,Reach-1,227005
     671     671
River Rch & RM= Fisher River,Reach-1,225489
     696     696
River Rch & RM= Fisher River,Reach-1,224003
     981     981
River Rch & RM= Fisher River,Reach-1,222999
    1002    1002
River Rch & RM= Fisher River,Reach-1,220938
    1559    1559
River Rch & RM= Fisher River,Reach-1,218256
    1825    1825
River Rch & RM= Fisher River,Reach-1,214015
    2481    2481
River Rch & RM= Fisher River,Reach-1,212517
    2898    2898
River Rch & RM= Fisher River,Reach-1,209009
    3044    3044
River Rch & RM= Fisher River,Reach-1,201510
    5621    5621
River Rch & RM= Fisher River,Reach-1,198994
    6768    6768
River Rch & RM= Fisher River,Reach-1,185477
    7192    7192
River Rch & RM= Fisher River,Reach-1,181983
    7875    7875
River Rch & RM= Fisher River,Reach-1,178010
    8235    8235
River Rch & RM= Fisher River,Reach-1,168000
    8799    8799
River Rch & RM= Fisher River,Reach-1,162499
    9357    9357
River Rch & RM= Fisher River,Reach-1,151998
   10008   10008
River Rch & RM= Fisher River,Reach-1,143004
   10490   10490
River Rch & RM= Fisher River,Reach-1,138254
   10821   10821
River Rch & RM= Fisher River,Reach-1,126022
   11546   11546
River Rch & RM= Fisher River,Reach-1,118502
   12167   12167
River Rch & RM= Fisher River,Reach-1,99997
   18484   18484
River Rch & RM= Fisher River,Reach-1,98952
   18556   18556
River Rch & RM= Fisher River,Reach-1,98467
   20236   20236
River Rch & RM= Fisher River,Reach-1,87996
   20997   20997
River Rch & RM= Fisher River,Reach-1,72124
   21224   21224
River Rch & RM= Fisher River,Reach-1,66210
   21587   21587
River Rch & RM= Fisher River,Reach-1,58997
   21970   21970
River Rch & RM= Fisher River,Reach-1,54002
   23033   23033
River Rch & RM= Fisher River,Reach-1,50958
   23106   23106
River Rch & RM= Fisher River,Reach-1,42499
   23324   23324
River Rch & RM= Fisher River,Reach-1,37020
   23428   23428
River Rch & RM= Fisher River,Reach-1,31993
   24132   24132
River Rch & RM= Fisher River,Reach-1,23011
   24258   24258
River Rch & RM= Fisher River,Reach-1,16005
   24306   24306
River Rch & RM= Fisher River,Reach-1,9005
   24389   24389
River Rch & RM= Fisher River,Reach-1,2989
   24418   24418
Boundary for River Rch & Prof#=Fisher River,Reach-1,1
Up Type=0
Dn Type=3
Dn Slope=0.0009
Boundary for River Rch & Prof#=Fisher River,Reach-1,2
Up Type=0
Dn Type=3
Dn Slope=0.0009

--- Fisher River.g01 (geometry) ---

Geom Title=Existing Conditions

River Reach=Fisher River,Reach-1
Reach XY= 30
      1448477.15      1028062.36      1454559.17      1007607.50
      1462137.56       997639.17      1460692.50       994119.63
      1464172.95       992235.49      1469724.75       982261.06
      1476921.00       979758.13      1475087.06       984935.06
      1479894.25       985659.13      1485191.04       973787.35
      1491767.88       975086.44      1492627.76       973472.47
      1501909.75       976976.56      1503026.75       972969.78
      1500204.36       970345.24      1500450.46       965556.61
      1501760.43       967880.51      1503858.60       963402.99
      1506939.13       963305.06      1503573.38       962328.06
      1506825.74       953391.91      1503430.50       947788.50
      1505449.38       942348.94      1501588.50       942675.56
      1499061.63       936945.63      1500776.50       933157.44
      1498352.67       929778.83      1498757.63       922078.63
      1501012.38       922844.75      1501147.03       920286.32

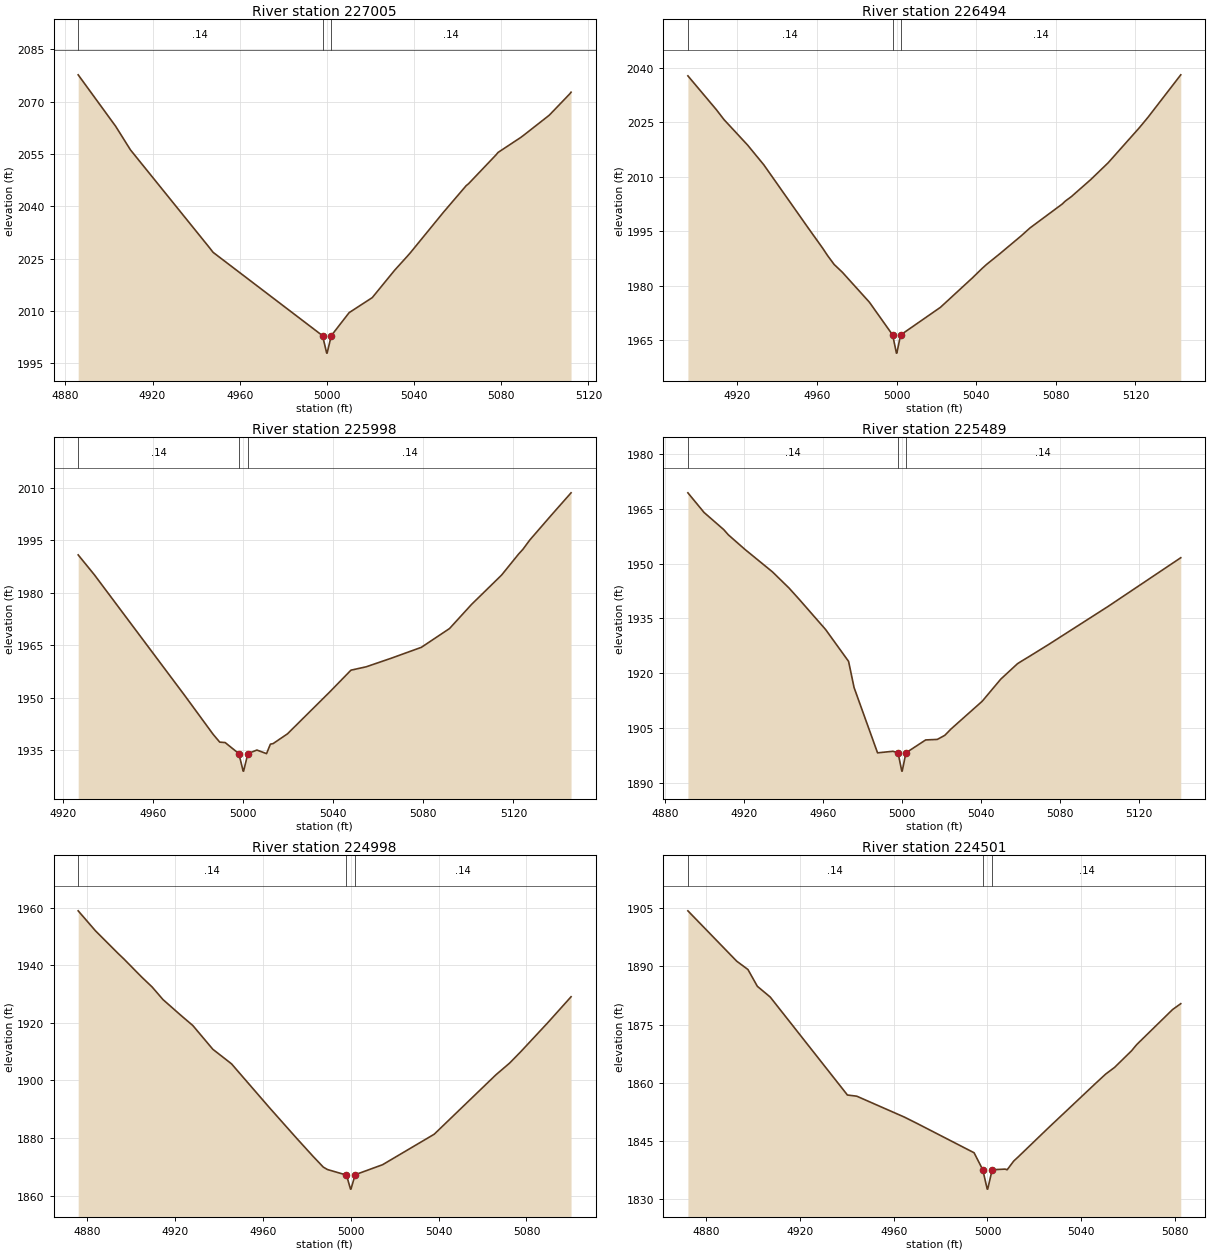
Type RM Length L Ch R = 1,227005,511,511,511
BEGIN DESCRIPTION:
Fisher River 454.0
END DESCRIPTION:
XS GIS Cut Line= 3
      1448613.67      1028065.65      1448558.89      1028040.75
      1448412.01      1027963.57
#Sta/Elev= 25
  4885.9 2077.68  4903.1 2062.92  4909.9 2056.15  4946.1 2028.14  4947.8 2026.78
  4998.0 2002.89  4999.9 1997.89  5000.1 1997.89  5002.0 2002.89  5010.2 2009.50
  5020.8 2013.80  5031.1 2021.68  5036.6 2025.47  5038.3 2026.68  5053.5 2038.31
  5063.9 2045.91  5065.0 2046.47  5077.6 2054.74  5078.0 2055.04  5078.5 2055.42
  5089.0 2059.76  5090.4 2060.42  5102.0 2066.10  5111.5 2072.28  5112.0 2072.70
#Mann=3,-1,0
  4885.9    0.14       0  4998.0    0.04       0  5002.0    0.14       0
Bank Sta=4998,5002
XS Rating Curve= 0
Exp/Cntr=0.3,0.1

Type RM Length L Ch R = 1,226494,496,496,496
BEGIN DESCRIPTION:
Fisher River 453.0
END DESCRIPTION:
XS GIS Cut Line= 4
      1448800.40      1027595.03      1448743.15      1027575.11
      1448653.51      1027540.25      1448563.84      1027525.31
#Sta/Elev= 30
  4895.1 2037.80  4909.4 2028.48  4913.3 2025.71  4925.1 2018.73  4933.3 2013.25
  4955.7 1995.78  4962.9 1990.26  4965.3 1988.28  4968.6 1985.83  4972.7 1983.70
  4986.3 1975.44  4998.0 1966.40  4999.9 1961.40  5000.1 1961.40  5002.0 1966.40
  5022.0 1974.01  5038.2 1982.19  5042.9 1984.70  5045.2 1985.84  5051.9 1988.80
  5062.7 1993.76  5067.0 1995.88  5083.2 2002.47  5084.7 2003.26  5087.9 2004.56
  5097.5 2009.19  5106.3 2013.84  5121.9 2023.45  5126.3 2026.36  5142.8 2038.08
#Mann=3,-1,0
  4895.1    0.14       0  4998.0    0.04       0  5002.0    0.14       0
Bank Sta=4998,5002
XS Rating Curve= 0
Exp/Cntr=0.3,0.1

Type RM Length L Ch R = 1,225998,509,509,509
BEGIN DESCRIPTION:
Fisher River 452.0
END DESCRIPTION:
XS GIS Cut Line= 3
      1448775.49      1027116.94      1448668.45      1027084.58
      1448561.39      1027079.60
#Sta/Elev= 28
  4926.6 1990.85  4933.8 1985.17  4974.2 1950.47  4986.6 1939.58  4989.5 1937.38
  4991.9 1937.26  4998.0 1934.10  4999.9 1929.10  5000.1 1929.10  5002.0 1934.10
  5006.0 1935.12  5010.3 1934.10  5012.0 1936.80  5013.2 1936.96  5019.6 1939.75
  5038.4 1951.73  5047.8 1957.93  5054.6 1958.90  5065.9 1961.39  5079.1 1964.46
  5091.6 1969.82  5101.4 1976.72  5114.7 1985.07  5122.3 1991.10  5124.2 1992.44
  5127.3 1995.13  5137.0 2002.32  5145.6 2008.58
#Mann=3,-1,0
  4926.6    0.14       0  4998.0    0.04       0  5002.0    0.14       0
Bank Sta=4998,5002
XS Rating Curve= 0
Exp/Cntr=0.3,0.1

Type RM Length L Ch R = 1,225489,491,491,491
BEGIN DESCRIPTION:
Fisher River 451.0
END DESCRIPTION:
XS GIS Cut Line= 3
      1449027.02      1026962.54      1449034.48      1026895.34
      1449019.54      1026713.56
#Sta/Elev= 30
  4891.4 1969.34  4899.6 1963.97  4909.6 1959.27  4911.9 1957.86  4920.4 1953.84
  4934.3 1947.72  4942.7 1943.30  4948.1 1940.07  4959.0 1933.34  4961.2 1931.99
  4972.9 1923.25  4975.7 1916.07  4987.6 1898.23  4995.4 1898.66  4998.0 1898.23
  4999.9 1893.23  5000.1 1893.23  5002.0 1898.23  5012.0 1901.76  5017.9 1901.90
  5021.7 1903.01  5024.9 1904.77  5040.7 1912.35  5050.1 1918.39  5058.6 1922.62
  5060.7 1923.33  5064.3 1924.50  5074.6 1927.94  5104.5 1938.26  5141.4 1951.59
#Mann=3,-1,0
  4891.4    0.14       0  4998.0    0.04       0  5002.0    0.14       0
Bank Sta=4998,5002
XS Rating Curve= 0
Exp/Cntr=0.3,0.1

Type RM Length L Ch R = 1,224998,497,497,497
BEGIN DESCRIPTION:
Fisher River 450.0
END DESCRIPTION:
XS GIS Cut Line= 3
      1449544.92      1026885.36      1449500.12      1026810.68
      1449403.02      1026713.58
#Sta/Elev= 28
  4875.9 1958.86  4883.8 1951.90  4894.0 1944.12  4896.6 1942.24  4904.8 1935.88
  4909.6 1932.40  4914.5 1928.06  4922.8 1922.49  4928.1 1919.05  4937.2 1910.81
  4945.7 1905.76  4963.0 1890.52  4975.4 1879.88  4982.9 1873.59  4987.5 1869.90
  4989.4 1869.06  4997.5 1867.26  4998.0 1867.26  4999.9 1862.26  5000.1 1862.26
  5002.0 1867.26  5014.5 1870.74  5038.0 1881.32  5066.1 1901.95  5072.3 1905.99
  5077.3 1909.88  5089.6 1919.94  5100.3 1929.03
#Mann=3,-1,0
  4875.9    0.14       0  4998.0    0.04       0  5002.0    0.14       0
Bank Sta=4998,5002
XS Rating Curve= 0
Exp/Cntr=0.3,0.1

Type RM Length L Ch R = 1,224501,498,498,498
BEGIN DESCRIPTION:
Fisher River 449.0
END DESCRIPTION:
XS GIS Cut Line= 3
      1449764.05      1026529.29      1449724.22      1026439.67
      1449721.73      1026327.67
#Sta/Elev= 28
  4872.3 1904.36  4893.1 1891.36  4897.9 1889.20  4901.9 1884.87  4907.4 1882.09
  4940.3 1856.79  4944.3 1856.48  4964.6 1851.08  4970.4 1849.32  4994.3 1841.87
  4998.0 1837.48  4999.9 1832.48  5000.1 1832.48  5002.0 1837.48  5007.5 1837.65
  5008.4 1837.48  5008.6 1837.64  5011.2 1839.74  5013.2 1840.86  5026.2 1848.44
  5046.6 1860.08  5050.4 1862.20  5054.2 1863.93  5061.5 1868.26  5062.9 1869.30
  5063.8 1869.92  5078.9 1878.86  5082.4 1880.38
#Mann=3,-1,0
  4872.3    0.14       0  4998.0    0.04       0  5002.0    0.14       0
Bank Sta=4998,5002
XS Rating Curve= 0
Exp/Cntr=0.3,0.1

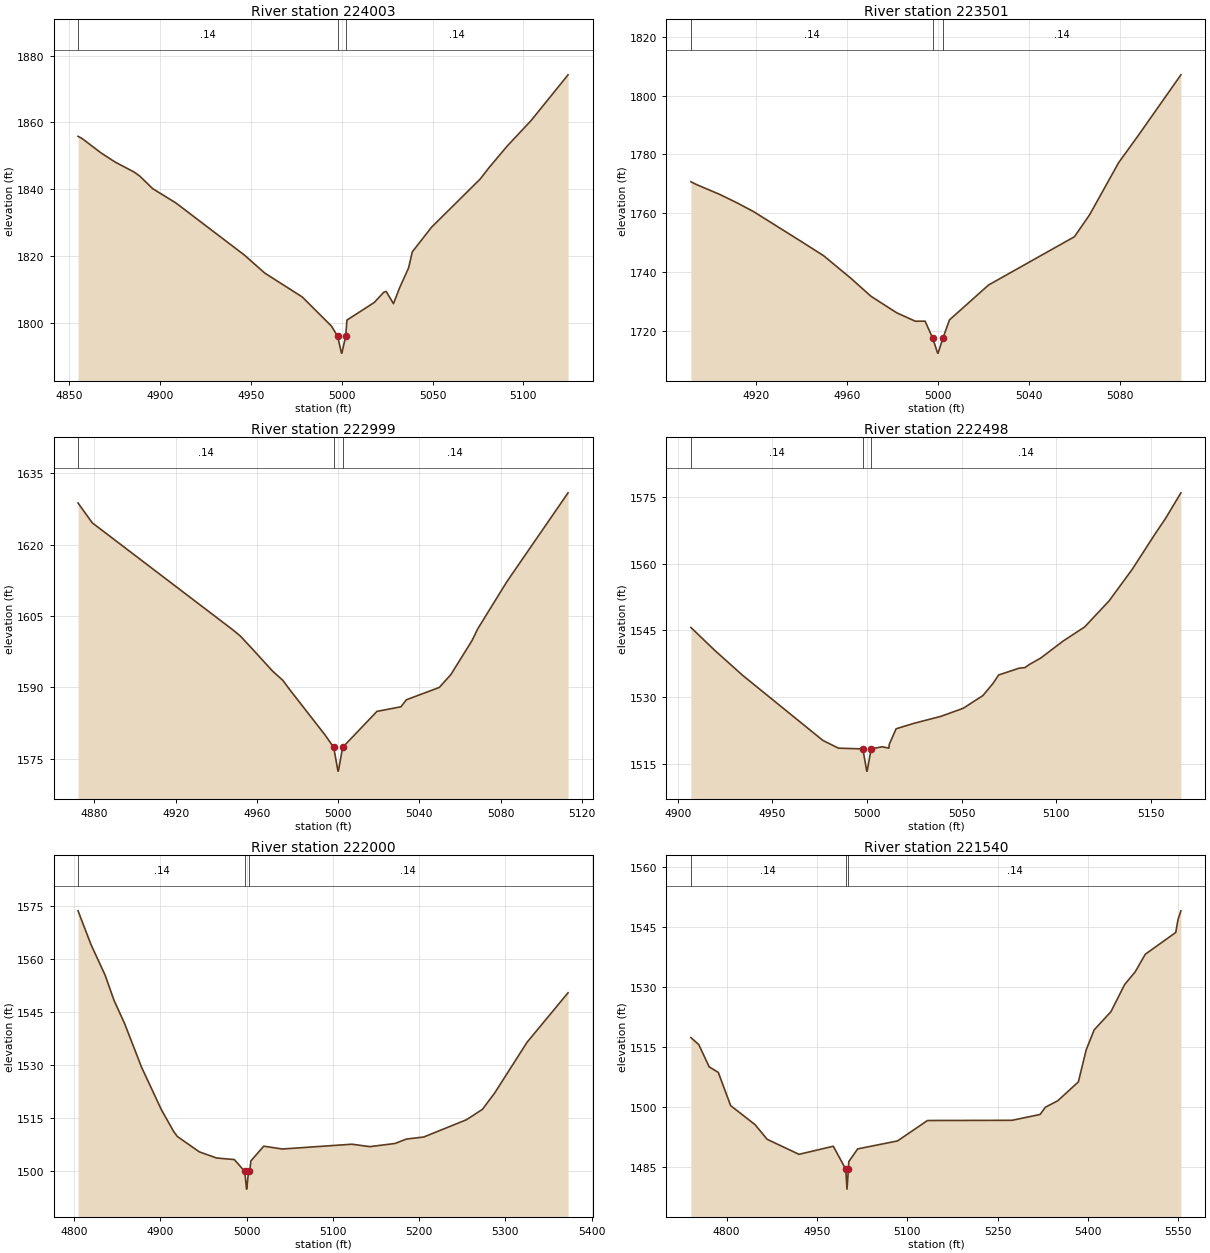
Type RM Length L Ch R = 1,224003,502,502,502
BEGIN DESCRIPTION:
Fisher River 448.0
END DESCRIPTION:
XS GIS Cut Line= 3
      1450110.15      1026188.16      1450010.57      1026118.45
      1449868.60      1026076.11
#Sta/Elev= 30
  4854.9 1855.87  4857.2 1855.19  4867.6 1850.89  4875.2 1848.21  4885.8 1845.18
  4888.9 1843.97  4896.0 1840.22  4908.7 1835.98  4946.4 1820.41  4957.7 1814.99
  4978.3 1807.86  4994.4 1799.15  4997.8 1796.08  4999.9 1791.08  5000.1 1791.08
  5002.2 1796.08  5002.9 1800.95  5017.9 1806.20  5023.2 1809.29  5024.5 1809.51
  5028.5 1805.86  5031.9 1810.62  5036.8 1816.49  5038.9 1821.37  5049.5 1828.72
  5076.3 1843.14  5081.2 1846.57  5091.2 1853.01  5104.3 1860.60  5124.6 1874.24
#Mann=3,-1,0
  4854.9    0.14       0  4997.8    0.04       0  5002.2    0.14       0
Bank Sta=4997.8,5002.2
XS Rating Curve= 0
Exp/Cntr=0.3,0.1

Type RM Length L Ch R = 1,223501,502,502,502
BEGIN DESCRIPTION:
Fisher River 447.0
END DESCRIPTION:
XS GIS Cut Line= 3
      1450249.61      1025752.41      1450212.26      1025682.70
      1450082.79      1025640.37
#Sta/Elev= 23
  4891.5 1770.71  4893.8 1769.81  4904.3 1766.36  4912.0 1763.44  4919.0 1760.57
  4940.6 1750.09  4949.9 1745.49  4961.9 1737.79  4970.6 1731.75  4981.9 1726.13
  4990.1 1723.25  4994.4 1723.27  4997.8 1717.39  4999.9 1712.39  5000.1 1712.39
  5002.2 1717.39  5005.1 1723.69  5022.3 1735.58  5060.0 1751.99  5066.7 1759.50
  5079.4 1777.16  5088.1 1786.50  5106.8 1807.10
#Mann=3,-1,0
  4891.5    0.14       0  4997.8    0.04       0  5002.2    0.14       0
Bank Sta=4997.8,5002.2
XS Rating Curve= 0
Exp/Cntr=0.3,0.1

Type RM Length L Ch R = 1,222999,501,501,501
BEGIN DESCRIPTION:
Fisher River 446.0
END DESCRIPTION:
XS GIS Cut Line= 3
      1450364.18      1025179.70      1450286.96      1025217.07
      1450175.00      1025325.00
#Sta/Elev= 24
  4871.9 1628.79  4878.9 1624.62  4947.7 1602.24  4950.7 1601.20  4951.0 1601.09
  4951.9 1600.76  4957.7 1598.10  4967.6 1593.46  4972.8 1591.45  4976.0 1589.60
  4993.5 1580.00  4997.8 1577.37  4999.9 1572.37  5000.1 1572.37  5002.2 1577.37
  5019.1 1584.94  5030.9 1585.91  5033.6 1587.39  5049.8 1589.98  5055.5 1592.69
  5065.9 1599.83  5068.7 1602.29  5083.0 1612.19  5113.2 1630.93
#Mann=3,-1,0
  4871.9    0.14       0  4997.8    0.04       0  5002.2    0.14       0
Bank Sta=4997.8,5002.2
XS Rating Curve= 0
Exp/Cntr=0.3,0.1

Type RM Length L Ch R = 1,222498,498,498,498
BEGIN DESCRIPTION:
Fisher River 445.0
END DESCRIPTION:
XS GIS Cut Line= 3
      1450286.98      1024873.45      1450217.24      1024858.50
      1450030.52      1024838.59
#Sta/Elev= 30
  4906.9 1545.68  4919.3 1540.61  4934.3 1534.89  4976.7 1520.25  4984.9 1518.51
  4997.8 1518.34  4999.9 1513.34  5000.1 1513.34  5002.2 1518.34  5008.0 1518.82
  5011.6 1518.52  5011.8 1519.38  5015.4 1522.87  5024.9 1524.11  5039.0 1525.66
  5050.9 1527.49  5061.3 1530.35  5066.6 1533.06  5069.6 1534.98  5080.5 1536.52
  5083.5 1536.65  5086.0 1537.38  5091.9 1538.80  5103.7 1542.62  5115.1 1545.80
  5128.0 1551.65  5140.3 1558.80  5152.5 1566.84  5157.8 1570.18  5166.0 1575.99
#Mann=3,-1,0
  4906.9    0.14       0  4997.8    0.04       0  5002.2    0.14       0
Bank Sta=4997.8,5002.2
XS Rating Curve= 0
Exp/Cntr=0.3,0.1

Type RM Length L Ch R = 1,222000,460,460,460
BEGIN DESCRIPTION:
Fisher River 444.0
END DESCRIPTION:
XS GIS Cut Line= 3
      1450446.30      1024522.32      1450359.17      1024390.38
      1449960.75      1024293.26
#Sta/Elev= 30
  4804.5 1573.64  4819.5 1564.11  4835.9 1555.44  4846.3 1548.27  4858.3 1541.86
  4878.2 1529.37  4901.2 1517.35  4915.4 1511.20  4919.6 1509.81  4945.1 1505.45
  4965.1 1503.71  4985.8 1503.26  4997.8 1499.90  4999.9 1494.90  5000.1 1494.90
  5002.2 1499.90  5003.6 1499.90  5004.9 1502.87  5019.8 1507.05  5041.5 1506.25
  5122.1 1507.61  5142.7 1506.92  5172.0 1507.81  5185.3 1509.06  5205.4 1509.65
  5254.9 1514.53  5273.4 1517.47  5287.6 1522.09  5325.2 1536.46  5372.7 1550.46
#Mann=3,-1,0
  4804.5    0.14       0  4997.8    0.04       0  5002.2    0.14       0
Bank Sta=4997.8,5002.2
XS Rating Curve= 0
Exp/Cntr=0.3,0.1

Type RM Length L Ch R = 1,221540,220,220,220
BEGIN DESCRIPTION:
Fisher River 443.0
END DESCRIPTION:
XS GIS Cut Line= 4
      1450695.35      1024146.38      1450570.82      1024021.86
      1450428.89      1024041.78      1449940.88      1024121.45
#Sta/Elev= 30
  4740.6 1517.34  4753.7 1515.58  4771.0 1510.02  4786.1 1508.64  4806.6 1500.34
  4847.2 1495.57  4867.2 1491.92  4920.1 1488.16  4977.1 1490.18  4997.8 1484.46
  4999.9 1479.46  5002.2 1484.46  5002.8 1486.32  5017.5 1489.51  5083.7 1491.50
  5133.6 1496.61  5274.0 1496.66  5320.5 1498.12  5329.6 1499.95  5350.1 1501.56
  5384.2 1506.27  5397.1 1514.24  5410.5 1519.28  5438.3 1523.81  5461.0 1530.59
  5478.6 1533.78  5495.3 1538.16  5545.9 1543.61  5549.8 1546.92  5554.5 1549.02
#Mann=3,-1,0
  4740.6    0.14       0  4997.8    0.04       0  5002.2    0.14       0
Bank Sta=4997.8,5002.2
XS Rating Curve= 0
Exp/Cntr=0.5,0.3