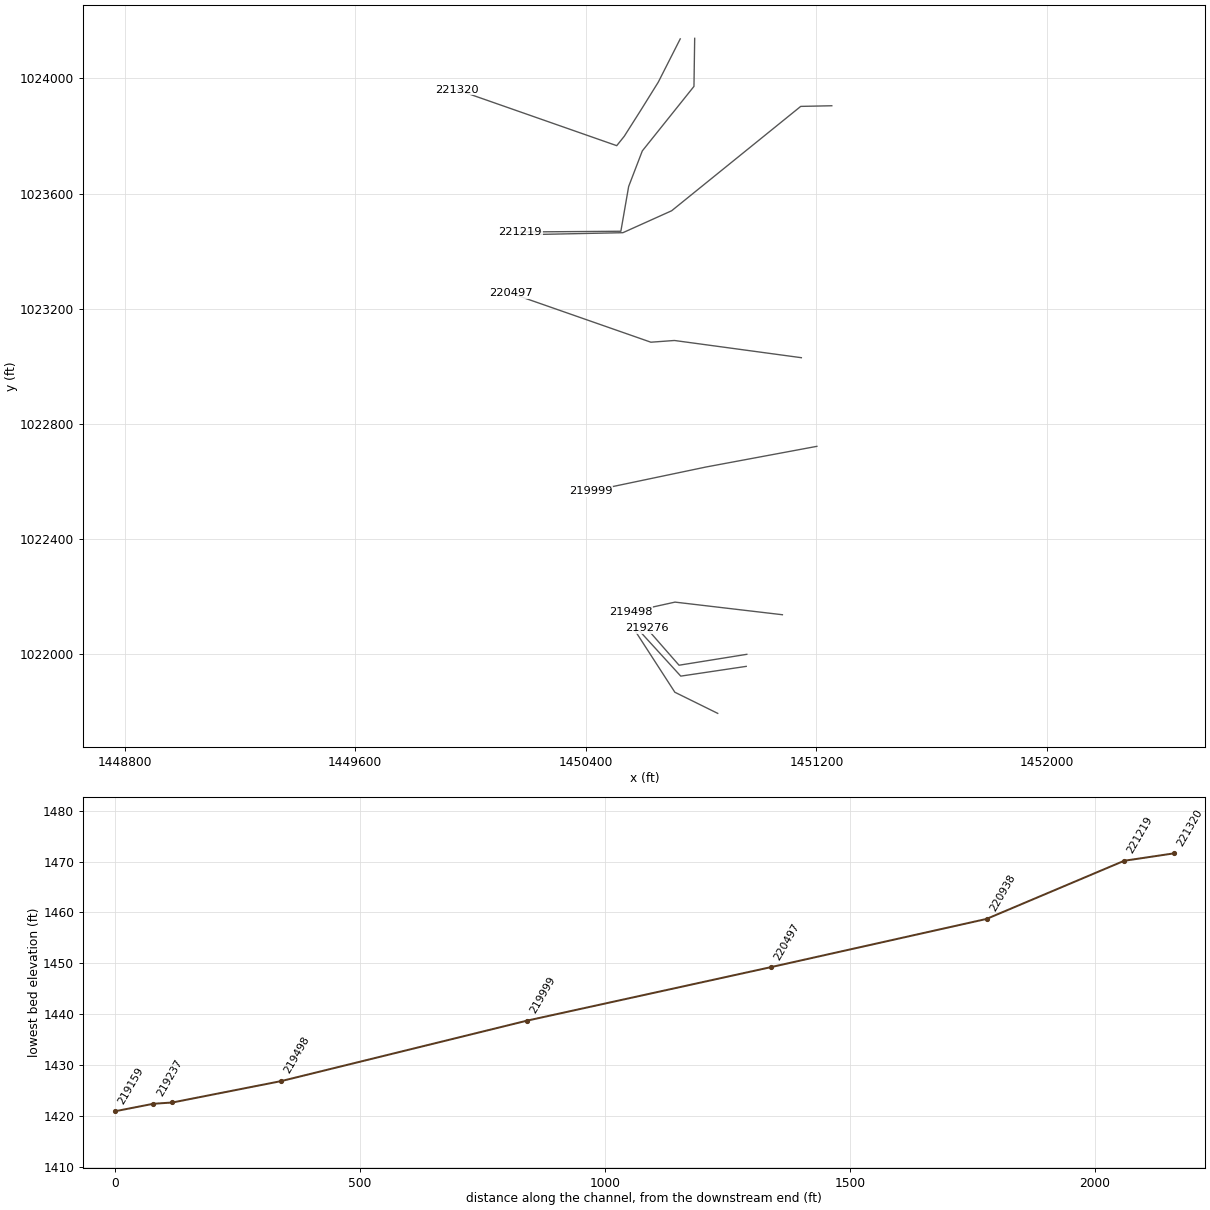
HEC-RAS study Fisher River.prj: Fisher River Limited Detail Study

--- Fisher River.g01 (geometry) --- (continued)

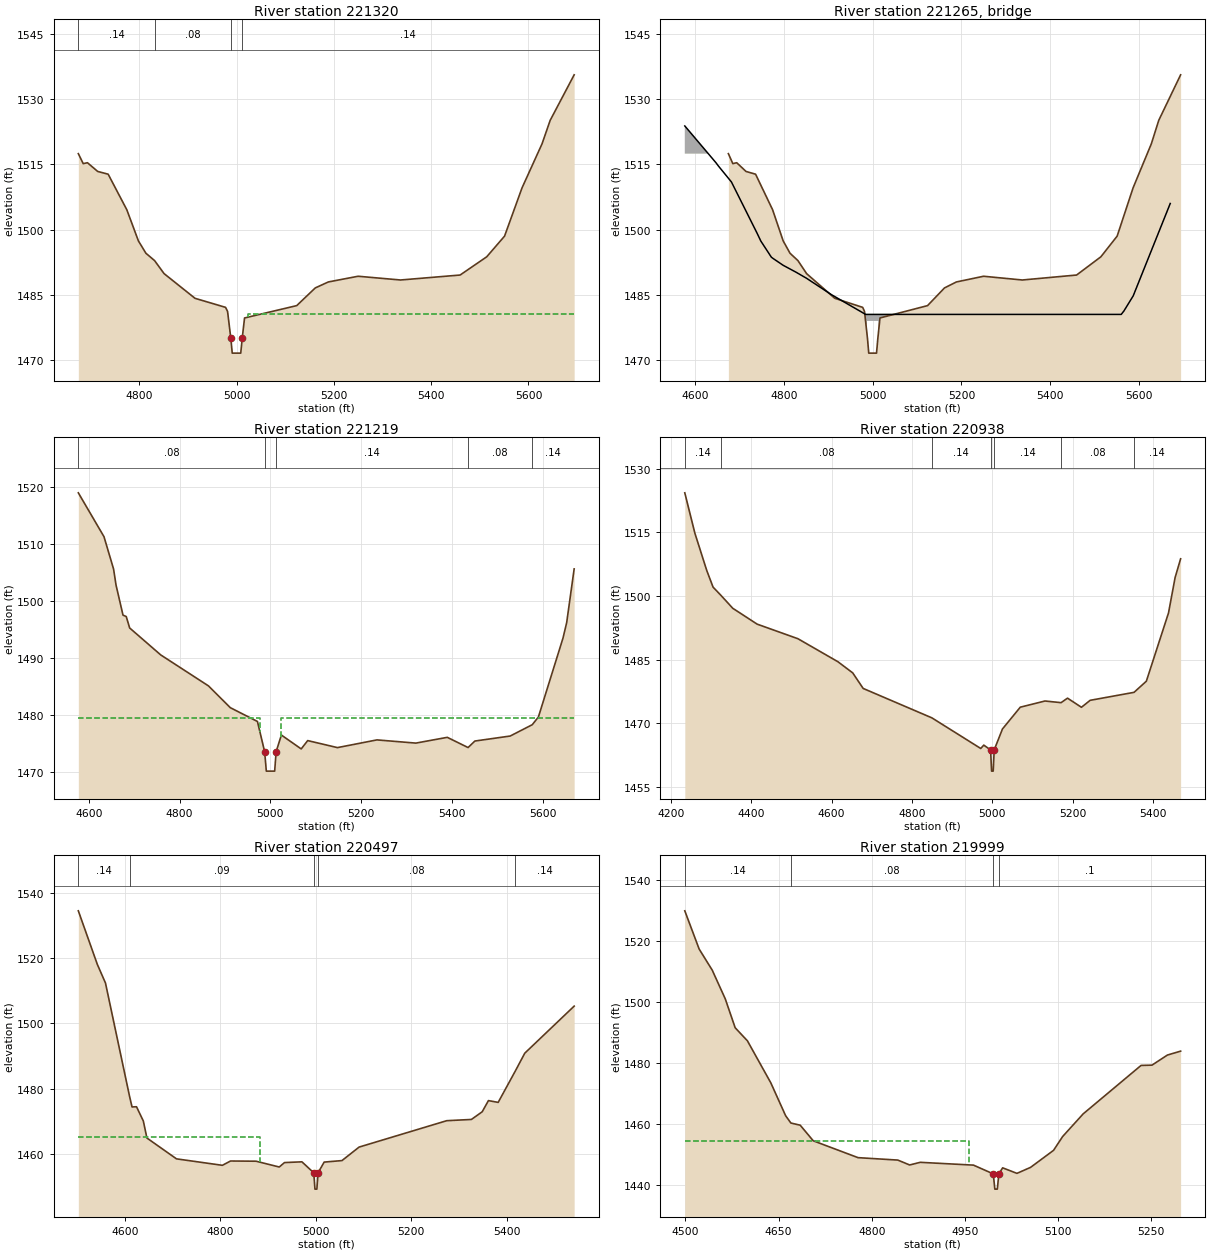
Type RM Length L Ch R = 1,221320,101,101,101
BEGIN DESCRIPTION:
Lumber Plant Rd (2) - US
END DESCRIPTION:
XS GIS Cut Line= 6
      1450727.41      1024137.00      1450651.08      1023986.53
      1450590.02      1023888.39      1450533.32      1023798.97
      1450507.14      1023766.26      1449953.24      1023960.34
#Sta/Elev= 30
  4674.9 1517.45  4685.0 1515.15  4693.6 1515.37  4714.7 1513.36  4736.2 1512.73
  4774.5 1504.57  4798.4 1497.39  4813.8 1494.56  4831.6 1492.87  4851.1 1489.88
  4914.7 1484.20  4977.5 1482.12  4981.6 1481.19  4988.3 1475.00  4991.2 1471.60
  5008.7 1471.60  5011.7 1475.00  5016.5 1479.68  5123.7 1482.52  5161.9 1486.59
  5188.7 1487.96  5249.9 1489.27  5337.1 1488.41  5459.5 1489.55  5514.2 1493.74
  5550.9 1498.50  5586.8 1509.59  5627.9 1519.71  5644.6 1525.10  5693.9 1535.57
#Mann=4,-1,0
  4674.9    0.14       0  4831.6    0.08       0  4988.3    0.04       0
  5011.7    0.14       0
#XS Ineff=2,0
    0.00 4977.00 1480.50 5023.00    0.00 1480.50
Permanent Ineff=
       F       F
Bank Sta=4988.3,5011.7
XS Rating Curve= 0
Exp/Cntr=0.5,0.3

Type RM Length L Ch R =3,221265,,,
BEGIN DESCRIPTION:
Lumber Plant Rd (2) - TOR
Structure ID: LDS_FR_26
Approximate Survey Structure
END DESCRIPTION:
Bridge Culvert--1,0,-1,-1,0
Deck Dist Width WeirC Skew NumUp NumDn MinLoCord MaxHiCord MaxSubmerge Is_Ogee
21.5,21,3,,22,22,,,0.95,0,1,1,,,
  4576.7  4646.7  4653.0  4681.8  4739.6  4747.9  4771.7  4775.7  4798.3  4827.7
  4851.4  4907.3  4984.2  4987.0  4987.0  5013.0  5013.0  5560.1  5564.0  5565.7
  5587.1  5670.5
 1523.82 1515.39 1514.54 1510.94 1499.16 1497.38 1493.66 1493.35 1491.79 1490.18
 1488.78 1485.03 1480.50 1480.50 1480.50 1480.50 1480.50 1480.50 1481.02 1481.22
 1484.77 1506.00
 1450.60 1450.60 1450.60 1450.60 1450.60 1450.60 1450.60 1450.60 1450.60 1450.60
 1450.60 1450.60 1450.60 1450.60 1479.00 1479.00 1450.60 1450.60 1450.60 1450.60
 1450.60 1450.60
  4576.7  4646.7  4653.0  4681.8  4739.6  4747.9  4771.7  4775.7  4798.3  4827.7
  4851.4  4907.3  4984.2  4987.0  4987.0  5013.0  5013.0  5560.1  5564.0  5565.7
  5587.1  5670.5
 1523.82 1515.39 1514.54 1510.94 1499.16 1497.38 1493.66 1493.35 1491.79 1490.18
 1488.78 1485.03 1480.50 1480.50 1480.50 1480.50 1480.50 1480.50 1481.02 1481.22
 1484.77 1506.00
 1450.60 1450.60 1450.60 1450.60 1450.60 1450.60 1450.60 1450.60 1450.60 1450.60
 1450.60 1450.60 1450.60 1450.60 1479.00 1479.00 1450.60 1450.60 1450.60 1450.60
 1450.60 1450.60
BR Coef=1,1,0,1.25,0,,,0.8,0,2,0,
WSPro=,,,, 1 ,,,, 0 ,,,, 0 ,,,,-1 ,-1 ,-1 , 0 , 0 , 0 , 0 , 0
BC Design=,,0,,0,,,,,,

Type RM Length L Ch R = 1,221219,281,281,281
BEGIN DESCRIPTION:
Lumber Plant Rd (2) - DS
END DESCRIPTION:
XS GIS Cut Line= 6
      1450777.50      1024138.91      1450775.01      1023972.06
      1450595.85      1023748.05      1450548.52      1023624.64
      1450521.47      1023469.12      1450172.41      1023466.58
#Sta/Elev= 30
  4576.6 1518.91  4633.2 1511.22  4654.3 1505.56  4659.7 1502.76  4675.1 1497.48
  4682.2 1497.24  4689.8 1495.23  4758.3 1490.51  4863.6 1485.08  4911.6 1481.27
  4971.5 1478.85  4987.4 1473.55  4991.1 1470.15  5009.5 1470.15  5012.7 1473.55
  5024.3 1476.47  5068.0 1474.04  5082.3 1475.50  5147.9 1474.27  5235.0 1475.62
  5320.7 1475.06  5390.1 1476.07  5435.9 1474.28  5450.9 1475.42  5528.8 1476.30
  5577.4 1478.28  5591.0 1479.64  5645.2 1493.46  5653.3 1496.16  5669.8 1505.58
#Mann=5,-1,0
  4576.6    0.08       0  4987.4    0.04       0  5012.7    0.14       0
  5435.9    0.08       0  5577.4    0.14       0
#XS Ineff=2,0
    0.00 4977.00 1479.50 5023.00    0.00 1479.50
Permanent Ineff=
       F       F
Bank Sta=4987.4,5012.7
XS Rating Curve= 0
Exp/Cntr=0.5,0.3

Type RM Length L Ch R = 1,220938,441,441,441
BEGIN DESCRIPTION:
Fisher River 442.0
END DESCRIPTION:
XS GIS Cut Line= 5
      1451253.08      1023904.83      1451145.32      1023902.61
      1450697.64      1023540.27      1450528.49      1023464.09
      1450165.00      1023456.62
#Sta/Elev= 30
  4235.2 1524.31  4260.2 1514.82  4289.8 1506.00  4305.5 1502.08  4324.7 1500.18
  4354.4 1497.10  4415.0 1493.36  4516.5 1489.92  4615.7 1484.51  4652.7 1481.87
  4678.7 1478.20  4849.5 1471.27  4971.0 1464.05  4978.6 1464.84  4995.5 1463.71
  4998.0 1458.71  5002.0 1458.71  5004.5 1463.71  5025.0 1468.64  5069.3 1473.78
  5130.7 1475.24  5170.7 1474.85  5186.8 1475.91  5221.4 1473.76  5243.1 1475.40
  5352.2 1477.28  5382.8 1479.91  5437.9 1496.00  5454.3 1504.35  5468.0 1508.76
#Mann=7,-1,0
  4235.2    0.14       0  4324.7    0.08       0  4849.5    0.14       0
  4995.5    0.04       0  5004.5    0.14       0  5170.7    0.08       0
  5352.2    0.14       0
Bank Sta=4995.5,5004.5
XS Rating Curve= 0
Exp/Cntr=0.3,0.1

Type RM Length L Ch R = 1,220497,498,498,498
BEGIN DESCRIPTION:
Fisher River 441.0
END DESCRIPTION:
XS GIS Cut Line= 4
      1451147.47      1023030.09      1450707.28      1023089.84
      1450625.60      1023083.87      1450141.59      1023253.18
#Sta/Elev= 30
  4502.2 1534.53  4542.0 1518.12  4559.1 1512.39  4609.5 1477.69  4614.7 1474.41
  4624.1 1474.46  4638.4 1470.10  4645.9 1464.88  4707.9 1458.49  4804.0 1456.51
  4821.1 1457.83  4874.5 1457.77  4923.2 1455.99  4934.2 1457.35  4970.7 1457.58
  4995.5 1454.21  4998.0 1449.21  5002.0 1449.21  5004.5 1454.21  5017.3 1457.50
  5054.6 1457.96  5090.5 1462.10  5274.1 1470.19  5325.8 1470.57  5348.4 1472.92
  5361.5 1476.35  5381.9 1475.80  5417.4 1485.31  5437.6 1490.88  5541.1 1505.31
#Mann=5,-1,0
  4502.2    0.14       0  4609.5    0.09       0  4995.5    0.04       0
  5004.5    0.08       0  5417.4    0.14       0
#XS Ineff=2,0
    0.00 4881.90 1465.06               0
Permanent Ineff=
       F       F
Bank Sta=4995.5,5004.5
XS Rating Curve= 0
Exp/Cntr=0.3,0.1

Type RM Length L Ch R = 1,219999,501,501,501
BEGIN DESCRIPTION:
Fisher River 440.0
END DESCRIPTION:
XS GIS Cut Line= 3
      1451201.29      1022722.32      1450816.84      1022650.60
      1450418.41      1022566.94
#Sta/Elev= 30
  4498.9 1529.93  4522.0 1517.40  4543.1 1510.47  4564.1 1501.04  4580.0 1491.59
  4599.7 1487.31  4637.4 1473.52  4661.2 1462.76  4669.7 1460.35  4684.7 1459.64
  4705.7 1454.53  4777.8 1449.00  4841.9 1448.20  4860.9 1446.60  4877.9 1447.47
  4963.6 1446.55  4995.5 1443.68  4998.0 1438.68  5002.0 1438.68  5004.5 1443.68
  5010.6 1445.66  5033.6 1443.85  5055.5 1445.81  5092.5 1451.39  5107.2 1455.93
  5140.2 1463.35  5233.4 1479.24  5251.0 1479.33  5275.8 1482.64  5297.1 1483.92
#Mann=4,-1,0
  4498.9    0.14       0  4669.7    0.08       0  4995.5    0.04       0
  5004.5     0.1       0
#XS Ineff=2,0
    0.00 4957.10 1454.32               0
Permanent Ineff=
       F       F
Bank Sta=4995.5,5004.5
XS Rating Curve= 0
Exp/Cntr=0.3,0.1

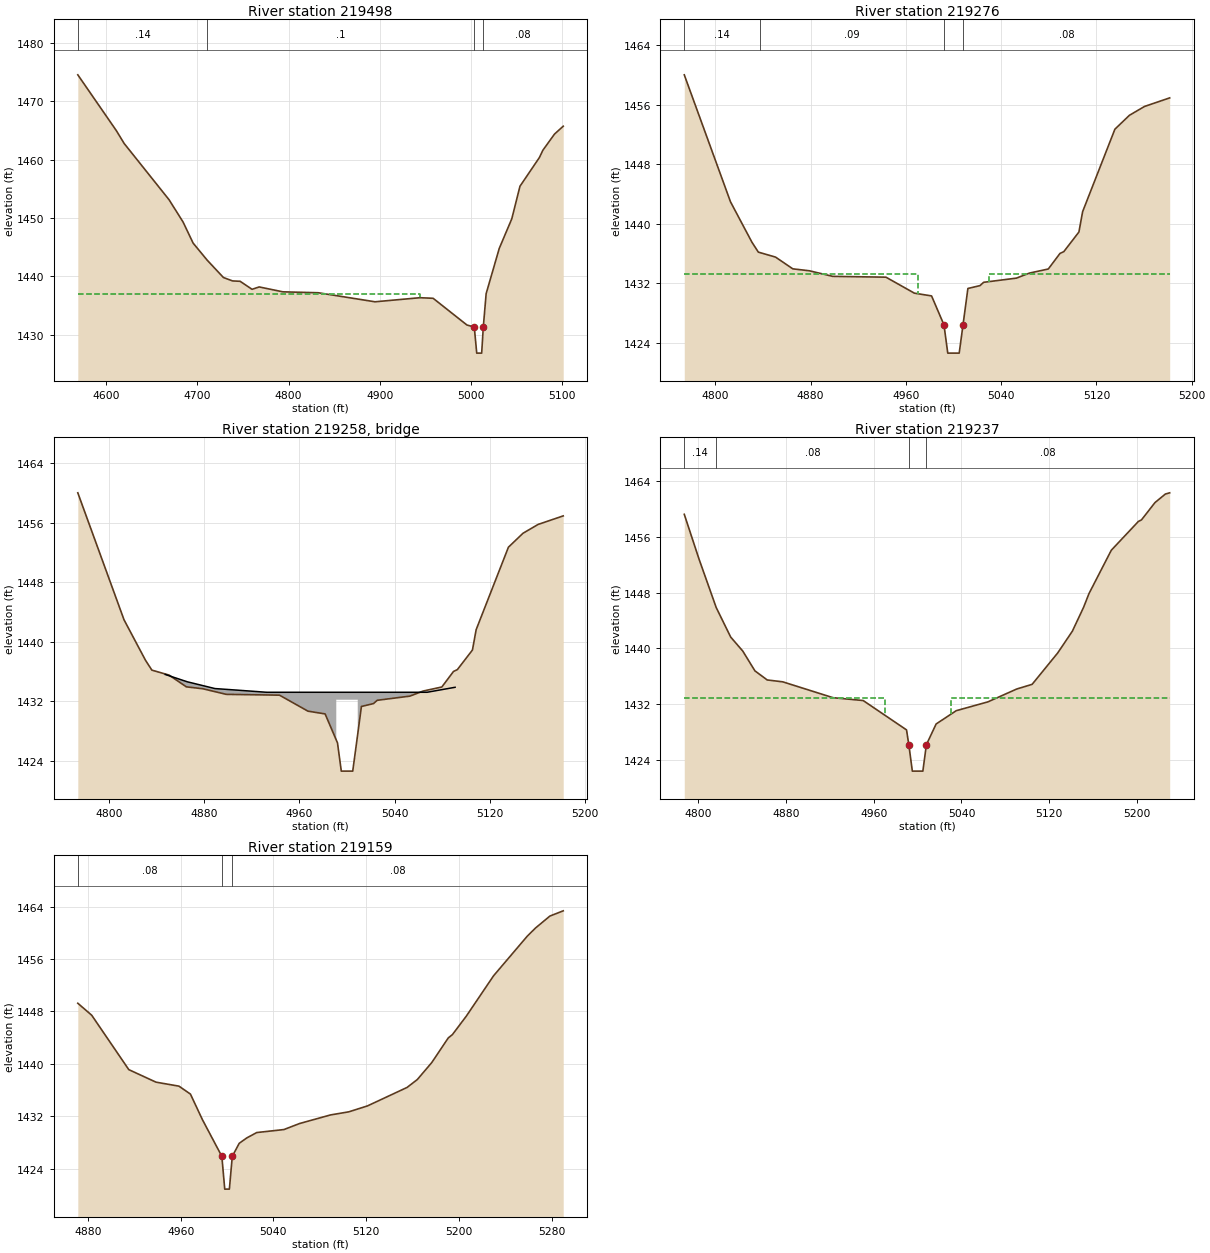
Type RM Length L Ch R = 1,219498,222,222,222
BEGIN DESCRIPTION:
Fisher River 439.0
END DESCRIPTION:
XS GIS Cut Line= 3
      1451081.74      1022137.67      1450709.27      1022181.49
      1450555.90      1022147.63
#Sta/Elev= 30
  4568.9 1474.57  4611.2 1464.98  4619.7 1462.79  4668.9 1453.14  4684.3 1449.31
  4695.3 1445.69  4710.8 1442.75  4728.5 1439.79  4738.5 1439.20  4746.8 1439.14
  4759.9 1437.76  4767.7 1438.17  4793.6 1437.33  4832.5 1437.17  4894.7 1435.62
  4943.9 1436.32  4958.4 1436.22  4995.4 1431.64  5003.5 1431.28  5006.2 1426.81
  5011.6 1426.81  5013.4 1431.28  5016.5 1437.01  5030.9 1444.79  5044.6 1449.85
  5053.6 1455.45  5074.9 1460.38  5078.7 1461.63  5091.5 1464.41  5101.0 1465.75
#Mann=4,-1,0
  4568.9    0.14       0  4710.8     0.1       0  5003.5    0.04       0
  5013.4    0.08       0
#XS Ineff=2,0
    0.00 4943.90 1436.90               0
Permanent Ineff=
       F       F
Bank Sta=5003.5,5013.4
XS Rating Curve= 0
Exp/Cntr=0.5,0.3

Type RM Length L Ch R = 1,219276,39,39,39
BEGIN DESCRIPTION:
Off Lumber Plant Rd (3) - US
END DESCRIPTION:
XS GIS Cut Line= 3
      1450958.26      1022000.21      1450723.21      1021962.36
      1450611.64      1022089.87
#Sta/Elev= 30
  4774.0 1460.01  4812.8 1442.94  4830.8 1437.51  4836.2 1436.17  4837.4 1436.12
  4850.6 1435.51  4865.1 1433.93  4879.0 1433.67  4898.6 1432.92  4943.3 1432.81
  4967.2 1430.66  4981.6 1430.29  4992.0 1426.40  4995.2 1422.60  5004.8 1422.60
  5008.0 1426.40  5012.1 1431.29  5022.3 1431.68  5025.3 1432.12  5052.8 1432.68
  5063.8 1433.36  5079.6 1433.91  5089.4 1436.00  5092.6 1436.24  5105.3 1438.88
  5108.4 1441.61  5135.5 1452.70  5147.7 1454.57  5160.4 1455.76  5181.5 1456.91
#Mann=4,-1,0
  4774.0    0.14       0  4837.4    0.09       0  4992.0    0.04       0
  5008.0    0.08       0
#XS Ineff=2,0
    0.00 4970.00 1433.20 5030.00    0.00 1433.20
Permanent Ineff=
       F       F
Bank Sta=4992,5008
XS Rating Curve= 0
Exp/Cntr=0.5,0.3

Type RM Length L Ch R =3,219258,,,
BEGIN DESCRIPTION:
Off LumberPlant  Rd (3) - TOR
Structure ID: LDS_FR_25C
Approximate Survey Structure
END DESCRIPTION:
Bridge Culvert--1,0,-1,-1,0
Deck Dist Width WeirC Skew NumUp NumDn MinLoCord MaxHiCord MaxSubmerge Is_Ogee
17,2,3,,11,11,,,0.95,0,1,1,,,
  4847.4  4865.9  4889.1  4908.5  4932.5  4991.0  4991.0  5009.0  5009.0  5067.2
  5090.7
 1435.59 1434.61 1433.70 1433.48 1433.20 1433.20 1433.20 1433.20 1433.20 1433.20
 1433.87
 1402.60 1402.60 1402.60 1402.60 1402.60 1402.60 1432.20 1432.20 1402.60 1402.60
 1402.60
  4847.4  4865.9  4889.1  4908.5  4932.5  4991.0  4991.0  5009.0  5009.0  5067.2
  5090.7
 1435.59 1434.61 1433.70 1433.48 1433.20 1433.20 1433.20 1433.20 1433.20 1433.20
 1433.87
 1402.60 1402.60 1402.60 1402.60 1402.60 1402.60 1432.20 1432.20 1402.60 1402.60
 1402.60
BR Coef=1,1,0,1.25,0,,,0.8,0,2,0,
WSPro=,,,, 1 ,,,, 0 ,,,, 0 ,,,,-1 ,-1 ,-1 , 0 , 0 , 0 , 0 , 0
BC Design=,,0,,0,,,,,,

Type RM Length L Ch R = 1,219237,78,78,78
BEGIN DESCRIPTION:
Off Lumber Rd Plant (3) - DS
END DESCRIPTION:
XS GIS Cut Line= 3
      1450956.28      1021958.38      1450729.19      1021924.52
      1450585.78      1022081.87
#Sta/Elev= 30
  4787.3 1459.28  4800.8 1452.82  4816.4 1445.88  4829.6 1441.63  4840.6 1439.62
  4851.7 1436.77  4862.9 1435.46  4877.1 1435.19  4922.9 1432.91  4950.4 1432.50
  4989.9 1428.28  4992.0 1426.15  4995.2 1422.35  5004.8 1422.35  5008.0 1426.15
  5016.9 1429.13  5035.2 1431.04  5064.1 1432.31  5090.4 1434.16  5104.4 1434.83
  5127.7 1439.34  5141.1 1442.48  5151.4 1445.94  5156.2 1447.87  5176.6 1454.12
  5201.3 1458.26  5204.1 1458.48  5216.4 1460.97  5225.9 1462.20  5229.8 1462.37
#Mann=4,-1,0
  4787.3    0.14       0  4816.4    0.08       0  4992.0    0.04       0
  5008.0    0.08       0
#XS Ineff=2,0
    0.00 4970.00 1432.80 5030.00    0.00 1432.80
Permanent Ineff=
       F       F
Bank Sta=4992,5008
XS Rating Curve= 0
Exp/Cntr=0.5,0.3

Type RM Length L Ch R = 1,219159,165,165,165
BEGIN DESCRIPTION:
Fisher River 438.0
END DESCRIPTION:
XS GIS Cut Line= 3
      1450857.40      1021795.18      1450708.73      1021868.57
      1450571.39      1022081.16
#Sta/Elev= 30
  4871.2 1449.24  4883.2 1447.41  4915.2 1439.11  4938.7 1437.20  4958.5 1436.59
  4968.4 1435.38  4978.7 1431.49  4995.5 1425.88  4998.0 1420.88  5002.0 1420.88
  5004.5 1425.88  5010.5 1427.87  5017.0 1428.69  5025.6 1429.51  5049.1 1429.97
  5062.6 1430.89  5089.3 1432.20  5105.0 1432.67  5121.1 1433.57  5155.3 1436.39
  5164.2 1437.60  5176.7 1440.20  5190.9 1443.95  5194.5 1444.46  5206.5 1447.28
  5230.0 1453.43  5259.1 1459.48  5266.2 1460.72  5278.6 1462.54  5290.1 1463.34
#Mann=3,-1,0
  4871.2    0.08       0  4995.5    0.04       0  5004.5    0.08       0
Bank Sta=4995.5,5004.5
XS Rating Curve= 0
Exp/Cntr=0.5,0.3