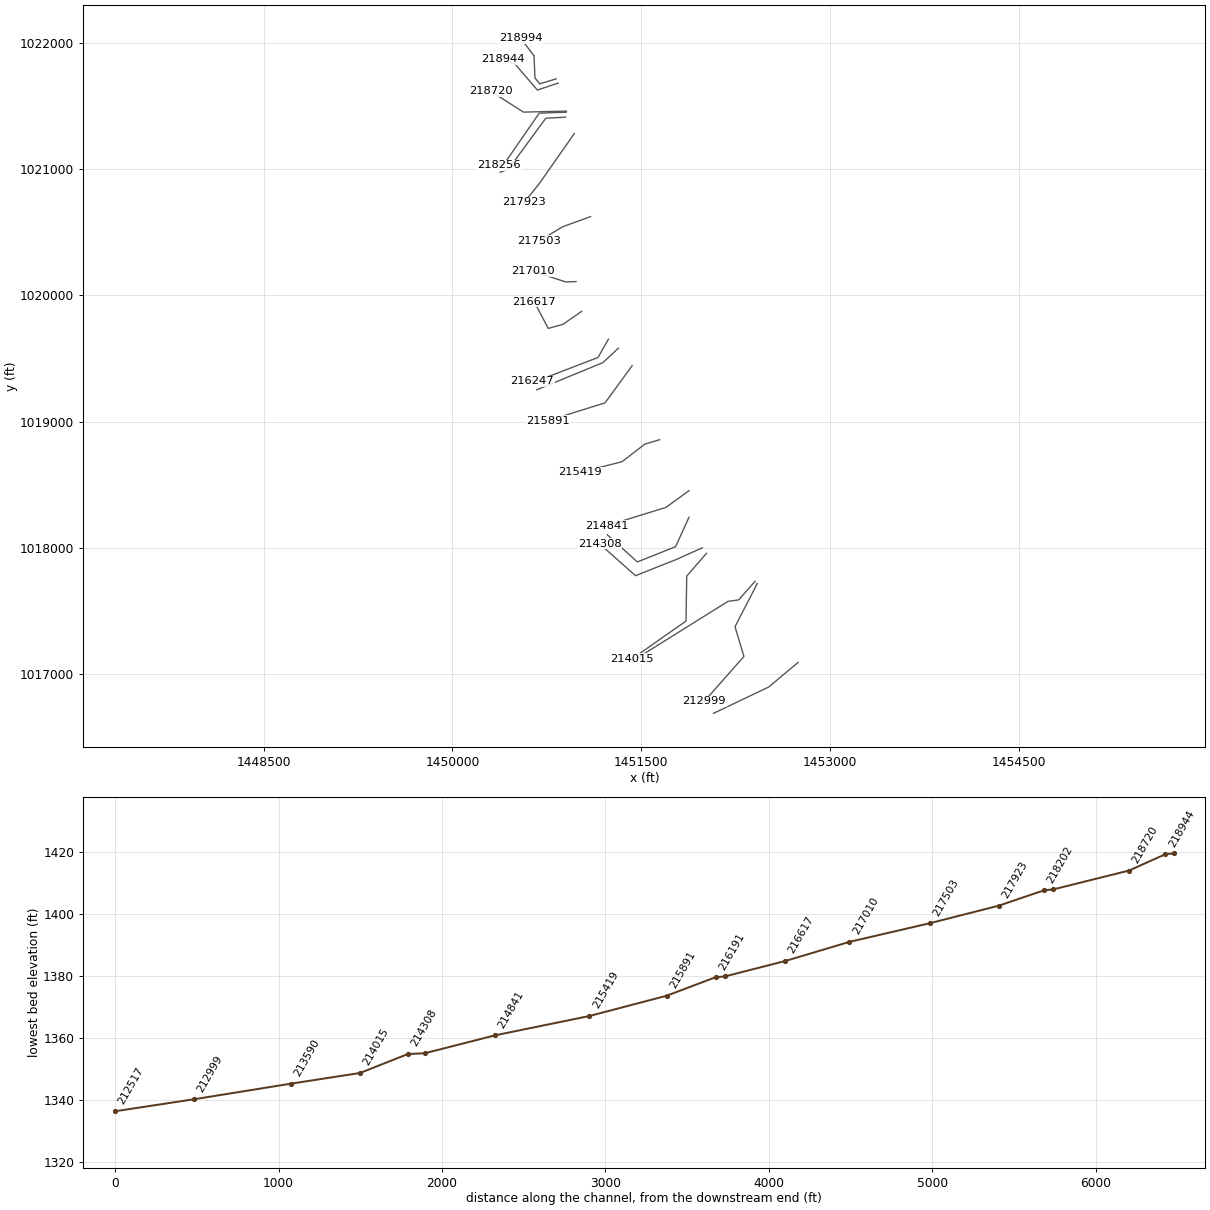
HEC-RAS study Fisher River.prj: Fisher River Limited Detail Study

--- Fisher River.g01 (geometry) --- (continued)

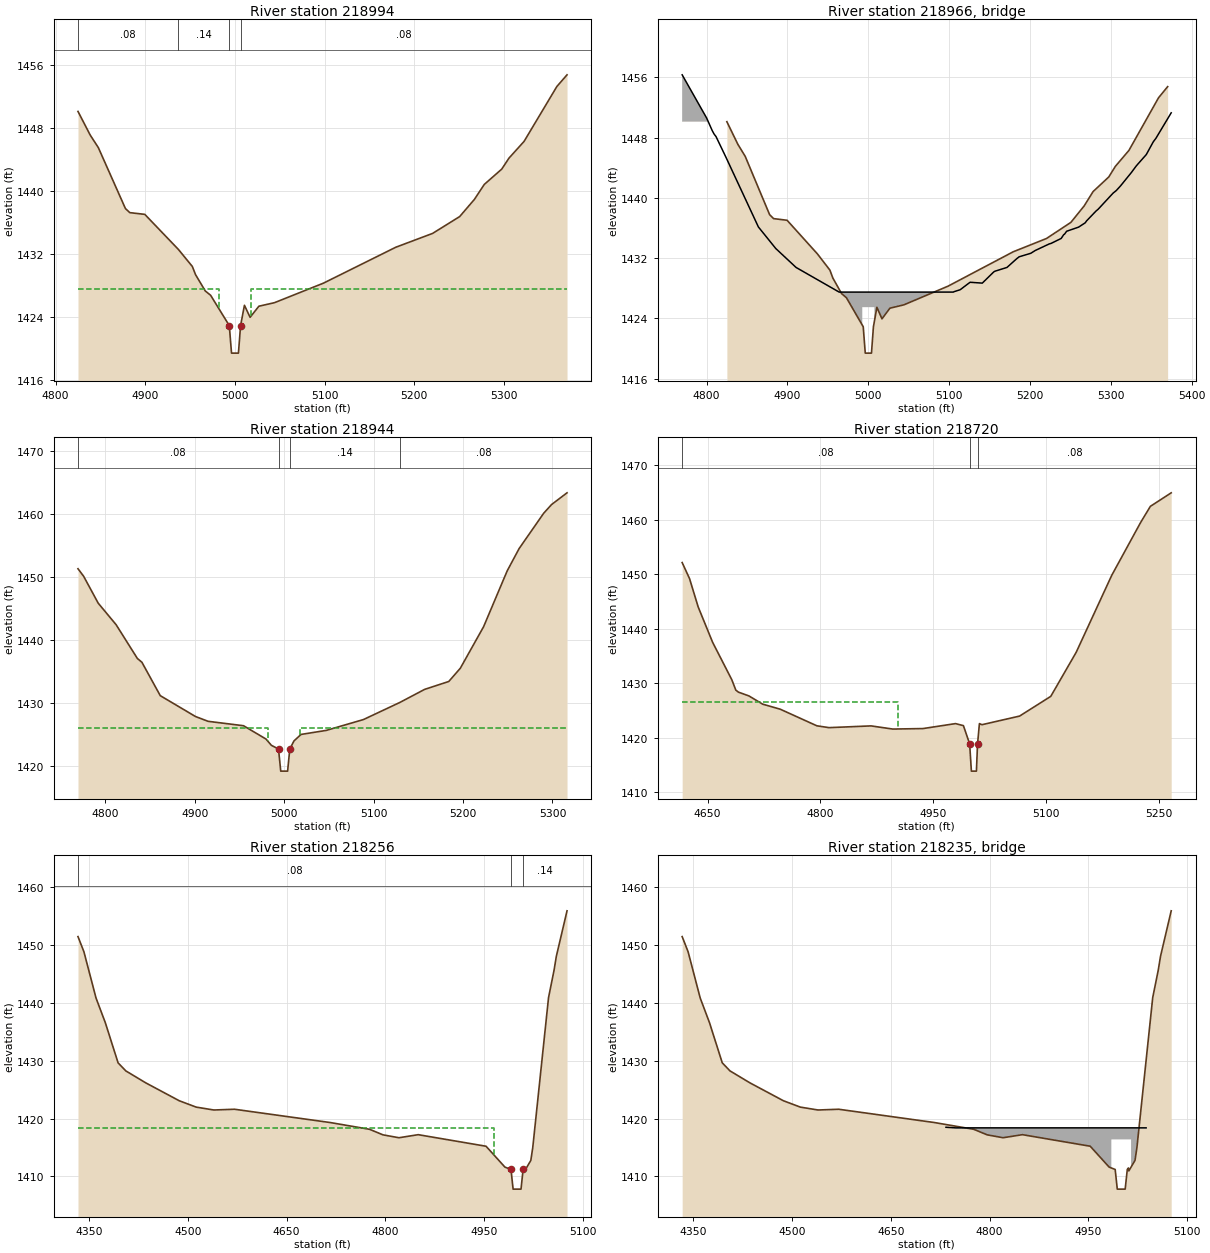
Type RM Length L Ch R = 1,218994,50,50,50
BEGIN DESCRIPTION:
Off Lumber Plant Rd (2) - US
END DESCRIPTION:
XS GIS Cut Line= 5
      1450823.54      1021716.18      1450693.67      1021677.03
      1450656.04      1021723.69      1450648.52      1021898.68
      1450543.18      1022037.88
#Sta/Elev= 30
  4825.0 1450.11  4838.6 1447.11  4847.7 1445.51  4877.9 1437.77  4882.8 1437.25
  4899.5 1437.03  4937.0 1432.57  4952.5 1430.41  4956.1 1429.37  4966.9 1427.30
  4972.9 1426.75  4993.7 1422.90  4996.2 1419.40  5003.9 1419.40  5006.3 1422.90
  5010.6 1425.48  5016.9 1423.95  5026.7 1425.36  5044.1 1425.81  5098.7 1428.29
  5179.3 1432.85  5220.4 1434.61  5250.6 1436.75  5267.0 1438.93  5278.0 1440.83
  5297.5 1442.78  5305.6 1444.18  5322.4 1446.30  5359.0 1453.28  5370.3 1454.76
#Mann=4,-1,0
  4825.0    0.08       0  4937.0    0.14       0  4993.7    0.04       0
  5006.3    0.08       0
#XS Ineff=2,0
    0.00 4982.00 1427.50 5018.00    0.00 1427.50
Permanent Ineff=
       F       F
Bank Sta=4993.7,5006.3
XS Rating Curve= 0
Exp/Cntr=0.5,0.3

Type RM Length L Ch R =3,218966,,,
BEGIN DESCRIPTION:
Off Lumber Plant Rd (2) - TOR
Structure ID: LDS_FR_25B
Approximate Survey Structure
END DESCRIPTION:
Bridge Culvert--1,0,-1,-1,0
Deck Dist Width WeirC Skew NumUp NumDn MinLoCord MaxHiCord MaxSubmerge Is_Ogee
22,12,3,,49,49,,,0.95,0,1,1,,,
  4769.7  4800.0  4806.9  4809.2  4811.6  4823.6  4864.0  4885.5  4910.6  4963.9
  4992.5  4992.5  5007.5  5007.5  5105.1  5106.2  5113.6  5125.3  5125.8  5126.2
  5141.0  5155.1  5156.6  5171.5  5183.9  5186.0  5186.5  5201.0  5206.5  5223.8
  5226.1  5238.6  5241.8  5242.7  5245.3  5260.1  5268.3  5270.1  5281.8  5284.2
  5302.7  5306.9  5312.0  5325.6  5331.6  5343.9  5352.5  5355.8  5374.7
 1456.33 1450.59 1448.92 1448.47 1448.13 1445.45 1436.14 1433.28 1430.77 1427.50
 1427.50 1427.50 1427.50 1427.50 1427.50 1427.56 1427.81 1428.76 1428.79 1428.80
 1428.69 1430.17 1430.27 1430.77 1431.96 1432.13 1432.18 1432.65 1433.02 1433.89
 1433.96 1434.62 1435.13 1435.18 1435.57 1436.12 1436.69 1436.96 1438.27 1438.48
 1440.62 1440.99 1441.59 1443.39 1444.26 1445.75 1447.44 1447.91 1451.29
 1399.40 1399.40 1399.40 1399.40 1399.40 1399.40 1399.40 1399.40 1399.40 1399.40
 1399.40 1425.50 1425.50 1399.40 1399.40 1399.40 1399.40 1399.40 1399.40 1399.40
 1399.40 1399.40 1399.40 1399.40 1399.40 1399.40 1399.40 1399.40 1399.40 1399.40
 1399.40 1399.40 1399.40 1399.40 1399.40 1399.40 1399.40 1399.40 1399.40 1399.40
 1399.40 1399.40 1399.40 1399.40 1399.40 1399.40 1399.40 1399.40 1399.40
  4769.7  4800.0  4806.9  4809.2  4811.6  4823.6  4864.0  4885.5  4910.6  4963.9
  4992.5  4992.5  5007.5  5007.5  5105.1  5106.2  5113.6  5125.3  5125.8  5126.2
  5141.0  5155.1  5156.6  5171.5  5183.9  5186.0  5186.5  5201.0  5206.5  5223.8
  5226.1  5238.6  5241.8  5242.7  5245.3  5260.1  5268.3  5270.1  5281.8  5284.2
  5302.7  5306.9  5312.0  5325.6  5331.6  5343.9  5352.5  5355.8  5374.7
 1456.33 1450.59 1448.92 1448.47 1448.13 1445.45 1436.14 1433.28 1430.77 1427.50
 1427.50 1427.50 1427.50 1427.50 1427.50 1427.56 1427.81 1428.76 1428.79 1428.80
 1428.69 1430.17 1430.27 1430.77 1431.96 1432.13 1432.18 1432.65 1433.02 1433.89
 1433.96 1434.62 1435.13 1435.18 1435.57 1436.12 1436.69 1436.96 1438.27 1438.48
 1440.62 1440.99 1441.59 1443.39 1444.26 1445.75 1447.44 1447.91 1451.29
 1399.40 1399.40 1399.40 1399.40 1399.40 1399.40 1399.40 1399.40 1399.40 1399.40
 1399.40 1425.50 1425.50 1399.40 1399.40 1399.40 1399.40 1399.40 1399.40 1399.40
 1399.40 1399.40 1399.40 1399.40 1399.40 1399.40 1399.40 1399.40 1399.40 1399.40
 1399.40 1399.40 1399.40 1399.40 1399.40 1399.40 1399.40 1399.40 1399.40 1399.40
 1399.40 1399.40 1399.40 1399.40 1399.40 1399.40 1399.40 1399.40 1399.40
Abutment Skew #Up #Dn=,2,2
  4992.5  4994.0
 1425.50 1421.19
  4992.5  4994.0
 1425.50 1420.94
Abutment Skew #Up #Dn=,2,2
  5006.0  5007.5
 1421.19 1425.50
  5006.0  5007.5
 1420.94 1425.50
BR Coef=1,1,0,1.25,0,,,0.8,0,2,0,
WSPro=,,,, 1 ,,,, 0 ,,,, 0 ,,,,-1 ,-1 ,-1 , 0 , 0 , 0 , 0 , 0
BC Design=,,0,,0,,,,,,

Type RM Length L Ch R = 1,218944,224,224,224
BEGIN DESCRIPTION:
Off Lumber Plant Rd (2) - DS
END DESCRIPTION:
XS GIS Cut Line= 4
      1450840.40      1021682.67      1450674.86      1021628.11
      1450501.76      1021829.44      1450403.91      1021872.71
#Sta/Elev= 30
  4769.5 1451.25  4775.8 1450.06  4792.1 1445.79  4812.1 1442.38  4835.9 1437.02
  4841.0 1436.41  4861.5 1431.12  4900.9 1427.81  4915.0 1427.05  4954.6 1426.35
  4979.7 1424.24  4985.7 1423.25  4993.7 1422.65  4996.2 1419.15  5003.9 1419.15
  5006.3 1422.65  5011.0 1423.94  5018.9 1424.97  5047.1 1425.61  5088.7 1427.33
  5129.5 1430.05  5157.0 1432.11  5184.1 1433.37  5197.0 1435.47  5223.0 1442.05
  5249.4 1450.91  5262.7 1454.44  5290.2 1460.05  5299.0 1461.43  5316.3 1463.29
#Mann=4,-1,0
  4769.5    0.08       0  4993.7    0.04       0  5006.3    0.14       0
  5129.5    0.08       0
#XS Ineff=2,0
    0.00 4982.00 1426.00 5018.00    0.00 1426.00
Permanent Ineff=
       F       F
Bank Sta=4993.7,5006.3
XS Rating Curve= 0
Exp/Cntr=0.5,0.3

Type RM Length L Ch R = 1,218720,464,464,464
BEGIN DESCRIPTION:
Fisher River 437.0
END DESCRIPTION:
XS GIS Cut Line= 3
      1450906.33      1021460.66      1450563.85      1021453.13
      1450304.21      1021618.70
#Sta/Elev= 30
  4616.1 1452.14  4625.9 1449.20  4637.4 1444.00  4656.6 1437.51  4682.1 1430.65
  4687.5 1428.73  4691.0 1428.36  4704.9 1427.67  4723.2 1426.16  4746.6 1425.23
  4795.2 1422.19  4811.4 1421.85  4867.3 1422.17  4896.3 1421.59  4936.4 1421.68
  4979.7 1422.59  4990.2 1422.22  4998.5 1418.87  5000.8 1413.87  5007.5 1413.87
  5009.0 1418.87  5011.5 1422.59  5014.9 1422.39  5064.9 1423.97  5106.4 1427.59
  5140.2 1435.67  5187.5 1449.80  5226.0 1459.52  5238.9 1462.46  5266.6 1464.94
#Mann=3,-1,0
  4616.1    0.08       0  4998.5    0.04       0  5009.0    0.08       0
#XS Ineff=2,0
    0.00 4903.70 1426.64               0
Permanent Ineff=
       F       F
Bank Sta=4998.5,5009
XS Rating Curve= 0
Exp/Cntr=0.5,0.3

Type RM Length L Ch R = 1,218256,54,54,54
BEGIN DESCRIPTION:
Lumber Plant Rd - US
END DESCRIPTION:
XS GIS Cut Line= 4
      1450904.43      1021452.38      1450689.91      1021444.85
      1450418.97      1021053.49      1450371.96      1021030.92
#Sta/Elev= 30
  4333.1 1451.49  4342.1 1448.87  4360.5 1440.86  4374.6 1436.60  4394.0 1429.65
  4405.7 1428.26  4435.8 1426.20  4486.9 1423.09  4512.6 1421.99  4539.5 1421.49
  4570.8 1421.62  4716.3 1419.32  4776.0 1418.15  4796.4 1417.19  4820.6 1416.69
  4849.9 1417.22  4952.9 1415.22  4981.6 1411.61  4990.8 1411.20  4994.0 1407.80
  5006.0 1407.80  5009.2 1411.20  5010.9 1411.46  5011.5 1410.95  5020.9 1412.76
  5023.8 1414.94  5047.8 1440.92  5056.2 1445.67  5059.7 1448.10  5075.9 1455.95
#Mann=3,-1,0
  4333.1    0.08       0  4990.8    0.04       0  5009.2    0.14       0
#XS Ineff=2,0
    0.00 4965.00 1418.40 5035.00    0.00 1418.40
Permanent Ineff=
       F       F
Bank Sta=4990.8,5009.2
XS Rating Curve= 0
Exp/Cntr=0.5,0.3

Type RM Length L Ch R =3,218235,,,
BEGIN DESCRIPTION:
Lumber Plant Rd - TOR
Structure ID: LDS_FR_25A
Approximate Survey Structure
END DESCRIPTION:
Bridge Culvert--1,0,-1,-1,0
Deck Dist Width WeirC Skew NumUp NumDn MinLoCord MaxHiCord MaxSubmerge Is_Ogee
11,20,3,,7,7,,,0.95,0,1,1,,,
  4733.8  4748.5  4985.0  4985.0  5015.0  5015.0  5037.8
 1418.50 1418.40 1418.40 1418.40 1418.40 1418.40 1418.40
 1387.80 1387.80 1387.80 1416.40 1416.40 1387.80 1387.80
  4733.8  4748.5  4985.0  4985.0  5015.0  5015.0  5037.8
 1418.50 1418.40 1418.40 1418.40 1418.40 1418.40 1418.40
 1387.80 1387.80 1387.80 1416.40 1416.40 1387.80 1387.80
BR Coef=1,1,0,1.25,0,,,0.8,0,2,0,
WSPro=,,,, 1 ,,,, 0 ,,,, 0 ,,,,-1 ,-1 ,-1 , 0 , 0 , 0 , 0 , 0
BC Design=,,0,,0,,,,,,

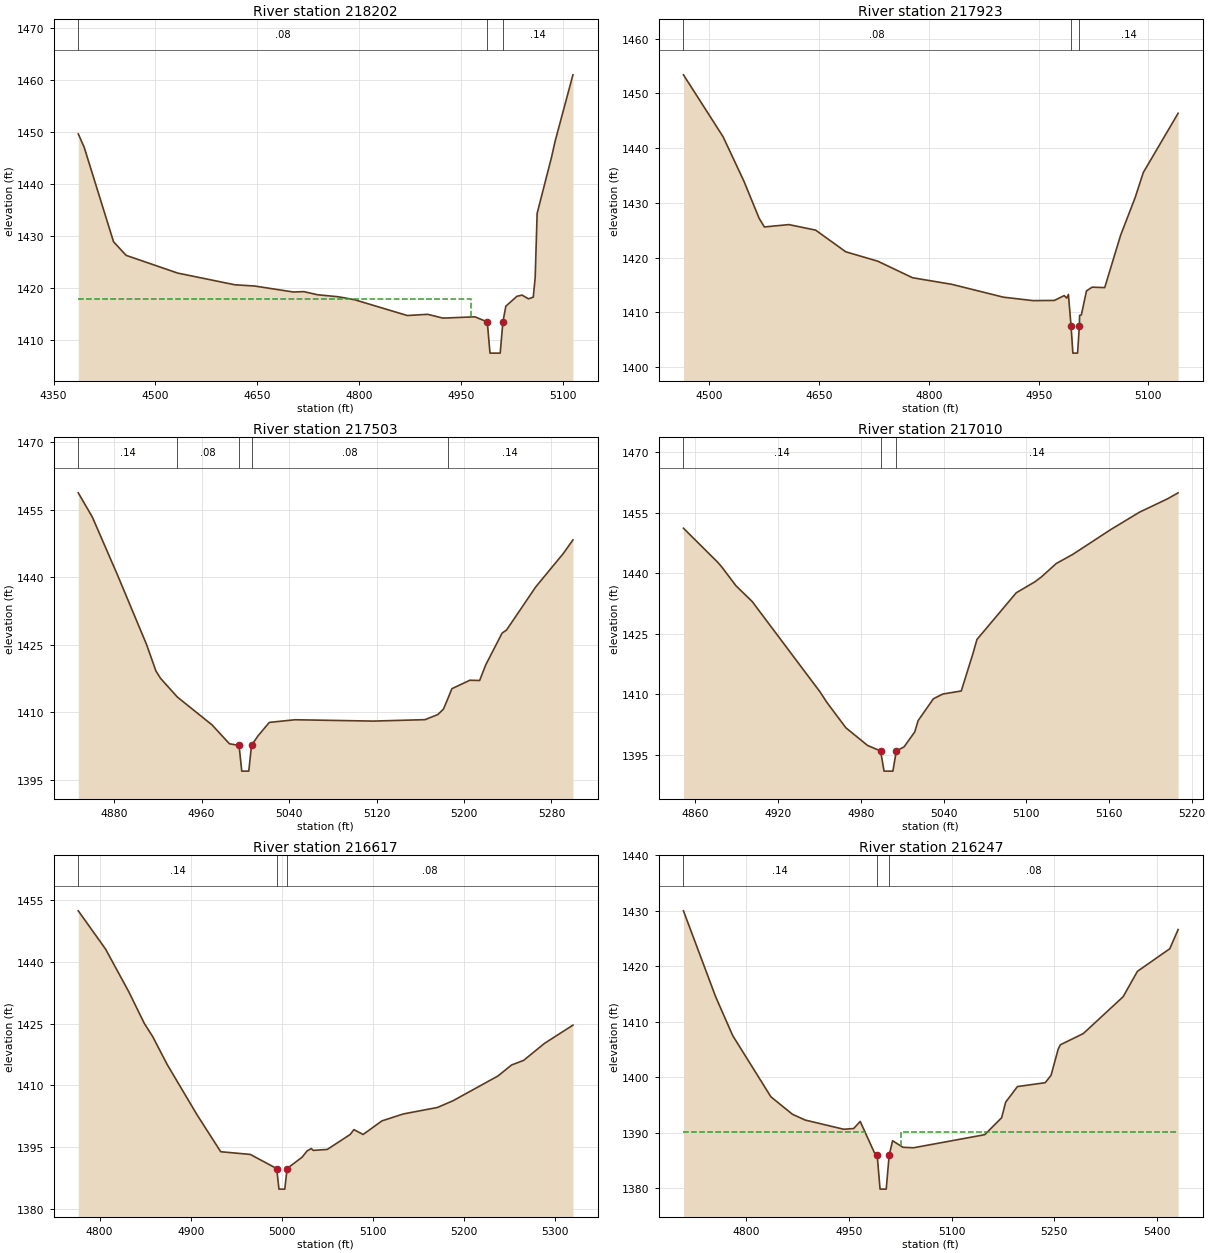
Type RM Length L Ch R = 1,218202,279,279,279
BEGIN DESCRIPTION:
Lumber Plant Rd - DS
END DESCRIPTION:
XS GIS Cut Line= 4
      1450898.78      1021412.87      1450742.20      1021404.75
      1450445.31      1021000.81      1450379.50      1020976.36
#Sta/Elev= 30
  4386.3 1449.69  4395.0 1447.13  4438.2 1428.97  4456.7 1426.35  4532.6 1422.94
  4616.7 1420.69  4646.0 1420.45  4703.0 1419.30  4718.4 1419.37  4738.7 1418.77
  4769.4 1418.38  4793.3 1417.81  4870.7 1414.78  4900.8 1415.01  4923.2 1414.28
  4970.3 1414.53  4988.5 1413.55  4992.5 1407.55  5007.5 1407.55  5011.5 1413.55
  5015.8 1416.57  5032.1 1418.47  5039.7 1418.71  5049.2 1417.98  5056.2 1418.31
  5059.0 1422.04  5061.9 1434.42  5083.2 1445.27  5088.3 1448.25  5114.6 1461.05
#Mann=3,-1,0
  4386.3    0.08       0  4988.5    0.04       0  5011.5    0.14       0
#XS Ineff=2,0
    0.00 4965.00 1418.00 5035.00    0.00 1418.00
Permanent Ineff=
       F       F
Bank Sta=4988.5,5011.5
XS Rating Curve= 0
Exp/Cntr=0.5,0.3

Type RM Length L Ch R = 1,217923,420,420,420
BEGIN DESCRIPTION:
Fisher River 436.0
END DESCRIPTION:
XS GIS Cut Line= 3
      1450967.96      1021282.22      1450690.64      1020886.90
      1450569.71      1020736.47
#Sta/Elev= 30
  4464.7 1453.41  4518.8 1442.11  4547.3 1433.99  4568.1 1427.20  4575.3 1425.62
  4608.7 1426.05  4645.3 1425.04  4686.5 1421.08  4730.3 1419.36  4777.8 1416.34
  4831.3 1415.14  4901.9 1412.79  4942.6 1412.16  4971.6 1412.20  4984.9 1413.08
  4988.4 1412.63  4990.7 1413.29  4994.3 1407.57  4996.8 1402.57  5003.2 1402.57
  5005.7 1407.57  5006.0 1409.46  5008.4 1409.55  5015.4 1413.94  5023.1 1414.62
  5040.3 1414.54  5062.0 1424.09  5082.1 1431.06  5093.0 1435.56  5140.6 1446.39
#Mann=3,-1,0
  4464.7    0.08       0  4994.3    0.04       0  5005.7    0.14       0
Bank Sta=4994.3,5005.7
XS Rating Curve= 0
Exp/Cntr=0.3,0.1

Type RM Length L Ch R = 1,217503,493,493,493
BEGIN DESCRIPTION:
Fisher River 435.0
END DESCRIPTION:
XS GIS Cut Line= 3
      1451097.80      1020624.35      1450876.50      1020544.68
      1450690.61      1020432.55
#Sta/Elev= 30
  4847.3 1458.75  4860.2 1453.35  4883.1 1440.54  4909.8 1425.03  4918.3 1419.19
  4922.5 1417.56  4937.9 1413.40  4969.6 1407.22  4985.5 1403.03  4994.3 1402.65
  4996.8 1396.95  5003.2 1396.95  5005.7 1402.65  5011.5 1404.74  5022.0 1407.77
  5045.5 1408.36  5117.0 1408.06  5164.4 1408.38  5176.1 1409.52  5181.2 1410.72
  5185.1 1412.97  5188.9 1415.25  5205.3 1417.13  5214.3 1417.08  5219.8 1420.51
  5234.8 1427.59  5238.9 1428.29  5265.6 1437.86  5290.7 1445.25  5299.6 1448.29
#Mann=5,-1,0
  4847.3    0.14       0  4937.9    0.08       0  4994.3    0.04       0
  5005.7    0.08       0  5185.1    0.14       0
#XS Ineff=2,0
       0                 5045.50    0.00 1408.36
Permanent Ineff=
       F       F
Bank Sta=4994.3,5005.7
XS Rating Curve= 0
Exp/Cntr=0.3,0.1

Type RM Length L Ch R = 1,217010,393,393,393
BEGIN DESCRIPTION:
Fisher River 434.0
END DESCRIPTION:
XS GIS Cut Line= 3
      1450982.67      1020109.54      1450900.10      1020106.59
      1450637.51      1020192.15
#Sta/Elev= 30
  4851.3 1451.12  4876.2 1442.67  4879.1 1441.52  4889.5 1436.82  4901.1 1432.98
  4950.5 1410.51  4955.3 1407.98  4969.1 1401.68  4984.9 1397.29  4994.3 1395.94
  4996.8 1390.94  5003.2 1390.94  5005.7 1395.94  5011.3 1396.94  5019.1 1400.67
  5021.5 1403.45  5032.6 1408.87  5039.4 1410.04  5052.8 1410.80  5061.2 1419.96
  5064.2 1423.56  5092.7 1435.13  5106.3 1437.86  5110.9 1439.04  5121.7 1442.38
  5133.7 1444.64  5161.1 1450.76  5182.0 1455.08  5202.5 1458.42  5210.1 1459.89
#Mann=3,-1,0
  4851.3    0.14       0  4994.3    0.04       0  5005.7    0.14       0
Bank Sta=4994.3,5005.7
XS Rating Curve= 0
Exp/Cntr=0.3,0.1

Type RM Length L Ch R = 1,216617,370,370,370
BEGIN DESCRIPTION:
Fisher River 433.0
END DESCRIPTION:
XS GIS Cut Line= 4
      1451026.99      1019873.55      1450878.60      1019770.39
      1450761.45      1019737.82      1450649.34      1019950.23
#Sta/Elev= 30
  4776.7 1452.41  4806.7 1443.09  4832.1 1432.74  4849.2 1425.02  4858.4 1421.82
  4874.2 1415.07  4906.6 1402.97  4932.9 1393.87  4965.4 1393.21  4994.3 1389.78
  4996.8 1384.78  5003.2 1384.78  5005.7 1389.78  5022.2 1392.55  5027.7 1394.07
  5032.2 1394.64  5034.5 1394.19  5049.8 1394.43  5074.9 1398.06  5079.0 1399.24
  5089.1 1398.06  5109.7 1401.36  5133.2 1403.05  5170.7 1404.63  5187.9 1406.28
  5237.0 1412.28  5251.9 1414.95  5265.1 1416.06  5288.0 1420.20  5319.2 1424.63
#Mann=3,-1,0
  4776.7    0.14       0  4994.3    0.04       0  5005.7    0.08       0
Bank Sta=4994.3,5005.7
XS Rating Curve= 0
Exp/Cntr=0.5,0.3

Type RM Length L Ch R = 1,216247,56,56,56
BEGIN DESCRIPTION:
Off Lumber Plant Rd - US
END DESCRIPTION:
XS GIS Cut Line= 4
      1451239.36      1019652.25      1451156.77      1019507.71
      1450696.55      1019330.70      1450634.62      1019318.91
#Sta/Elev= 30
  4708.3 1430.01  4755.4 1414.49  4780.3 1407.49  4836.0 1396.47  4867.4 1393.32
  4886.1 1392.27  4942.4 1390.61  4956.9 1390.74  4966.5 1392.02  4987.0 1386.45
  4991.3 1385.91  4995.5 1379.81  5004.5 1379.81  5008.8 1385.91  5013.8 1388.54
  5028.9 1387.36  5044.4 1387.27  5148.4 1389.63  5173.1 1392.69  5179.0 1395.50
  5196.2 1398.31  5236.8 1399.01  5245.3 1400.34  5255.7 1405.06  5258.9 1405.85
  5292.4 1407.87  5350.6 1414.52  5371.5 1419.10  5418.7 1423.17  5430.9 1426.63
#Mann=3,-1,0
  4708.3    0.14       0  4991.3    0.04       0  5008.8    0.08       0
#XS Ineff=2,0
    0.00 4974.00 1390.15 5026.00    0.00 1390.15
Permanent Ineff=
       F       F
Bank Sta=4991.3,5008.8
XS Rating Curve= 0
Exp/Cntr=0.5,0.3

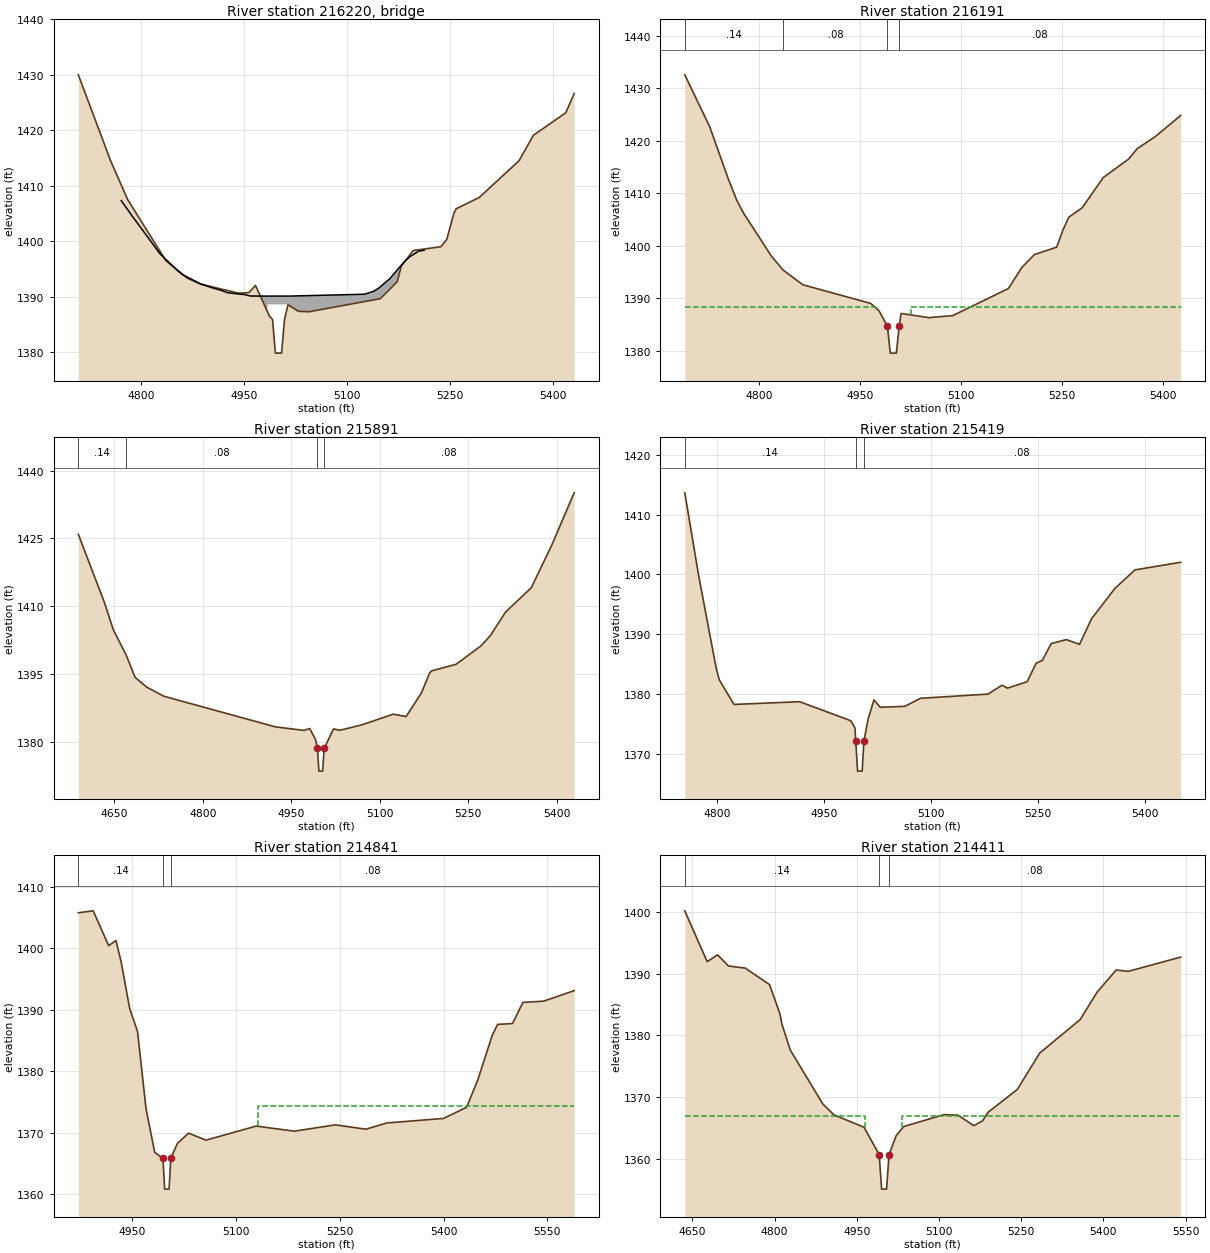
Type RM Length L Ch R =3,216220,,,
BEGIN DESCRIPTION:
Off Lumber Plant Rd - TOR
Structure ID: LDS_FR_25
Approximate Survey Structure
END DESCRIPTION:
Bridge Culvert--1,0,-1,-1,0
Deck Dist Width WeirC Skew NumUp NumDn MinLoCord MaxHiCord MaxSubmerge Is_Ogee
21.5,11,3,,29,29,,,0.95,0,1,1,,,
  4770.8  4784.3  4786.0  4793.4  4827.2  4852.9  4860.1  4885.6  4901.3  4916.6
  4925.5  4949.1  4949.6  4959.3  4984.0  4984.0  5016.0  5016.0  5124.2  5124.8
  5138.8  5146.0  5162.1  5182.0  5182.5  5191.2  5204.0  5205.0  5212.2
 1407.31 1404.98 1404.65 1403.44 1397.74 1394.71 1393.97 1392.36 1391.67 1391.13
 1390.71 1390.38 1390.40 1390.11 1390.10 1390.10 1390.10 1390.10 1390.43 1390.42
 1390.97 1391.53 1393.23 1396.11 1396.19 1397.19 1398.18 1398.23 1398.35
 1359.81 1359.81 1359.81 1359.81 1359.81 1359.81 1359.81 1359.81 1359.81 1359.81
 1359.81 1359.81 1359.81 1359.81 1359.81 1388.60 1388.60 1359.81 1359.81 1359.81
 1359.81 1359.81 1359.81 1359.81 1359.81 1359.81 1359.81 1359.81 1359.81
  4770.8  4784.3  4786.0  4793.4  4827.2  4852.9  4860.1  4885.6  4901.3  4916.6
  4925.5  4949.1  4949.6  4959.3  4984.0  4984.0  5016.0  5016.0  5124.2  5124.8
  5138.8  5146.0  5162.1  5182.0  5182.5  5191.2  5204.0  5205.0  5212.2
 1407.31 1404.98 1404.65 1403.44 1397.74 1394.71 1393.97 1392.36 1391.67 1391.13
 1390.71 1390.38 1390.40 1390.11 1390.10 1390.10 1390.10 1390.10 1390.43 1390.42
 1390.97 1391.53 1393.23 1396.11 1396.19 1397.19 1398.18 1398.23 1398.35
 1359.81 1359.81 1359.81 1359.81 1359.81 1359.81 1359.81 1359.81 1359.81 1359.81
 1359.81 1359.81 1359.81 1359.81 1359.81 1388.60 1388.60 1359.81 1359.81 1359.81
 1359.81 1359.81 1359.81 1359.81 1359.81 1359.81 1359.81 1359.81 1359.81
Abutment Skew #Up #Dn=,2,2
  4984.0  4987.5
 1388.60 1385.41
  4984.0  4987.5
 1388.60 1385.16
Abutment Skew #Up #Dn=,2,2
  5012.5  5016.0
 1385.41 1388.60
  5012.5  5016.0
 1385.16 1388.60
BR Coef=1,1,0,1.25,0,,,0.8,0,2,0,
WSPro=,,,, 1 ,,,, 0 ,,,, 0 ,,,,-1 ,-1 ,-1 , 0 , 0 , 0 , 0 , 0
BC Design=,,0,,0,,,,,,

Type RM Length L Ch R = 1,216191,300,300,300
BEGIN DESCRIPTION:
Off Lumber Plant Rd - DS
END DESCRIPTION:
XS GIS Cut Line= 3
      1451319.04      1019581.48      1451195.12      1019466.41
      1450669.98      1019251.04
#Sta/Elev= 30
  4690.2 1432.52  4727.4 1422.59  4754.7 1412.75  4767.3 1408.69  4777.5 1406.20
  4818.4 1398.11  4836.4 1395.35  4865.8 1392.56  4966.4 1389.02  4979.0 1387.58
  4991.3 1384.66  4995.5 1379.56  5004.5 1379.56  5008.8 1384.66  5011.3 1386.96
  5012.2 1387.10  5052.7 1386.31  5088.4 1386.70  5171.0 1391.85  5191.1 1395.88
  5209.6 1398.31  5242.7 1399.72  5252.3 1403.06  5260.8 1405.44  5280.5 1407.20
  5312.0 1412.98  5349.8 1416.51  5362.3 1418.46  5389.0 1420.74  5426.9 1424.78
#Mann=4,-1,0
  4690.2    0.14       0  4836.4    0.08       0  4991.3    0.04       0
  5008.8    0.08       0
#XS Ineff=2,0
    0.00 4974.00 1388.40 5026.00    0.00 1388.40
Permanent Ineff=
       F       F
Bank Sta=4991.3,5008.8
XS Rating Curve= 0
Exp/Cntr=0.5,0.3

Type RM Length L Ch R = 1,215891,472,472,472
BEGIN DESCRIPTION:
Fisher River 431.0
END DESCRIPTION:
XS GIS Cut Line= 3
      1451428.16      1019442.79      1451212.82      1019147.80
      1450758.51      1019006.19
#Sta/Elev= 30
  4588.7 1425.91  4632.6 1410.99  4648.2 1404.79  4669.8 1399.27  4685.0 1394.31
  4704.9 1392.14  4733.6 1390.15  4923.2 1383.37  4972.1 1382.59  4981.1 1383.03
  4991.2 1380.55  4994.3 1378.60  4996.8 1373.60  5003.2 1373.60  5005.7 1378.60
  5021.6 1382.93  5032.1 1382.62  5068.8 1383.79  5123.1 1386.19  5144.7 1385.65
  5170.6 1390.86  5184.6 1395.26  5187.9 1395.74  5229.5 1397.20  5271.9 1401.29
  5287.5 1403.52  5313.5 1408.75  5357.0 1414.11  5391.6 1423.46  5429.8 1435.08
#Mann=4,-1,0
  4588.7    0.14       0  4669.8    0.08       0  4994.3    0.04       0
  5005.7    0.08       0
Bank Sta=4994.3,5005.7
XS Rating Curve= 0
Exp/Cntr=0.3,0.1

Type RM Length L Ch R = 1,215419,578,578,578
BEGIN DESCRIPTION:
Fisher River 430.0
END DESCRIPTION:
XS GIS Cut Line= 4
      1451646.46      1018855.73      1451528.48      1018820.33
      1451348.52      1018681.68      1451015.18      1018596.13
#Sta/Elev= 30
  4754.8 1413.63  4774.3 1399.73  4799.1 1384.11  4803.1 1382.36  4823.7 1378.24
  4915.7 1378.70  4987.3 1375.52  4993.1 1374.34  4994.3 1372.09  4996.8 1367.09
  5003.2 1367.09  5005.7 1372.09  5011.4 1375.71  5019.7 1379.00  5028.7 1377.76
  5063.0 1377.93  5084.9 1379.27  5179.6 1379.97  5199.1 1381.46  5206.8 1380.97
  5234.3 1382.04  5246.8 1385.12  5255.6 1385.61  5268.0 1388.42  5289.4 1389.08
  5307.7 1388.29  5324.6 1392.59  5357.4 1397.66  5385.3 1400.74  5449.3 1402.02
#Mann=3,-1,0
  4754.8    0.14       0  4994.3    0.04       0  5005.7    0.08       0
#XS Ineff=2,0
    0.00 4915.70 1378.70 5019.70    0.00 1379.00
Permanent Ineff=
       F       F
Bank Sta=4994.3,5005.7
XS Rating Curve= 0
Exp/Cntr=0.3,0.1

Type RM Length L Ch R = 1,214841,430,430,430
BEGIN DESCRIPTION:
Fisher River 429.0
END DESCRIPTION:
XS GIS Cut Line= 3
      1451879.54      1018451.56      1451696.64      1018318.81
      1451227.60      1018174.26
#Sta/Elev= 30
  4872.0 1405.78  4893.5 1406.10  4915.8 1400.44  4926.4 1401.27  4933.9 1397.80
  4946.2 1390.23  4957.6 1386.48  4969.8 1373.99  4982.4 1366.85  4994.3 1365.86
  4996.8 1360.86  5003.2 1360.86  5005.7 1365.86  5015.3 1368.30  5031.3 1369.96
  5056.6 1368.82  5129.2 1371.11  5184.1 1370.28  5243.7 1371.31  5287.7 1370.60
  5318.1 1371.62  5399.9 1372.35  5433.3 1374.16  5449.3 1378.55  5470.2 1385.80
  5478.1 1387.64  5499.7 1387.78  5514.7 1391.21  5544.9 1391.42  5588.8 1393.12
#Mann=3,-1,0
  4872.0    0.14       0  4994.3    0.04       0  5005.7    0.08       0
#XS Ineff=2,0
       0                 5131.50    0.00 1374.35
Permanent Ineff=
       F       F
Bank Sta=4994.3,5005.7
XS Rating Curve= 0
Exp/Cntr=0.5,0.3

Type RM Length L Ch R = 1,214411,103,103,103
BEGIN DESCRIPTION:
North Wilson Rd - US
END DESCRIPTION:
XS GIS Cut Line= 4
      1451879.53      1018240.60      1451773.34      1018007.57
      1451469.48      1017886.61      1451230.54      1018101.96
#Sta/Elev= 30
  4636.3 1400.20  4677.1 1391.96  4696.1 1393.07  4716.1 1391.26  4746.6 1390.92
  4791.0 1388.24  4809.9 1383.50  4813.5 1381.85  4828.8 1377.64  4888.1 1368.91
  4908.5 1367.13  4963.3 1365.13  4991.0 1360.70  4995.5 1355.10  5004.5 1355.10
  5009.0 1360.70  5022.1 1363.77  5035.9 1365.24  5108.9 1367.17  5134.7 1367.09
  5163.7 1365.39  5179.7 1366.17  5190.1 1367.58  5243.0 1371.25  5284.0 1377.15
  5357.8 1382.58  5388.7 1387.02  5423.5 1390.61  5445.5 1390.39  5541.1 1392.70
#Mann=3,-1,0
  4636.3    0.14       0  4991.0    0.04       0  5009.0    0.08       0
#XS Ineff=2,0
    0.00 4966.00 1366.90 5033.00    0.00 1366.90
Permanent Ineff=
       F       F
Bank Sta=4991,5009
XS Rating Curve= 0
Exp/Cntr=0.5,0.3

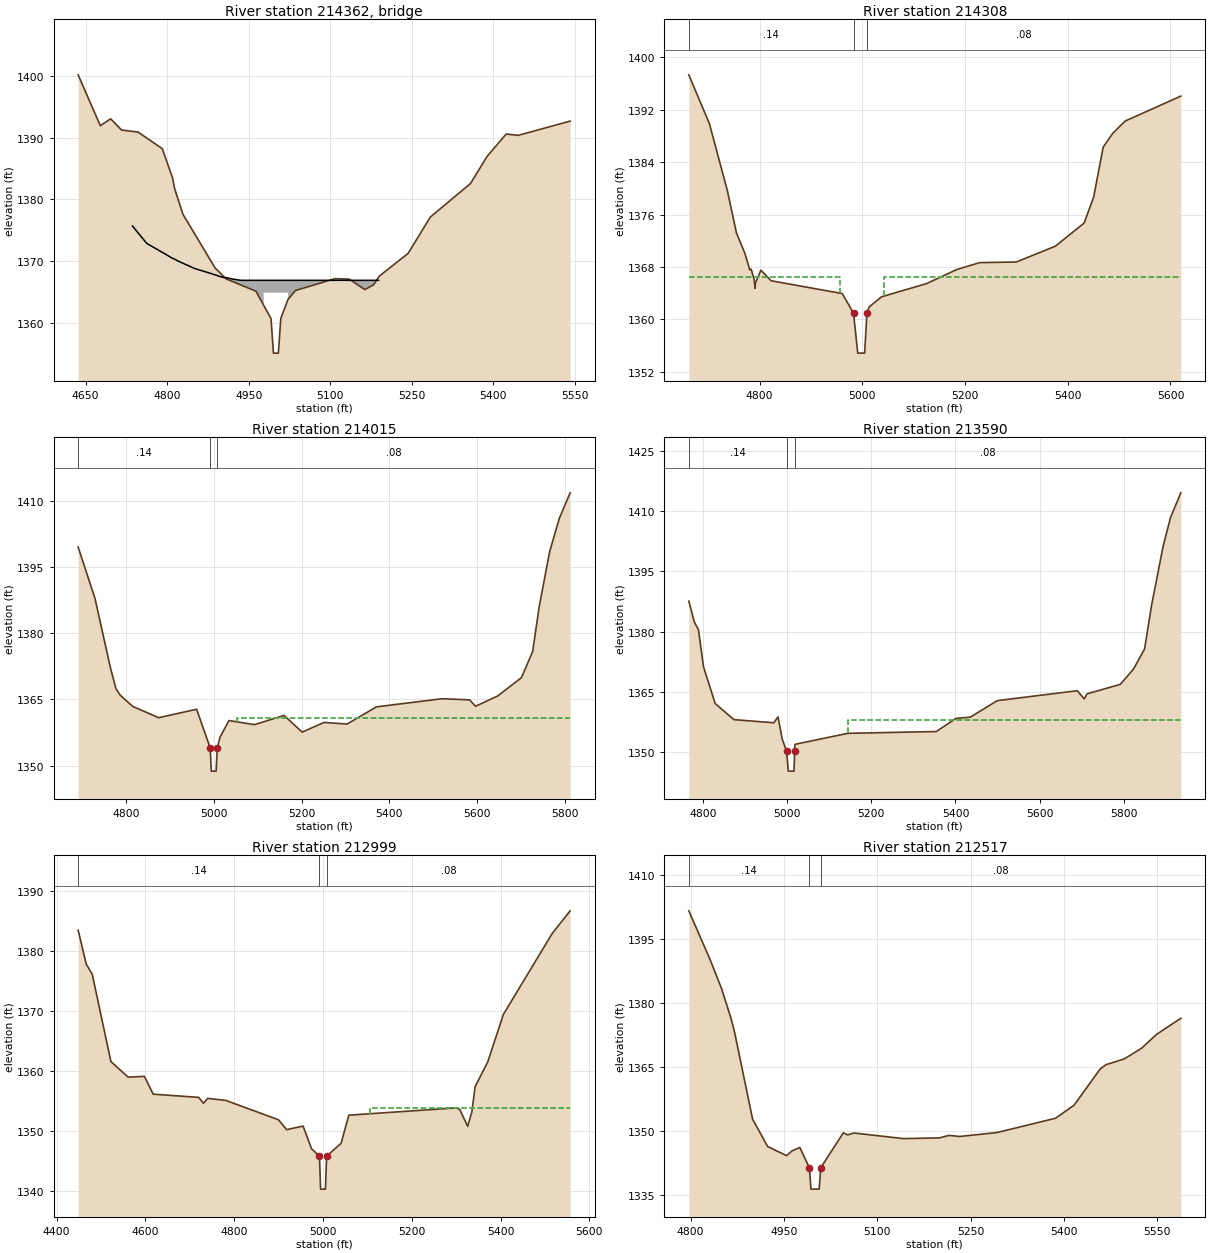
Type RM Length L Ch R =3,214362,,,
BEGIN DESCRIPTION:
North Wilson Rd - TOR
Structure ID: LDS_FR_24
Approximate Survey Structure
END DESCRIPTION:
Bridge Culvert--1,0,-1,-1,0
Deck Dist Width WeirC Skew NumUp NumDn MinLoCord MaxHiCord MaxSubmerge Is_Ogee
38.5,21,3,,19,19,,,0.95,0,1,1,,,
  4736.2  4762.5  4798.6  4808.5  4815.5  4817.9  4850.0  4879.2  4897.9  4901.5
  4910.0  4919.8  4934.3  4941.7  4977.5  4977.5  5022.5  5022.5  5188.8
 1375.70 1372.88 1371.05 1370.52 1370.26 1370.11 1368.83 1368.04 1367.50 1367.40
 1367.31 1367.12 1366.91 1366.90 1366.90 1366.90 1366.90 1366.90 1366.90
 1335.10 1335.10 1335.10 1335.10 1335.10 1335.10 1335.10 1335.10 1335.10 1335.10
 1335.10 1335.10 1335.10 1335.10 1335.10 1364.90 1364.90 1335.10 1335.10
  4736.2  4762.5  4798.6  4808.5  4815.5  4817.9  4850.0  4879.2  4897.9  4901.5
  4910.0  4919.8  4934.3  4941.7  4977.5  4977.5  5022.5  5022.5  5188.8
 1375.70 1372.88 1371.05 1370.52 1370.26 1370.11 1368.83 1368.04 1367.50 1367.40
 1367.31 1367.12 1366.91 1366.90 1366.90 1366.90 1366.90 1366.90 1366.90
 1335.10 1335.10 1335.10 1335.10 1335.10 1335.10 1335.10 1335.10 1335.10 1335.10
 1335.10 1335.10 1335.10 1335.10 1335.10 1364.90 1364.90 1335.10 1335.10
BR Coef=1,1,0,1.25,0,,,0.8,0,2,0,
WSPro=,,,, 1 ,,,, 0 ,,,, 0 ,,,,-1 ,-1 ,-1 , 0 , 0 , 0 , 0 , 0
BC Design=,,0,,0,,,,,,

Type RM Length L Ch R = 1,214308,293,293,293
BEGIN DESCRIPTION:
North Wilson Rd - DS
END DESCRIPTION:
XS GIS Cut Line= 4
      1451985.76      1017998.72      1451782.19      1017907.27
      1451454.73      1017777.46      1451168.54      1018031.20
#Sta/Elev= 30
  4662.2 1397.31  4702.4 1389.83  4737.3 1379.62  4754.9 1373.20  4771.5 1370.05
  4781.0 1367.55  4783.6 1367.66  4789.2 1366.14  4791.4 1364.73  4791.7 1365.53
  4802.6 1367.51  4822.5 1365.89  4960.9 1363.94  4982.9 1360.95  4991.1 1354.85
  5004.5 1354.85  5009.0 1360.95  5013.3 1361.90  5037.5 1363.45  5124.8 1365.45
  5183.8 1367.60  5228.6 1368.66  5299.8 1368.75  5375.9 1371.17  5431.9 1374.70
  5450.5 1378.68  5469.0 1386.29  5487.7 1388.39  5511.8 1390.26  5620.1 1394.06
#Mann=3,-1,0
  4662.2    0.14       0  4982.9    0.04       0  5009.0    0.08       0
#XS Ineff=2,0
    0.00 4956.00 1366.50 5043.00    0.00 1366.50
Permanent Ineff=
       F       F
Bank Sta=4982.9,5009
XS Rating Curve= 0
Exp/Cntr=0.5,0.3

Type RM Length L Ch R = 1,214015,425,425,425
BEGIN DESCRIPTION:
Fisher River 428.0
END DESCRIPTION:
XS GIS Cut Line= 4
      1452018.24      1017954.51      1451861.85      1017774.51
      1451855.95      1017417.54      1451425.21      1017116.62
#Sta/Elev= 30
  4691.1 1399.54  4729.4 1387.92  4764.5 1372.23  4777.2 1367.46  4786.4 1366.02
  4815.2 1363.43  4874.6 1360.86  4961.0 1362.77  4992.0 1354.00  4994.5 1348.75
  5005.5 1348.75  5008.0 1354.00  5014.3 1356.42  5034.7 1360.21  5092.8 1359.29
  5160.3 1361.37  5201.6 1357.59  5251.1 1359.78  5303.9 1359.42  5370.6 1363.31
  5520.4 1365.16  5582.8 1364.90  5596.6 1363.46  5646.8 1365.77  5701.0 1369.93
  5726.5 1375.80  5741.4 1385.94  5765.4 1398.53  5787.6 1406.09  5812.0 1411.82
#Mann=3,-1,0
  4691.1    0.14       0  4992.0    0.04       0  5008.0    0.08       0
#XS Ineff=2,0
       0                 5053.10    0.00 1360.69
Permanent Ineff=
       F       F
Bank Sta=4992,5008
XS Rating Curve= 0
Exp/Cntr=0.3,0.1

Type RM Length L Ch R = 1,213590,591,591,591
BEGIN DESCRIPTION:
Fisher River 427.0
END DESCRIPTION:
XS GIS Cut Line= 4
      1452404.67      1017733.21      1452274.87      1017585.70
      1452189.31      1017573.90      1451437.02      1017104.83
#Sta/Elev= 30
  4766.2 1387.56  4779.3 1382.38  4789.1 1380.43  4801.1 1371.25  4828.8 1362.11
  4873.4 1358.10  4968.2 1357.32  4978.3 1358.78  4988.2 1353.24  4998.6 1350.30
  5002.6 1345.30  5016.2 1345.30  5017.9 1350.30  5018.1 1351.86  5020.3 1352.00
  5144.4 1354.70  5354.5 1355.14  5401.1 1358.41  5435.1 1358.71  5499.5 1362.82
  5689.5 1365.29  5706.1 1363.25  5712.7 1364.51  5791.6 1366.86  5822.8 1370.61
  5849.4 1375.65  5866.5 1386.75  5893.5 1401.16  5911.3 1408.37  5935.6 1414.48
#Mann=3,-1,0
  4766.2    0.14       0  4998.6    0.04       0  5017.9    0.08       0
#XS Ineff=2,0
       0                 5143.80    0.00 1357.90
Permanent Ineff=
       F       F
Bank Sta=4998.6,5017.9
XS Rating Curve= 0
Exp/Cntr=0.3,0.1

Type RM Length L Ch R = 1,212999,482,482,482
BEGIN DESCRIPTION:
Fisher River 426.0
END DESCRIPTION:
XS GIS Cut Line= 4
      1452422.37      1017715.51      1452245.36      1017373.29
      1452316.17      1017137.28      1452000.51      1016780.32
#Sta/Elev= 30
  4448.4 1383.48  4466.7 1377.82  4480.2 1376.12  4522.2 1361.56  4561.2 1358.97
  4597.7 1359.10  4617.5 1356.13  4720.0 1355.60  4730.7 1354.62  4740.3 1355.43
  4781.1 1355.09  4899.4 1351.87  4918.2 1350.22  4955.1 1350.81  4974.2 1347.02
  4992.0 1345.80  4994.5 1340.30  5005.5 1340.30  5008.0 1345.80  5040.7 1347.93
  5058.1 1352.63  5299.0 1353.84  5307.8 1353.61  5325.9 1350.76  5335.3 1353.21
  5342.5 1357.37  5371.1 1361.52  5406.1 1369.41  5516.1 1382.91  5556.6 1386.70
#Mann=3,-1,0
  4448.4    0.14       0  4992.0    0.04       0  5008.0    0.08       0
#XS Ineff=2,0
       0                 5105.40    0.00 1353.79
Permanent Ineff=
       F       F
Bank Sta=4992,5008
XS Rating Curve= 0
Exp/Cntr=0.3,0.1

Type RM Length L Ch R = 1,212517,501,501,501
BEGIN DESCRIPTION:
Fisher River 425.0
END DESCRIPTION:
XS GIS Cut Line= 3
      1452746.92      1017090.11      1452513.83      1016895.37
      1452074.22      1016685.90
#Sta/Elev= 30
  4797.1 1401.66  4831.7 1390.10  4849.7 1383.44  4864.9 1376.48  4870.5 1373.31
  4899.6 1352.84  4923.8 1346.44  4954.1 1344.30  4962.9 1345.40  4975.5 1346.21
  4990.9 1341.45  4993.4 1336.45  5006.6 1336.45  5009.1 1341.45  5045.5 1349.66
  5052.4 1349.15  5062.5 1349.60  5141.8 1348.29  5199.7 1348.45  5215.2 1349.04
  5232.5 1348.79  5292.1 1349.70  5386.5 1353.06  5416.3 1356.12  5457.9 1364.55
  5467.5 1365.61  5496.8 1366.95  5524.9 1369.48  5548.9 1372.72  5587.8 1376.48
#Mann=3,-1,0
  4797.1    0.14       0  4990.9    0.04       0  5009.1    0.08       0
Bank Sta=4990.9,5009.1
XS Rating Curve= 0
Exp/Cntr=0.3,0.1