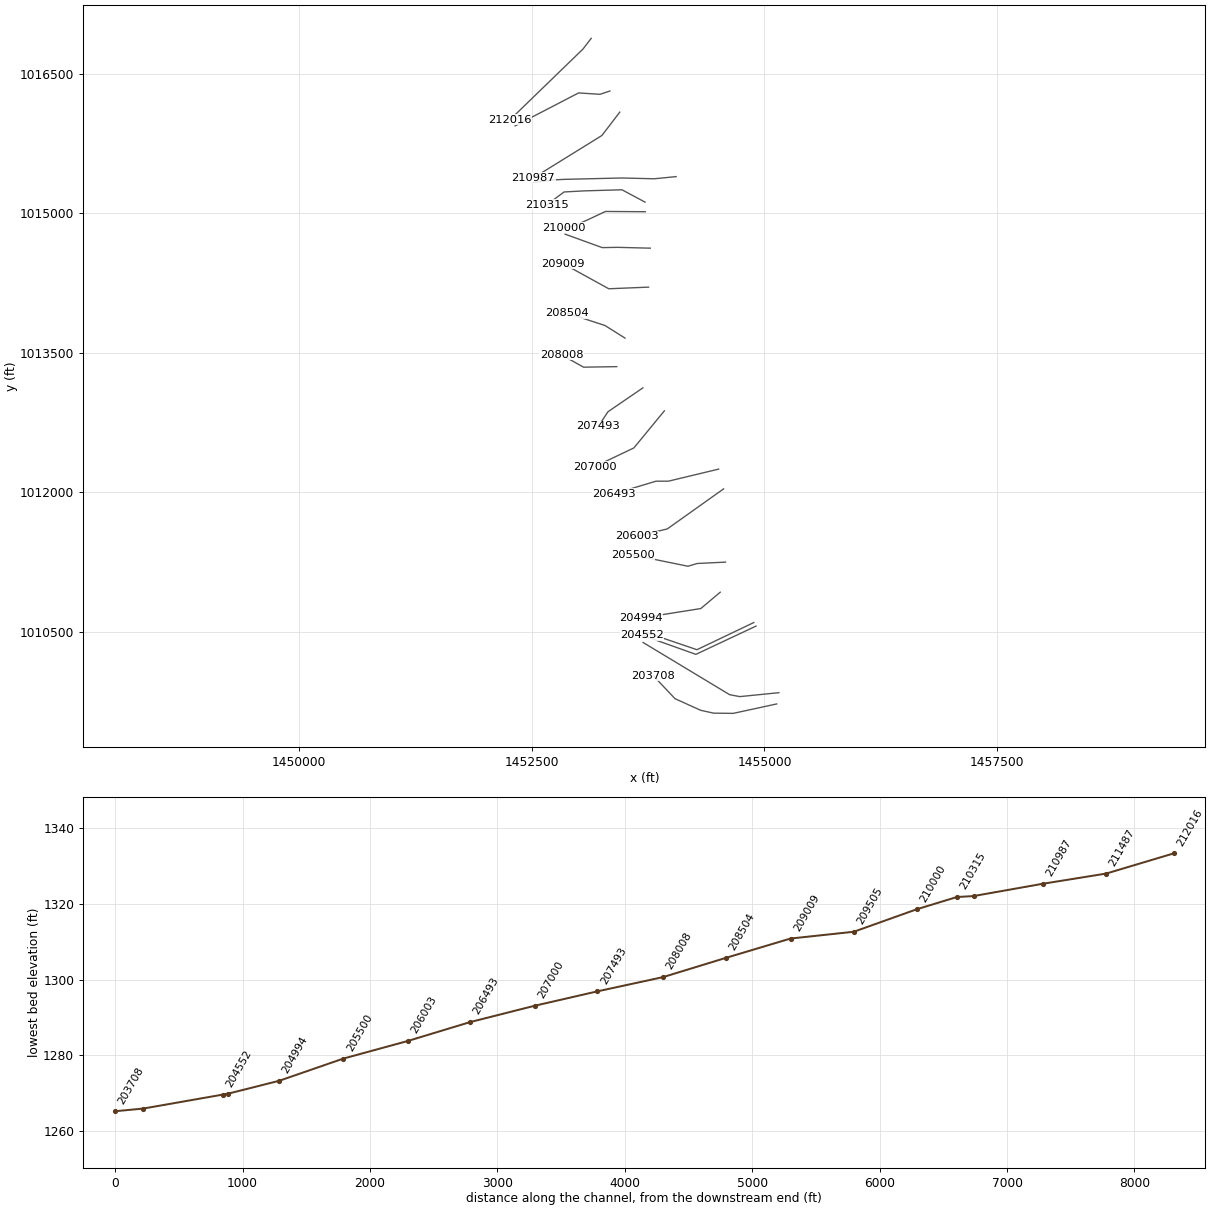
HEC-RAS study Fisher River.prj: Fisher River Limited Detail Study

--- Fisher River.g01 (geometry) --- (continued)

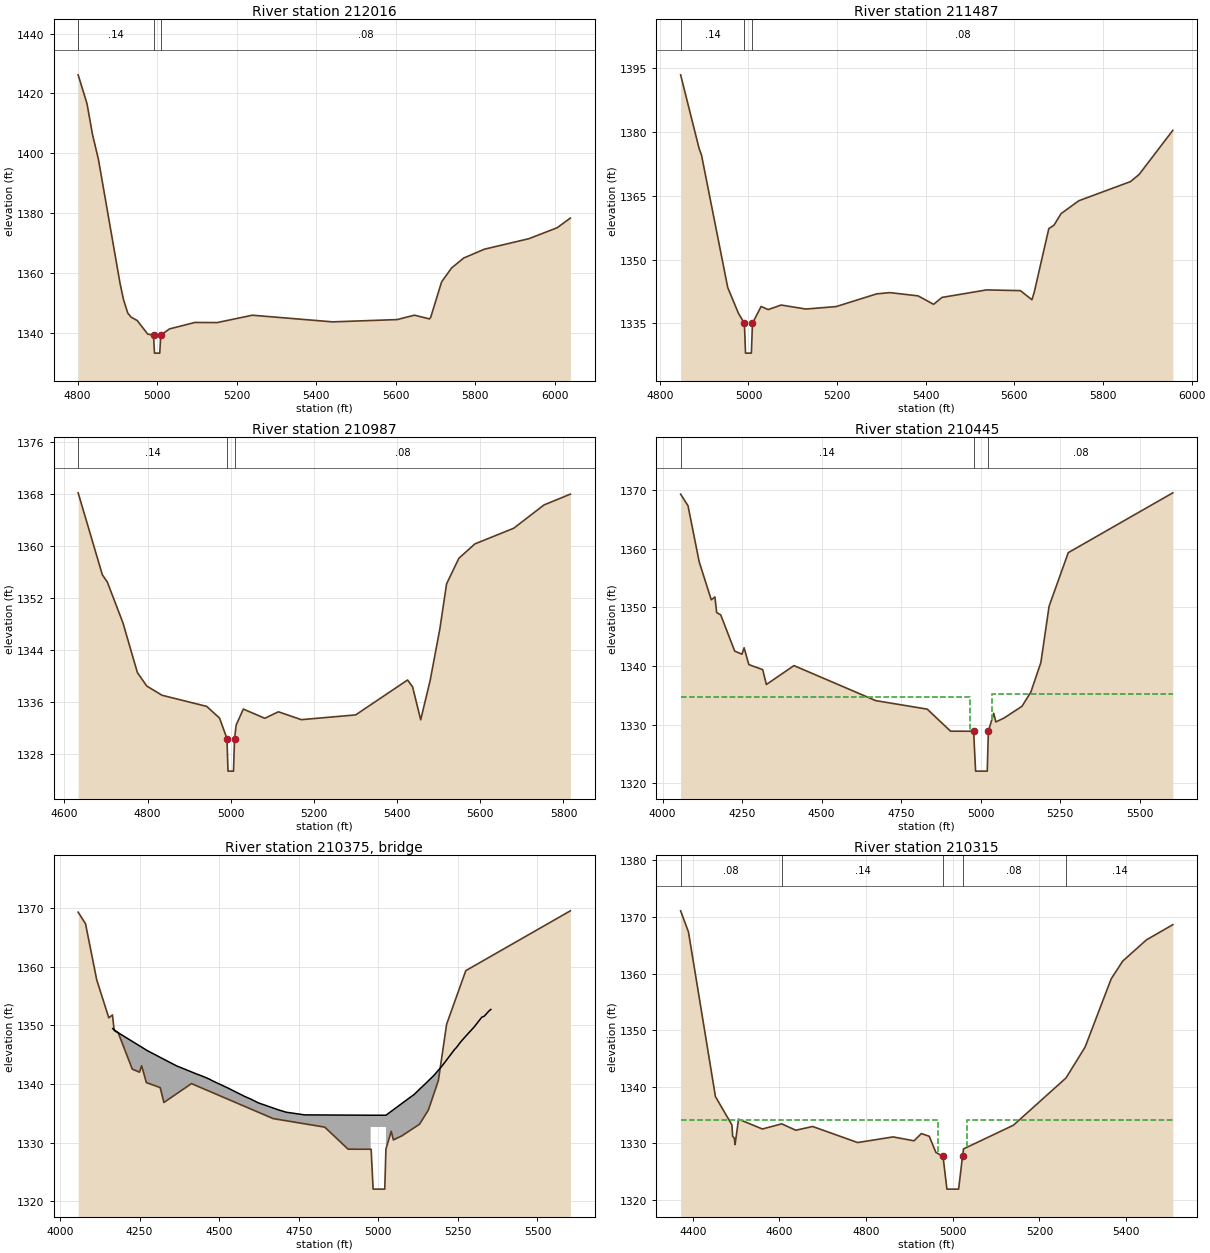
Type RM Length L Ch R = 1,212016,529,529,529
BEGIN DESCRIPTION:
Fisher River 424.0
END DESCRIPTION:
XS GIS Cut Line= 3
      1453139.23      1016880.58      1453050.75      1016765.57
      1452266.04      1016004.45
#Sta/Elev= 30
  4801.3 1426.22  4823.5 1416.65  4837.4 1406.32  4852.3 1398.03  4906.8 1356.59
  4915.4 1351.22  4926.2 1346.73  4934.5 1345.38  4949.9 1344.25  4976.4 1339.71
  4990.9 1339.37  4993.4 1333.37  5006.6 1333.37  5009.1 1339.37  5031.2 1341.45
  5095.2 1343.61  5150.9 1343.56  5239.7 1346.02  5441.4 1343.80  5603.7 1344.56
  5647.3 1346.03  5685.2 1344.79  5688.1 1345.25  5715.7 1357.14  5740.8 1361.78
  5771.3 1365.10  5823.3 1368.04  5935.3 1371.55  6006.4 1375.20  6039.6 1378.42
#Mann=3,-1,0
  4801.3    0.14       0  4990.9    0.04       0  5009.1    0.08       0
#XS Ineff=2,0
       0                 5239.70    0.00 1346.02
Permanent Ineff=
       F       F
Bank Sta=4990.9,5009.1
XS Rating Curve= 0
Exp/Cntr=0.3,0.1

Type RM Length L Ch R = 1,211487,500,500,500
BEGIN DESCRIPTION:
Fisher River 423.0
END DESCRIPTION:
XS GIS Cut Line= 4
      1453339.85      1016314.19      1453233.66      1016278.79
      1453003.55      1016293.54      1452322.03      1015939.51
#Sta/Elev= 30
  4847.0 1393.33  4888.8 1376.01  4894.1 1374.52  4953.3 1343.44  4977.5 1337.38
  4990.9 1335.05  4993.4 1328.05  5006.6 1328.05  5009.1 1335.05  5028.6 1339.00
  5044.6 1338.26  5073.8 1339.33  5129.7 1338.39  5197.9 1338.97  5289.3 1341.95
  5319.3 1342.24  5382.8 1341.48  5417.8 1339.50  5436.8 1341.12  5537.4 1342.88
  5613.6 1342.71  5639.6 1340.57  5644.8 1342.32  5677.7 1357.25  5689.4 1358.06
  5705.3 1360.77  5745.5 1363.80  5861.9 1368.28  5881.4 1369.95  5957.5 1380.31
#Mann=3,-1,0
  4847.0    0.14       0  4990.9    0.04       0  5009.1    0.08       0
Bank Sta=4990.9,5009.1
XS Rating Curve= 0
Exp/Cntr=0.3,0.1

Type RM Length L Ch R = 1,210987,542,542,542
BEGIN DESCRIPTION:
Fisher River 422.0
END DESCRIPTION:
XS GIS Cut Line= 4
      1453446.06      1016087.02      1453254.31      1015836.27
      1453167.04      1015781.71      1452516.82      1015379.03
#Sta/Elev= 30
  4633.1 1368.16  4691.3 1355.55  4703.2 1354.44  4740.9 1348.14  4775.5 1340.51
  4798.1 1338.43  4834.9 1337.01  4942.2 1335.30  4973.1 1333.50  4990.9 1330.34
  4993.4 1325.34  5006.6 1325.34  5009.1 1330.34  5013.0 1332.43  5030.3 1334.89
  5081.8 1333.47  5114.6 1334.47  5169.6 1333.26  5300.3 1333.99  5425.1 1339.36
  5437.1 1338.33  5456.7 1333.24  5479.3 1339.25  5502.7 1347.20  5518.9 1354.15
  5548.5 1358.09  5586.9 1360.30  5680.3 1362.71  5753.0 1366.29  5816.5 1367.96
#Mann=3,-1,0
  4633.1    0.14       0  4990.9    0.04       0  5009.1    0.08       0
#XS Ineff=2,0
       0                 5424.30    0.00 1339.32
Permanent Ineff=
       F       F
Bank Sta=4990.9,5009.1
XS Rating Curve= 0
Exp/Cntr=0.5,0.3

Type RM Length L Ch R = 1,210445,130,130,130
BEGIN DESCRIPTION:
Old Lowgap Rd - US
END DESCRIPTION:
XS GIS Cut Line= 6
      1454050.88      1015393.76      1453814.83      1015370.36
      1453469.67      1015379.00      1452850.14      1015364.25
      1452735.09      1015358.35      1452507.91      1015328.85
#Sta/Elev= 30
  4056.9 1369.32  4080.1 1367.35  4115.2 1357.80  4153.2 1351.31  4164.7 1351.80
  4170.2 1349.13  4182.8 1348.75  4226.9 1342.56  4249.7 1342.04  4256.4 1343.13
  4271.3 1340.26  4314.7 1339.41  4326.3 1336.87  4413.0 1340.09  4670.0 1334.12
  4831.7 1332.67  4905.1 1328.91  4977.5 1328.90  4983.7 1322.10  5020.3 1322.10
  5023.9 1328.90  5040.6 1331.96  5047.4 1330.49  5073.3 1331.16  5129.5 1333.16
  5157.3 1335.58  5188.8 1340.62  5214.7 1350.23  5274.9 1359.35  5603.4 1369.55
#Mann=3,-1,0
  4056.9    0.14       0  4977.5    0.04       0  5023.9    0.08       0
#XS Ineff=2,0
    0.00 4966.00 1334.70 5034.00    0.00 1335.17
Permanent Ineff=
       F       F
Bank Sta=4977.5,5023.9
XS Rating Curve= 0
Exp/Cntr=0.5,0.3

Type RM Length L Ch R =3,210375,,,
BEGIN DESCRIPTION:
Old Lowgap Rd - TOR
Structure ID: LDS_FR_23
Approximate Survey Structure
END DESCRIPTION:
Bridge Culvert--1,0,-1,-1,0
Deck Dist Width WeirC Skew NumUp NumDn MinLoCord MaxHiCord MaxSubmerge Is_Ogee
55,30,3,,37,37,,,0.95,0,1,1,,,
  4165.6  4180.3  4274.7  4365.2  4430.4  4449.6  4471.6  4474.3  4528.2  4579.4
  4590.3  4600.0  4622.5  4682.3  4682.8  4710.2  4768.2  4976.0  4976.0  5024.0
  5024.0  5098.5  5112.7  5133.8  5139.8  5174.1  5200.5  5239.8  5245.4  5257.7
  5266.3  5302.1  5325.2  5331.9  5334.0  5346.8  5353.5
 1349.46 1348.85 1345.70 1343.14 1341.70 1341.31 1340.80 1340.69 1339.32 1337.92
 1337.67 1337.44 1336.82 1335.69 1335.67 1335.22 1334.76 1334.70 1334.70 1334.70
 1334.70 1337.69 1338.24 1339.36 1339.65 1341.46 1343.11 1345.93 1346.23 1347.12
 1347.67 1349.81 1351.42 1351.56 1351.65 1352.43 1352.73
 1302.10 1302.10 1302.10 1302.10 1302.10 1302.10 1302.10 1302.10 1302.10 1302.10
 1302.10 1302.10 1302.10 1302.10 1302.10 1302.10 1302.10 1302.10 1332.70 1332.70
 1302.10 1302.10 1302.10 1302.10 1302.10 1302.10 1302.10 1302.10 1302.10 1302.10
 1302.10 1302.10 1302.10 1302.10 1302.10 1302.10 1302.10
  4165.6  4180.3  4274.7  4365.2  4430.4  4449.6  4471.6  4474.3  4528.2  4579.4
  4590.3  4600.0  4622.5  4682.3  4682.8  4710.2  4768.2  4976.0  4976.0  5024.0
  5024.0  5098.5  5112.7  5133.8  5139.8  5174.1  5200.5  5239.8  5245.4  5257.7
  5266.3  5302.1  5325.2  5331.9  5334.0  5346.8  5353.5
 1349.46 1348.85 1345.70 1343.14 1341.70 1341.31 1340.80 1340.69 1339.32 1337.92
 1337.67 1337.44 1336.82 1335.69 1335.67 1335.22 1334.76 1334.70 1334.70 1334.70
 1334.70 1337.69 1338.24 1339.36 1339.65 1341.46 1343.11 1345.93 1346.23 1347.12
 1347.67 1349.81 1351.42 1351.56 1351.65 1352.43 1352.73
 1302.10 1302.10 1302.10 1302.10 1302.10 1302.10 1302.10 1302.10 1302.10 1302.10
 1302.10 1302.10 1302.10 1302.10 1302.10 1302.10 1302.10 1302.10 1332.70 1332.70
 1302.10 1302.10 1302.10 1302.10 1302.10 1302.10 1302.10 1302.10 1302.10 1302.10
 1302.10 1302.10 1302.10 1302.10 1302.10 1302.10 1302.10
BR Coef=1,1,0,1.25,0,,,0.8,0,2,0,
WSPro=,,,, 1 ,,,, 0 ,,,, 0 ,,,,-1 ,-1 ,-1 , 0 , 0 , 0 , 0 , 0
BC Design=,,0,,0,,,,,,

Type RM Length L Ch R = 1,210315,315,315,315
BEGIN DESCRIPTION:
Old Lowgap Rd - DS
END DESCRIPTION:
XS GIS Cut Line= 5
      1453717.45      1015119.41      1453469.67      1015252.15
      1453062.55      1015240.35      1452847.19      1015228.55
      1452661.30      1015089.86
#Sta/Elev= 30
  4371.9 1371.09  4390.0 1367.36  4452.3 1338.22  4490.3 1333.21  4492.0 1331.21
  4495.8 1330.88  4497.5 1329.72  4505.6 1334.23  4560.6 1332.49  4605.3 1333.40
  4637.7 1332.27  4676.7 1332.93  4780.5 1330.09  4862.3 1331.09  4910.6 1330.40
  4927.5 1331.68  4945.8 1331.20  4961.1 1328.34  4977.5 1327.65  4986.5 1321.85
  5013.5 1321.85  5022.5 1327.65  5024.9 1328.97  5140.1 1333.16  5261.5 1341.53
  5305.5 1346.99  5365.6 1359.05  5392.2 1362.19  5447.0 1365.95  5507.9 1368.64
#Mann=5,-1,0
  4371.9    0.08       0  4605.3    0.14       0  4977.5    0.04       0
  5022.5    0.08       0  5261.5    0.14       0
#XS Ineff=2,0
    0.00 4966.00 1334.00 5034.00    0.00 1334.00
Permanent Ineff=
       F       F
Bank Sta=4977.5,5022.5
XS Rating Curve= 0
Exp/Cntr=0.5,0.3

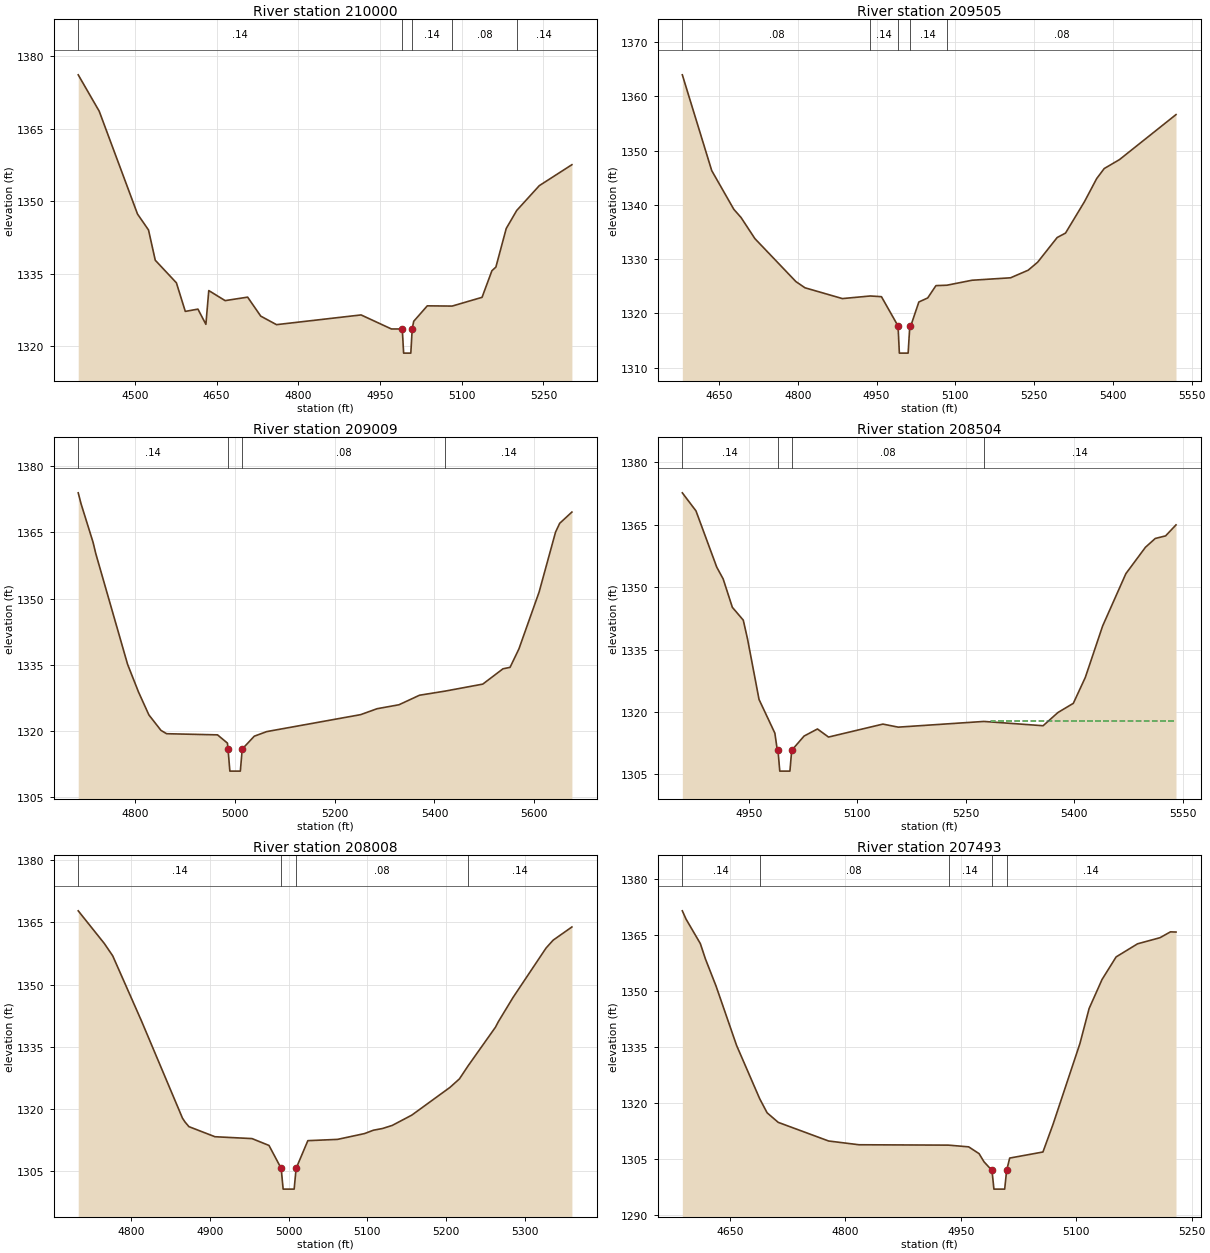
Type RM Length L Ch R = 1,210000,495,495,495
BEGIN DESCRIPTION:
Fisher River 420.0
END DESCRIPTION:
XS GIS Cut Line= 5
      1453720.42      1015016.14      1453292.66      1015019.09
      1453101.53      1014929.22      1452954.93      1014863.65
      1452850.14      1014845.03
#Sta/Elev= 30
  4396.2 1376.18  4434.7 1368.66  4505.0 1347.39  4525.2 1344.09  4537.6 1337.83
  4576.4 1333.16  4592.7 1327.25  4615.9 1327.72  4630.5 1324.58  4635.8 1331.56
  4665.8 1329.48  4707.1 1330.20  4731.2 1326.27  4760.1 1324.51  4915.3 1326.52
  4970.9 1323.62  4990.9 1323.62  4993.4 1318.62  5006.6 1318.62  5009.1 1323.62
  5011.9 1325.20  5036.8 1328.40  5082.4 1328.35  5137.3 1330.16  5155.4 1335.66
  5162.7 1336.42  5181.7 1344.40  5200.9 1348.12  5242.3 1353.25  5302.2 1357.59
#Mann=5,-1,0
  4396.2    0.14       0  4990.9    0.04       0  5009.1    0.14       0
  5082.4    0.08       0  5200.9    0.14       0
#XS Ineff=2,0
    0.00 4707.10 1330.10               0
Permanent Ineff=
       F       F
Bank Sta=4990.9,5009.1
XS Rating Curve= 0
Exp/Cntr=0.3,0.1

Type RM Length L Ch R = 1,209505,496,496,496
BEGIN DESCRIPTION:
Fisher River 419.0
END DESCRIPTION:
XS GIS Cut Line= 4
      1453773.55      1014624.36      1453422.47      1014633.21
      1453257.26      1014630.26      1452859.01      1014774.81
#Sta/Elev= 30
  4580.1 1363.95  4636.1 1346.30  4678.1 1339.18  4691.9 1337.66  4718.3 1333.77
  4796.4 1325.85  4813.7 1324.71  4884.9 1322.72  4938.1 1323.20  4959.3 1323.07
  4990.9 1317.67  4993.4 1312.67  5010.1 1312.67  5013.3 1317.67  5015.1 1317.67
  5030.5 1322.09  5047.4 1322.84  5063.1 1325.11  5083.8 1325.18  5131.8 1326.10
  5205.2 1326.55  5238.7 1327.95  5256.7 1329.42  5293.9 1333.97  5309.8 1334.79
  5345.8 1340.56  5369.2 1344.84  5383.5 1346.68  5412.6 1348.33  5520.2 1356.62
#Mann=5,-1,0
  4580.1    0.08       0  4938.1    0.14       0  4990.9    0.04       0
  5013.3    0.14       0  5083.8    0.08       0
Bank Sta=4990.9,5013.3
XS Rating Curve= 0
Exp/Cntr=0.3,0.1

Type RM Length L Ch R = 1,209009,505,505,505
BEGIN DESCRIPTION:
Fisher River 418.0
END DESCRIPTION:
XS GIS Cut Line= 3
      1453755.82      1014205.44      1453328.06      1014187.74
      1452835.40      1014459.15
#Sta/Elev= 30
  4685.2 1373.95  4690.8 1371.50  4715.0 1362.73  4720.4 1360.19  4784.3 1335.07
  4806.1 1328.83  4827.0 1323.62  4851.2 1320.12  4862.5 1319.36  4964.7 1319.10
  4984.6 1317.23  4985.8 1315.88  4989.5 1310.88  5010.5 1310.88  5014.3 1315.88
  5038.5 1318.80  5063.5 1319.84  5251.9 1323.68  5284.8 1325.02  5328.8 1325.92
  5370.0 1328.08  5421.7 1329.02  5497.0 1330.60  5537.5 1334.07  5551.7 1334.40
  5569.5 1338.58  5610.0 1351.46  5643.0 1365.05  5651.3 1367.04  5675.8 1369.59
#Mann=4,-1,0
  4685.2    0.14       0  4985.8    0.04       0  5014.3    0.08       0
  5421.7    0.14       0
Bank Sta=4985.8,5014.3
XS Rating Curve= 0
Exp/Cntr=0.3,0.1

Type RM Length L Ch R = 1,208504,496,496,496
BEGIN DESCRIPTION:
Fisher River 417.0
END DESCRIPTION:
XS GIS Cut Line= 3
      1453502.12      1013657.31      1453286.76      1013793.01
      1452879.61      1013925.78
#Sta/Elev= 30
  4858.2 1372.62  4877.1 1368.28  4905.8 1354.78  4914.7 1351.94  4927.4 1345.13
  4942.5 1342.05  4948.4 1337.52  4964.3 1323.01  4986.2 1314.92  4989.6 1310.80
  4990.5 1310.80  4993.0 1305.80  5007.0 1305.80  5009.5 1310.80  5026.6 1314.22
  5045.1 1315.92  5060.4 1313.98  5135.6 1317.09  5156.9 1316.36  5275.3 1317.73
  5357.2 1316.70  5377.7 1319.87  5399.0 1322.08  5415.6 1328.31  5439.5 1340.64
  5471.7 1353.22  5498.7 1359.54  5512.3 1361.66  5526.6 1362.28  5541.0 1364.92
#Mann=4,-1,0
  4858.2    0.14       0  4990.5    0.04       0  5009.5    0.08       0
  5275.3    0.14       0
#XS Ineff=2,0
       0                 5285.00    0.00 1317.89
Permanent Ineff=
       F       F
Bank Sta=4990.5,5009.5
XS Rating Curve= 0
Exp/Cntr=0.3,0.1

Type RM Length L Ch R = 1,208008,515,515,515
BEGIN DESCRIPTION:
Fisher River 416.0
END DESCRIPTION:
XS GIS Cut Line= 3
      1453413.64      1013350.49      1453056.65      1013344.59
      1452820.66      1013477.34
#Sta/Elev= 30
  4732.4 1367.77  4765.7 1359.87  4776.3 1356.91  4812.8 1341.25  4865.0 1317.79
  4868.2 1316.87  4873.2 1315.75  4906.3 1313.32  4953.4 1312.87  4975.0 1311.22
  4990.5 1305.69  4993.0 1300.69  5007.0 1300.69  5009.5 1305.69  5024.4 1312.37
  5062.2 1312.68  5096.5 1314.08  5107.8 1314.89  5119.3 1315.30  5131.8 1316.05
  5156.7 1318.54  5205.2 1325.22  5217.2 1327.27  5228.0 1330.35  5263.0 1339.72
  5266.7 1341.06  5285.4 1346.90  5327.3 1358.79  5336.3 1360.69  5360.2 1363.88
#Mann=4,-1,0
  4732.4    0.14       0  4990.5    0.04       0  5009.5    0.08       0
  5228.0    0.14       0
Bank Sta=4990.5,5009.5
XS Rating Curve= 0
Exp/Cntr=0.3,0.1

Type RM Length L Ch R = 1,207493,493,493,493
BEGIN DESCRIPTION:
Fisher River 415.0
END DESCRIPTION:
XS GIS Cut Line= 4
      1453693.85      1013121.84      1453413.62      1012930.10
      1453319.21      1012865.20      1453215.95      1012708.83
#Sta/Elev= 30
  4588.1 1371.58  4593.0 1369.33  4611.5 1362.80  4618.1 1358.69  4632.0 1351.36
  4658.6 1335.48  4688.7 1321.15  4698.3 1317.40  4712.7 1314.84  4778.2 1309.84
  4817.7 1308.83  4934.0 1308.73  4960.2 1308.27  4973.7 1306.45  4980.1 1304.27
  4990.5 1301.93  4993.0 1296.93  5007.0 1296.93  5009.5 1301.93  5013.5 1305.26
  5056.7 1306.89  5069.8 1314.30  5104.8 1336.01  5116.7 1345.38  5133.5 1353.16
  5151.8 1359.22  5179.6 1362.73  5208.8 1364.37  5222.4 1365.94  5229.6 1365.89
#Mann=5,-1,0
  4588.1    0.14       0  4688.7    0.08       0  4934.0    0.14       0
  4990.5    0.04       0  5009.5    0.14       0
Bank Sta=4990.5,5009.5
XS Rating Curve= 0
Exp/Cntr=0.3,0.1

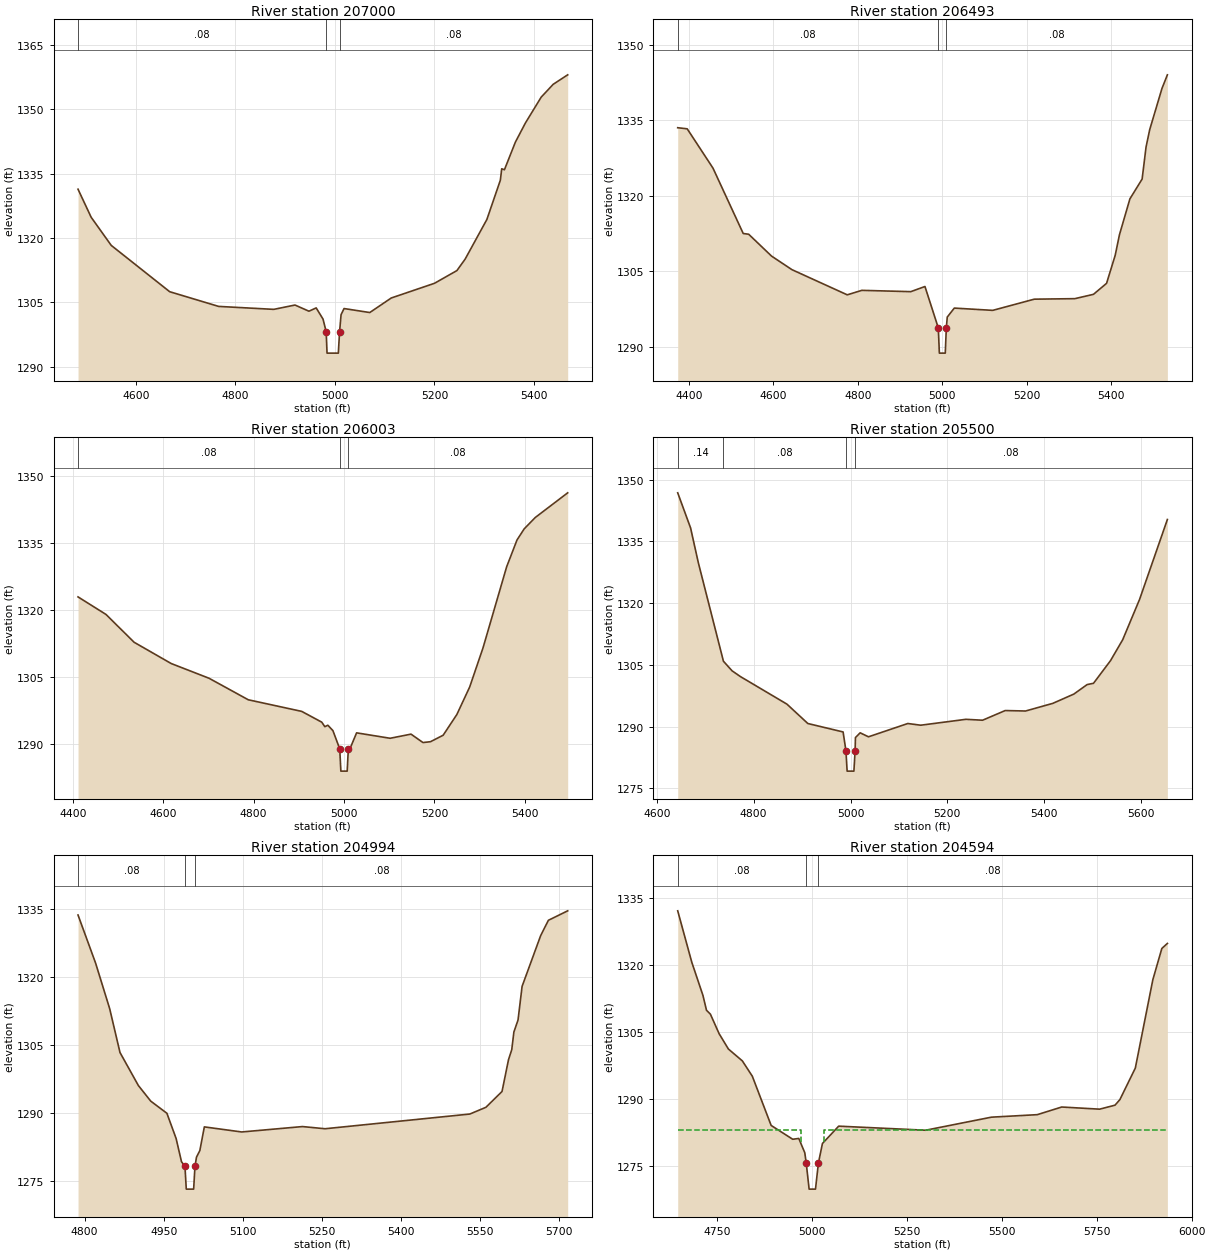
Type RM Length L Ch R = 1,207000,507,507,507
BEGIN DESCRIPTION:
Fisher River 414.0
END DESCRIPTION:
XS GIS Cut Line= 3
      1453925.00      1012875.00      1453597.36      1012476.24
      1453174.96      1012274.98
#Sta/Elev= 30
  4483.9 1331.37  4510.3 1324.82  4550.7 1318.25  4668.1 1307.45  4766.4 1304.02
  4877.3 1303.33  4919.9 1304.34  4948.0 1302.90  4962.5 1303.67  4976.2 1301.07
  4982.6 1298.12  4984.3 1293.12  5007.0 1293.12  5009.5 1298.12  5012.5 1302.09
  5018.5 1303.52  5070.2 1302.59  5113.3 1305.98  5200.2 1309.41  5245.3 1312.38
  5261.8 1315.05  5305.5 1324.30  5332.6 1333.47  5335.3 1336.13  5340.8 1335.91
  5362.8 1342.35  5382.9 1346.81  5414.7 1352.85  5438.8 1355.84  5467.9 1358.05
#Mann=3,-1,0
  4483.9    0.08       0  4982.6    0.04       0  5009.5    0.08       0
Bank Sta=4982.6,5009.5
XS Rating Curve= 0
Exp/Cntr=0.3,0.1

Type RM Length L Ch R = 1,206493,490,490,490
BEGIN DESCRIPTION:
Fisher River 413.0
END DESCRIPTION:
XS GIS Cut Line= 4
      1454508.13      1012248.62      1453968.24      1012118.81
      1453835.48      1012118.81      1453384.07      1011983.10
#Sta/Elev= 30
  4373.5 1333.50  4396.0 1333.28  4457.0 1325.49  4528.6 1312.52  4541.5 1312.38
  4595.7 1308.04  4644.0 1305.35  4774.9 1300.36  4809.5 1301.25  4925.3 1300.99
  4958.9 1302.01  4990.5 1293.80  4993.0 1288.80  5007.0 1288.80  5009.5 1293.80
  5011.7 1295.95  5028.4 1297.73  5119.4 1297.28  5217.8 1299.50  5313.7 1299.60
  5357.9 1300.46  5388.9 1302.64  5409.4 1308.22  5419.4 1312.27  5444.2 1319.40
  5473.1 1323.32  5482.4 1329.68  5491.1 1333.14  5520.1 1341.29  5532.9 1343.99
#Mann=3,-1,0
  4373.5    0.08       0  4990.5    0.04       0  5009.5    0.08       0
Bank Sta=4990.5,5009.5
XS Rating Curve= 0
Exp/Cntr=0.3,0.1

Type RM Length L Ch R = 1,206003,503,503,503
BEGIN DESCRIPTION:
Fisher River 412.0
END DESCRIPTION:
XS GIS Cut Line= 3
      1454561.20      1012036.20      1453956.44      1011605.49
      1453625.04      1011525.01
#Sta/Elev= 30
  4411.4 1322.94  4473.3 1319.00  4535.5 1312.75  4617.6 1307.97  4701.2 1304.67
  4788.1 1299.83  4906.4 1297.22  4950.7 1294.80  4957.5 1293.79  4964.2 1294.11
  4975.4 1292.90  4990.5 1288.80  4993.0 1283.80  5007.0 1283.80  5009.5 1288.80
  5013.1 1288.83  5027.8 1292.40  5102.0 1291.18  5148.2 1292.11  5174.7 1290.22
  5191.3 1290.41  5219.3 1291.86  5249.6 1296.51  5278.0 1302.69  5307.6 1311.51
  5359.8 1329.69  5382.7 1335.72  5398.7 1338.23  5423.2 1340.78  5494.9 1346.32
#Mann=3,-1,0
  4411.4    0.08       0  4990.5    0.04       0  5009.5    0.08       0
Bank Sta=4990.5,5009.5
XS Rating Curve= 0
Exp/Cntr=0.3,0.1

Type RM Length L Ch R = 1,205500,506,506,506
BEGIN DESCRIPTION:
Fisher River 411.0
END DESCRIPTION:
XS GIS Cut Line= 4
      1454581.88      1011248.53      1454278.00      1011233.78
      1454177.70      1011204.27      1453587.66      1011325.23
#Sta/Elev= 30
  4643.2 1346.81  4669.8 1338.27  4685.8 1329.81  4737.6 1305.89  4755.4 1303.56
  4772.6 1302.16  4868.7 1295.46  4911.9 1290.75  4984.7 1288.70  4990.5 1284.18
  4993.0 1279.18  5007.0 1279.18  5009.5 1284.18  5010.2 1287.33  5019.9 1288.49
  5037.1 1287.52  5118.3 1290.75  5145.0 1290.34  5238.4 1291.77  5272.7 1291.55
  5319.4 1293.90  5361.5 1293.79  5417.8 1295.65  5461.1 1297.90  5488.7 1300.22
  5501.7 1300.52  5536.9 1306.03  5562.1 1311.13  5596.9 1320.92  5654.3 1340.33
#Mann=4,-1,0
  4643.2    0.14       0  4737.6    0.08       0  4990.5    0.04       0
  5009.5    0.08       0
Bank Sta=4990.5,5009.5
XS Rating Curve= 0
Exp/Cntr=0.3,0.1

Type RM Length L Ch R = 1,204994,400,400,400
BEGIN DESCRIPTION:
Fisher River 410.0
END DESCRIPTION:
XS GIS Cut Line= 3
      1454525.03      1010925.02      1454316.36      1010749.36
      1453667.28      1010646.10
#Sta/Elev= 30
  4787.4 1333.72  4820.8 1323.11  4847.5 1313.08  4867.1 1303.41  4902.0 1296.13
  4925.6 1292.68  4956.2 1290.01  4973.7 1284.45  4983.9 1279.34  4990.5 1278.29
  4993.0 1273.29  5007.0 1273.29  5009.5 1278.29  5012.4 1280.34  5018.8 1281.80
  5027.3 1287.01  5098.3 1285.89  5213.7 1287.08  5256.6 1286.60  5531.5 1289.84
  5562.1 1291.33  5592.7 1294.82  5605.0 1301.83  5611.2 1304.05  5615.2 1307.92
  5623.1 1310.58  5630.8 1317.99  5666.0 1329.15  5680.7 1332.55  5717.4 1334.64
#Mann=3,-1,0
  4787.4    0.08       0  4990.5    0.04       0  5009.5    0.08       0
Bank Sta=4990.5,5009.5
XS Rating Curve= 0
Exp/Cntr=0.5,0.3

Type RM Length L Ch R = 1,204594,42,42,42
BEGIN DESCRIPTION:
Off Highway 89 - US
END DESCRIPTION:
XS GIS Cut Line= 3
      1454885.77      1010598.93      1454275.05      1010306.84
      1453693.91      1010504.49
#Sta/Elev= 30
  4645.2 1332.13  4682.3 1320.63  4711.7 1313.22  4721.1 1309.89  4731.4 1309.02
  4754.3 1304.66  4778.8 1301.23  4815.6 1298.57  4841.8 1295.16  4891.5 1284.14
  4948.4 1281.05  4964.4 1281.23  4980.2 1278.03  4984.0 1275.70  4991.6 1269.90
  5008.4 1269.90  5016.0 1275.70  5026.7 1280.10  5069.5 1283.98  5298.7 1283.07
  5472.2 1285.99  5593.0 1286.55  5657.4 1288.26  5757.3 1287.78  5797.9 1288.67
  5810.7 1289.90  5851.5 1296.97  5897.7 1316.74  5921.4 1323.72  5936.0 1324.84
#Mann=3,-1,0
  4645.2    0.08       0  4984.0    0.04       0  5016.0    0.08       0
#XS Ineff=2,0
    0.00 4970.00 1283.20 5030.00    0.00 1283.20
Permanent Ineff=
       F       F
Bank Sta=4984,5016
XS Rating Curve= 0
Exp/Cntr=0.5,0.3

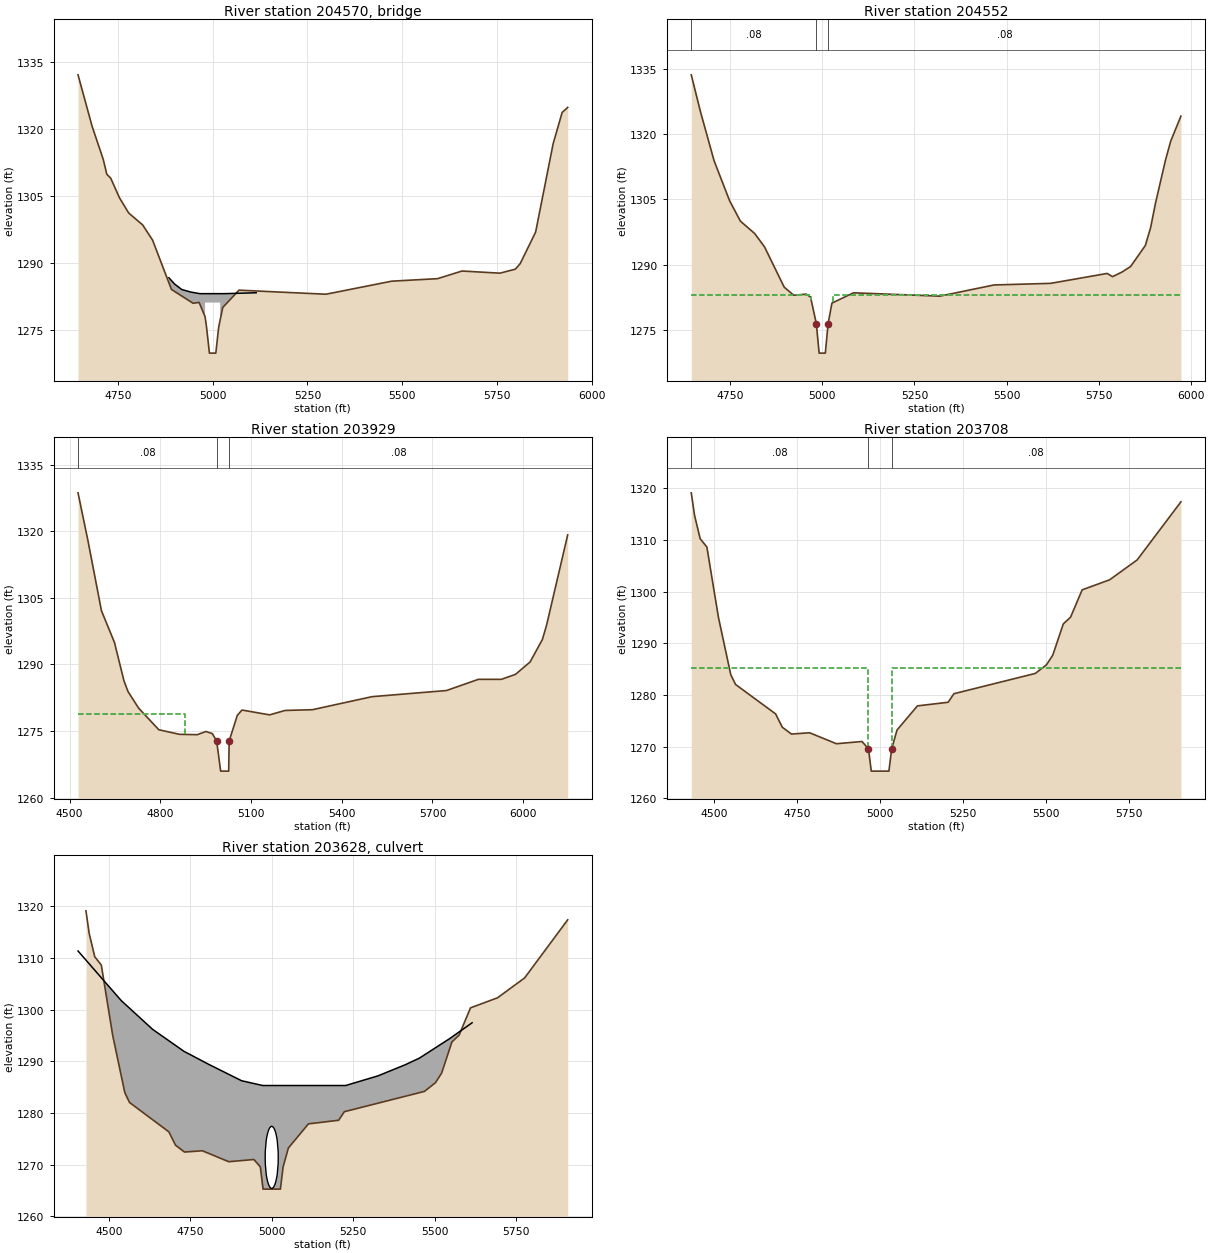
Type RM Length L Ch R =3,204570,,,
BEGIN DESCRIPTION:
Off Highway 89 - TOR
Structure ID: LDS_FR_21
Approximate Survey Structure
END DESCRIPTION:
Bridge Culvert--1,0,-1,-1,0
Deck Dist Width WeirC Skew NumUp NumDn MinLoCord MaxHiCord MaxSubmerge Is_Ogee
18,12,3,,11,11,,,0.95,0,1,1,,,
  4884.7  4899.9  4918.6  4941.7  4966.1  4980.0  4980.0  5020.0  5020.0  5032.2
  5114.9
 1286.75 1285.34 1284.13 1283.57 1283.20 1283.20 1283.20 1283.20 1283.20 1283.20
 1283.40
 1249.90 1249.90 1249.90 1249.90 1249.90 1249.90 1281.20 1281.20 1249.90 1249.90
 1249.90
  4884.7  4899.9  4918.6  4941.7  4966.1  4980.0  4980.0  5020.0  5020.0  5032.2
  5114.9
 1286.75 1285.34 1284.13 1283.57 1283.20 1283.20 1283.20 1283.20 1283.20 1283.20
 1283.40
 1249.90 1249.90 1249.90 1249.90 1249.90 1249.90 1281.20 1281.20 1249.90 1249.90
 1249.90
BR Coef=1,1,0,1.25,0,,,0.8,0,2,0,
WSPro=,,,, 1 ,,,, 0 ,,,, 0 ,,,,-1 ,-1 ,-1 , 0 , 0 , 0 , 0 , 0
BC Design=,,0,,0,,,,,,

Type RM Length L Ch R = 1,204552,623,623,623
BEGIN DESCRIPTION:
Off Highway 89 - DS
END DESCRIPTION:
XS GIS Cut Line= 3
      1454909.35      1010560.56      1454263.25      1010256.69
      1453685.01      1010463.21
#Sta/Elev= 30
  4644.8 1333.59  4669.6 1325.17  4706.7 1313.85  4749.0 1304.62  4778.2 1299.96
  4816.9 1297.12  4843.5 1294.06  4896.9 1284.80  4922.9 1282.95  4957.0 1283.21
  4968.3 1282.52  4984.0 1276.45  4991.6 1269.65  5008.4 1269.65  5016.0 1276.45
  5026.3 1281.14  5084.8 1283.51  5318.8 1282.74  5465.9 1285.31  5619.5 1285.68
  5772.8 1287.96  5787.4 1287.22  5813.6 1288.31  5836.2 1289.54  5876.3 1294.38
  5890.6 1298.49  5903.9 1304.13  5931.1 1314.06  5945.2 1318.37  5972.8 1324.10
#Mann=3,-1,0
  4644.8    0.08       0  4984.0    0.04       0  5016.0    0.08       0
#XS Ineff=2,0
    0.00 4970.00 1283.00 5030.00    0.00 1283.00
Permanent Ineff=
       F       F
Bank Sta=4984,5016
XS Rating Curve= 0
Exp/Cntr=0.5,0.3

Type RM Length L Ch R = 1,203929,221,221,221
BEGIN DESCRIPTION:
Fisher River 408.0
END DESCRIPTION:
XS GIS Cut Line= 4
      1455155.34      1009844.68      1454735.27      1009802.37
      1454626.12      1009823.02      1453696.50      1010384.30
#Sta/Elev= 30
  4527.9 1328.65  4560.5 1317.96  4605.4 1302.09  4648.5 1294.93  4679.8 1286.31
  4693.4 1283.87  4728.4 1280.15  4795.1 1275.29  4863.3 1274.26  4922.2 1274.18
  4950.9 1274.90  4972.0 1274.42  4986.3 1272.77  4999.5 1265.97  5026.1 1265.97
  5027.7 1272.77  5054.7 1278.54  5070.1 1279.73  5161.3 1278.64  5213.0 1279.64
  5302.8 1279.80  5500.1 1282.74  5746.2 1284.12  5851.6 1286.64  5927.8 1286.64
  5974.4 1287.76  6022.8 1290.55  6063.5 1295.63  6077.1 1298.79  6147.1 1319.17
#Mann=3,-1,0
  4527.9    0.08       0  4986.3    0.04       0  5027.7    0.08       0
#XS Ineff=2,0
    0.00 4883.00 1278.73               0
Permanent Ineff=
       F       F
Bank Sta=4986.3,5027.7
XS Rating Curve= 0
Exp/Cntr=0.5,0.3

Type RM Length L Ch R = 1,203708,139,139,139
BEGIN DESCRIPTION:
W Pine St (HWY 89) - US
END DESCRIPTION:
XS GIS Cut Line= 6
      1455131.77      1009723.60      1454664.47      1009622.12
      1454454.42      1009624.48      1454315.18      1009655.16
      1454039.04      1009780.25      1453805.39      1010028.07
#Sta/Elev= 30
  4430.2 1319.09  4440.2 1314.71  4457.2 1310.20  4477.3 1308.61  4512.3 1294.98
  4549.4 1283.92  4563.9 1282.02  4684.7 1276.33  4705.0 1273.75  4732.5 1272.43
  4787.2 1272.68  4868.2 1270.56  4945.4 1270.99  4965.0 1269.56  4973.4 1265.26
  5026.6 1265.26  5035.0 1269.56  5051.1 1273.21  5112.7 1277.88  5205.4 1278.58
  5222.7 1280.23  5468.5 1284.16  5502.1 1285.83  5521.1 1287.69  5552.8 1293.73
  5574.8 1295.04  5609.7 1300.32  5692.7 1302.27  5775.7 1306.11  5907.8 1317.35
#Mann=3,-1,0
  4430.2    0.08       0  4965.0    0.04       0  5035.0    0.08       0
#XS Ineff=2,0
    0.00 4965.00 1285.30 5035.00    0.00 1285.30
Permanent Ineff=
       F       F
Bank Sta=4965,5035
XS Rating Curve= 0
Exp/Cntr=0.5,0.3

Type RM Length L Ch R =2,203628,,,
BEGIN DESCRIPTION:
W Pine St (HWY 89) - TOR
Structure ID: LDS_FR_20
Approximate Survey Structure
END DESCRIPTION:
Bridge Culvert--1,0,-1,-1,0
Deck Dist Width WeirC Skew NumUp NumDn MinLoCord MaxHiCord MaxSubmerge Is_Ogee
60,40,3,,13,13,,,0.95,0,1,1,,,
  4405.9  4538.4  4635.0  4730.8  4805.7  4907.5  4972.3  5226.8  5326.0  5409.2
  5452.2  5545.0  5614.7
 1311.32 1301.73 1296.15 1291.92 1289.43 1286.23 1285.30 1285.30 1287.17 1289.31
 1290.57 1294.34 1297.44
 1245.26 1245.26 1245.26 1245.26 1245.26 1245.26 1245.26 1245.26 1245.26 1245.26
 1245.26 1245.26 1245.26
  4405.9  4538.4  4635.0  4730.8  4805.7  4907.5  4972.3  5226.8  5326.0  5409.2
  5452.2  5545.0  5614.7
 1311.32 1301.73 1296.15 1291.92 1289.43 1286.23 1285.30 1285.30 1287.17 1289.31
 1290.57 1294.34 1297.44
 1245.06 1245.06 1245.06 1245.06 1245.06 1245.06 1245.06 1245.06 1245.06 1245.06
 1245.06 1245.06 1245.06
Culvert=4,12,40,40,0.013,0.5,1,29,1,1265.4,5000,1265.2,5000,Culvert #1,0,60
Culvert Bottom n=0.013
Culvert Bottom Depth=0
Culvert Depth Blocked=0
BC Design=,,0,,0,,,,,,