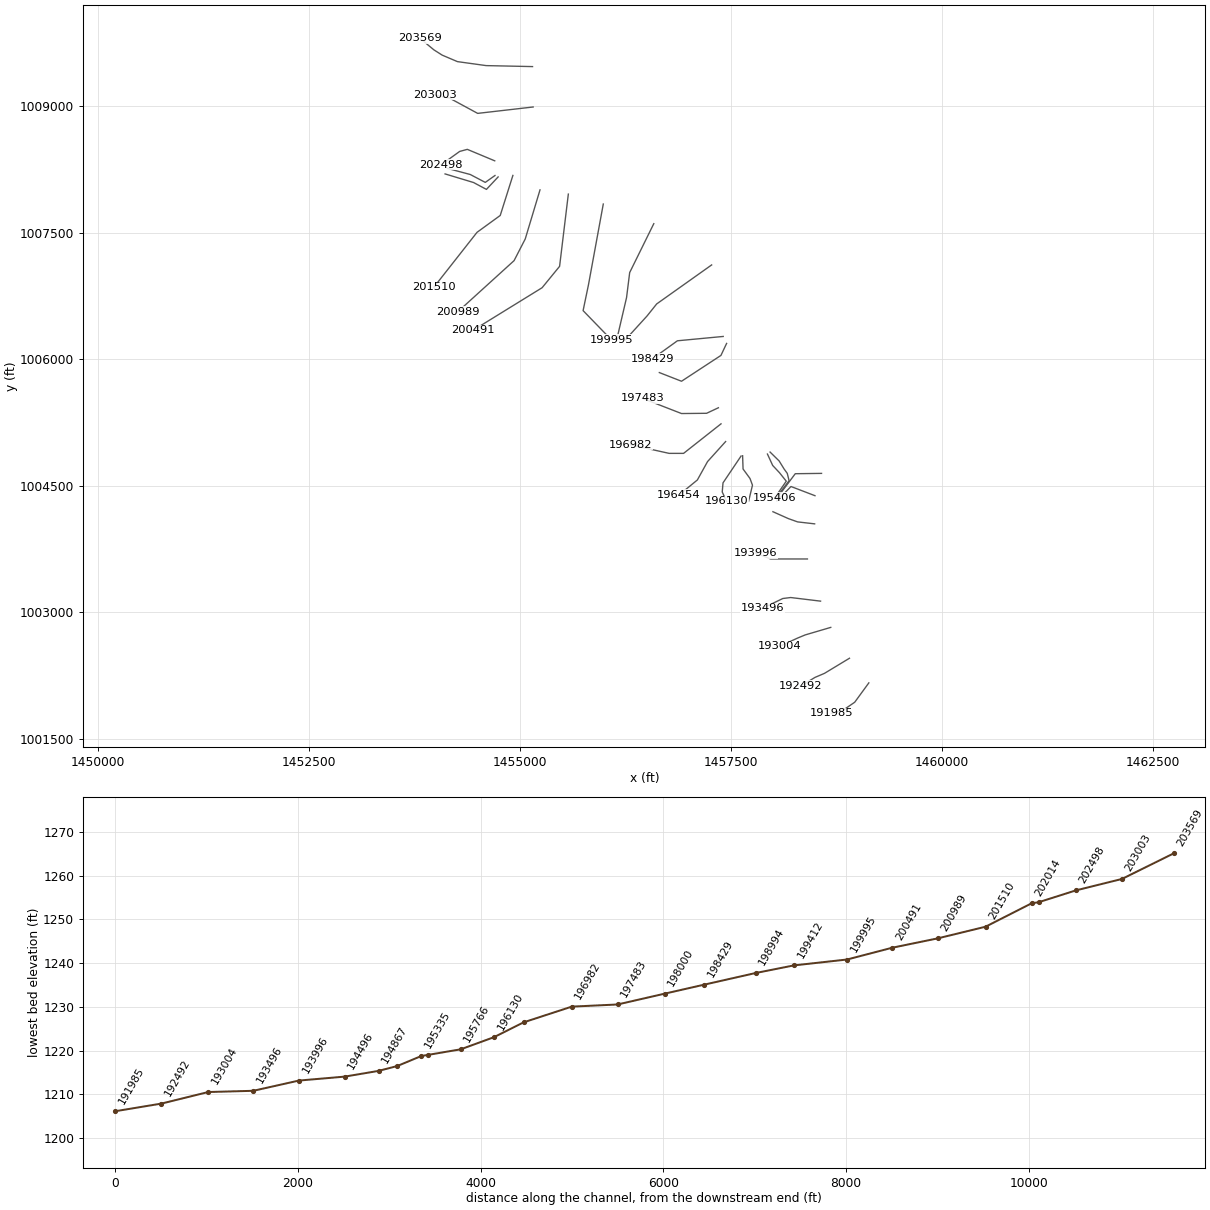
HEC-RAS study Fisher River.prj: Fisher River Limited Detail Study

--- Fisher River.g01 (geometry) --- (continued)

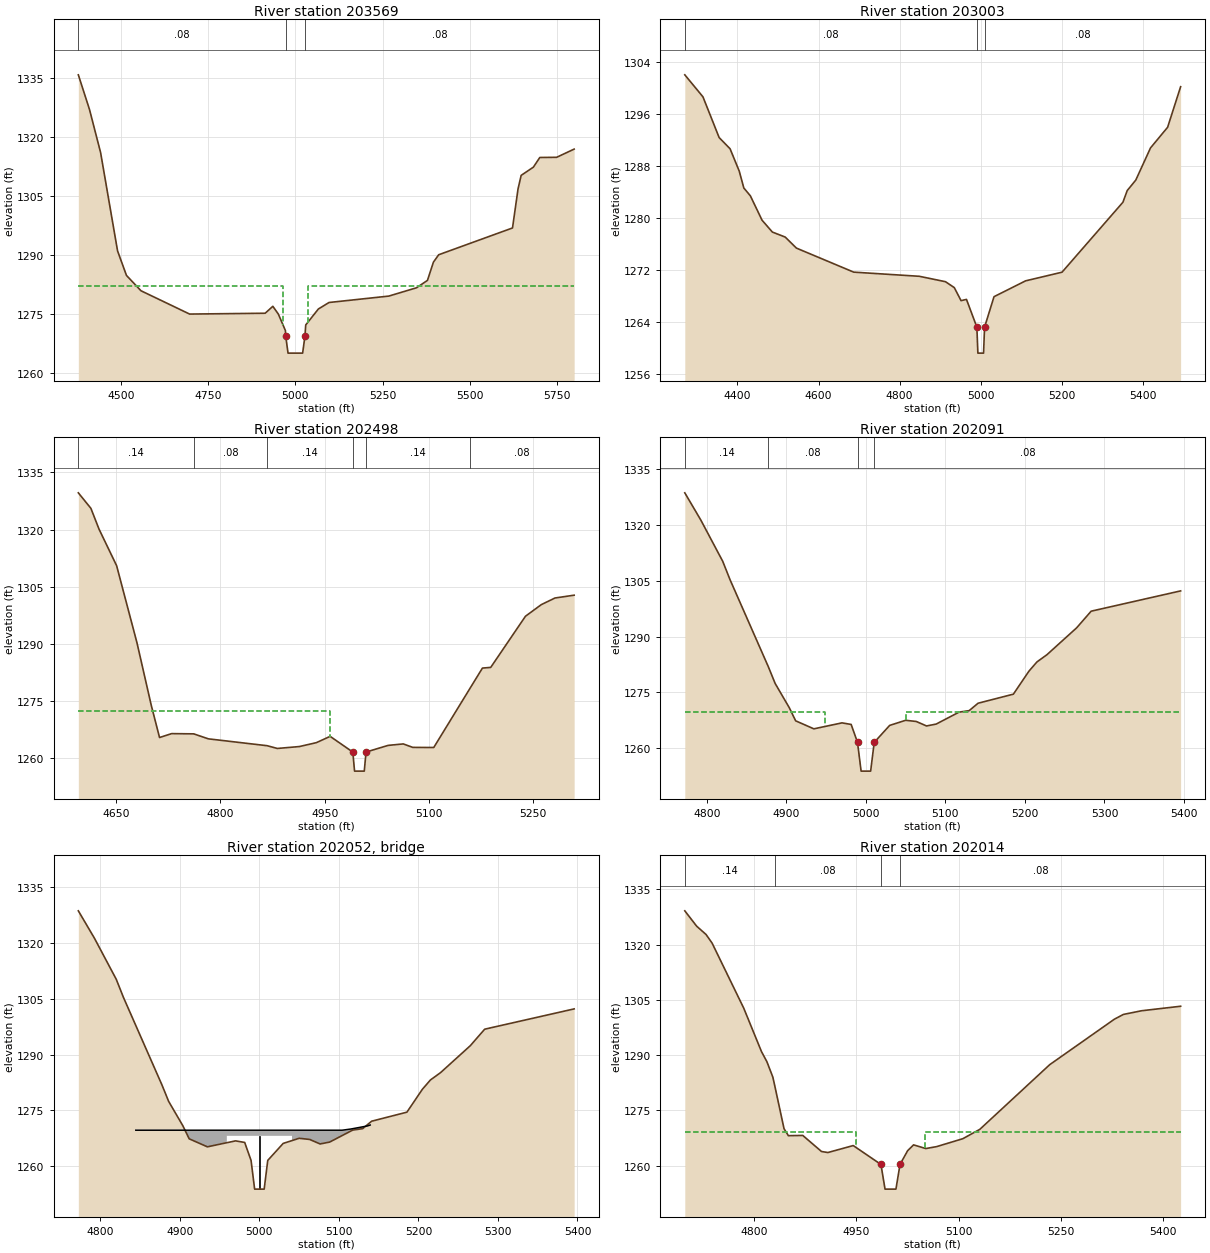
Type RM Length L Ch R = 1,203569,566,566,566
BEGIN DESCRIPTION:
W Pine St (HWY 89) - DS
END DESCRIPTION:
XS GIS Cut Line= 6
      1455145.96      1009471.07      1454596.03      1009482.87
      1454256.17      1009530.07      1454075.94      1009606.75
      1453977.68      1009669.32      1453812.47      1009806.21
#Sta/Elev= 30
  4378.3 1335.81  4410.3 1327.00  4442.1 1316.05  4490.7 1291.05  4516.2 1284.82
  4557.7 1280.92  4697.1 1274.99  4913.5 1275.20  4935.6 1276.96  4951.5 1274.96
  4971.6 1270.79  4972.5 1269.36  4979.1 1265.06  5020.9 1265.06  5027.5 1269.36
  5029.8 1272.22  5066.0 1276.28  5096.5 1277.93  5267.7 1279.56  5347.1 1281.67
  5378.5 1283.55  5395.6 1288.19  5410.7 1290.07  5622.2 1296.88  5638.0 1306.80
  5647.0 1310.25  5682.0 1312.34  5700.4 1314.80  5748.6 1314.84  5798.8 1316.93
#Mann=3,-1,0
  4378.3    0.08       0  4972.5    0.04       0  5027.5    0.08       0
#XS Ineff=2,0
    0.00 4965.00 1282.00 5035.00    0.00 1282.00
Permanent Ineff=
       F       F
Bank Sta=4972.5,5027.5
XS Rating Curve= 0
Exp/Cntr=0.5,0.3

Type RM Length L Ch R = 1,203003,505,505,505
BEGIN DESCRIPTION:
Fisher River 406.0
END DESCRIPTION:
XS GIS Cut Line= 4
      1455153.06      1008991.98      1454495.96      1008916.21
      1454161.77      1009097.47      1453984.74      1009135.94
#Sta/Elev= 30
  4270.2 1302.07  4315.0 1298.68  4354.9 1292.41  4381.9 1290.68  4404.5 1287.24
  4415.8 1284.64  4431.9 1283.44  4460.7 1279.69  4486.2 1277.86  4517.8 1277.09
  4545.5 1275.39  4686.8 1271.69  4848.5 1271.05  4913.0 1270.22  4934.8 1269.31
  4951.5 1267.30  4964.9 1267.49  4990.5 1263.22  4993.0 1259.22  5007.0 1259.22
  5009.5 1263.22  5032.8 1267.91  5110.7 1270.35  5200.5 1271.68  5350.7 1282.45
  5361.3 1284.25  5382.4 1285.86  5418.8 1290.82  5460.9 1293.99  5493.0 1300.24
#Mann=3,-1,0
  4270.2    0.08       0  4990.5    0.04       0  5009.5    0.08       0
Bank Sta=4990.5,5009.5
XS Rating Curve= 0
Exp/Cntr=0.3,0.1

Type RM Length L Ch R = 1,202498,407,407,407
BEGIN DESCRIPTION:
Fisher River 405.0
END DESCRIPTION:
XS GIS Cut Line= 4
      1454698.01      1008353.55      1454373.23      1008489.50
      1454282.61      1008464.96      1454065.52      1008308.28
#Sta/Elev= 30
  4595.4 1329.63  4613.5 1325.56  4625.2 1320.10  4650.5 1310.52  4679.8 1290.29
  4700.3 1273.93  4712.3 1265.42  4729.7 1266.44  4761.5 1266.38  4782.6 1265.07
  4867.2 1263.27  4881.8 1262.55  4913.6 1263.05  4938.0 1264.07  4957.9 1265.72
  4990.5 1261.60  4993.0 1256.60  5007.0 1256.60  5009.5 1261.60  5041.2 1263.35
  5063.1 1263.74  5076.8 1262.83  5107.0 1262.80  5159.3 1278.36  5177.1 1283.64
  5189.0 1283.82  5239.0 1297.24  5261.8 1300.29  5281.5 1302.03  5309.1 1302.77
#Mann=6,-1,0
  4595.4    0.14       0  4761.5    0.08       0  4867.2    0.14       0
  4990.5    0.04       0  5009.5    0.14       0  5159.3    0.08       0
#XS Ineff=2,0
    0.00 4958.30 1272.42               0
Permanent Ineff=
       F       F
Bank Sta=4990.5,5009.5
XS Rating Curve= 0
Exp/Cntr=0.5,0.3

Type RM Length L Ch R = 1,202091,77,77,77
BEGIN DESCRIPTION:
Hidden Valley Rd (4) - US
END DESCRIPTION:
XS GIS Cut Line= 4
      1454701.00      1008179.29      1454586.21      1008097.73
      1454407.97      1008191.38      1454136.13      1008263.87
#Sta/Elev= 30
  4772.3 1328.53  4792.5 1321.21  4820.0 1310.17  4829.0 1305.33  4877.4 1281.87
  4885.9 1277.42  4903.7 1270.91  4911.7 1267.39  4934.6 1265.24  4970.0 1266.84
  4981.5 1266.42  4989.5 1261.60  4994.0 1253.90  5006.0 1253.90  5010.5 1261.60
  5029.9 1266.16  5050.0 1267.53  5063.3 1267.22  5076.3 1266.01  5088.4 1266.52
  5117.2 1269.72  5129.9 1270.12  5141.1 1272.11  5185.5 1274.54  5205.0 1280.69
  5215.1 1283.18  5227.7 1285.12  5265.1 1292.34  5283.3 1296.79  5395.8 1302.23
#Mann=4,-1,0
  4772.3    0.14       0  4877.4    0.08       0  4989.5    0.04       0
  5010.5    0.08       0
#XS Ineff=2,0
    0.00 4949.00 1269.70 5051.00    0.00 1269.70
Permanent Ineff=
       F       F
Bank Sta=4989.5,5010.5
XS Rating Curve= 0
Exp/Cntr=0.5,0.3

Type RM Length L Ch R =3,202052,,,
BEGIN DESCRIPTION:
Hidden Valley Rd (4) - TOR
Structure ID: LDS_FR_19
Approximate Survey Structure
END DESCRIPTION:
Bridge Culvert--1,0,-1,-1,0
Deck Dist Width WeirC Skew NumUp NumDn MinLoCord MaxHiCord MaxSubmerge Is_Ogee
26.5,25,3,,9,9,,,0.95,0,1,1,,,
  4844.6  4959.0  4959.0  5041.0  5041.0  5104.0  5115.3  5135.8  5139.3
 1269.70 1269.70 1269.70 1269.70 1269.70 1269.70 1270.03 1270.84 1271.09
 1233.90 1233.90 1268.20 1268.20 1233.90 1233.90 1233.90 1233.90 1233.90
  4844.6  4959.0  4959.0  5041.0  5041.0  5104.0  5115.3  5135.8  5139.3
 1269.70 1269.70 1269.70 1269.70 1269.70 1269.70 1270.03 1270.84 1271.09
 1233.90 1233.90 1268.20 1268.20 1233.90 1233.90 1233.90 1233.90 1233.90
Pier Skew, UpSta & Num, DnSta & Num=,5000,2,5000,2,0,0,0,0,0
       1       1
 1256.90 1268.20
       1       1
 1256.65 1268.20
Abutment Skew #Up #Dn=,2,2
  4959.0  4965.5
 1268.20 1266.76
  4959.0  4965.3
 1268.20 1262.72
Abutment Skew #Up #Dn=,2,2
  5034.2  5041.0
 1266.46 1268.20
  5034.5  5041.0
 1265.61 1268.20
BR Coef=1,1,0,1.25,0,,,0.8,0,2,0,
WSPro=,,,, 1 ,,,, 0 ,,,, 0 ,,,,-1 ,-1 ,-1 , 0 , 0 , 0 , 0 , 0
BC Design=,,0,,0,,,,,,

Type RM Length L Ch R = 1,202014,504,504,504
BEGIN DESCRIPTION:
Hidden Valley Rd (4) - DS
END DESCRIPTION:
XS GIS Cut Line= 4
      1454738.25      1008162.51      1454599.80      1008014.65
      1454447.25      1008096.22      1454109.86      1008198.17
#Sta/Elev= 30
  4698.0 1329.16  4715.4 1325.00  4729.2 1322.74  4738.1 1320.40  4784.6 1302.73
  4810.6 1290.97  4818.6 1288.20  4827.3 1284.03  4830.2 1281.61  4843.7 1270.05
  4850.1 1268.15  4871.2 1268.22  4898.7 1263.86  4908.1 1263.58  4945.3 1265.47
  4986.0 1260.35  4992.0 1253.65  5008.0 1253.65  5014.0 1260.35  5025.2 1264.08
  5033.9 1265.66  5051.8 1264.66  5067.7 1265.18  5106.2 1267.33  5131.1 1269.86
  5233.8 1287.42  5328.7 1299.75  5342.0 1301.05  5368.8 1302.05  5426.0 1303.27
#Mann=4,-1,0
  4698.0    0.14       0  4830.2    0.08       0  4986.0    0.04       0
  5014.0    0.08       0
#XS Ineff=2,0
    0.00 4949.00 1269.10 5051.00    0.00 1269.10
Permanent Ineff=
       F       F
Bank Sta=4986,5014
XS Rating Curve= 0
Exp/Cntr=0.5,0.3

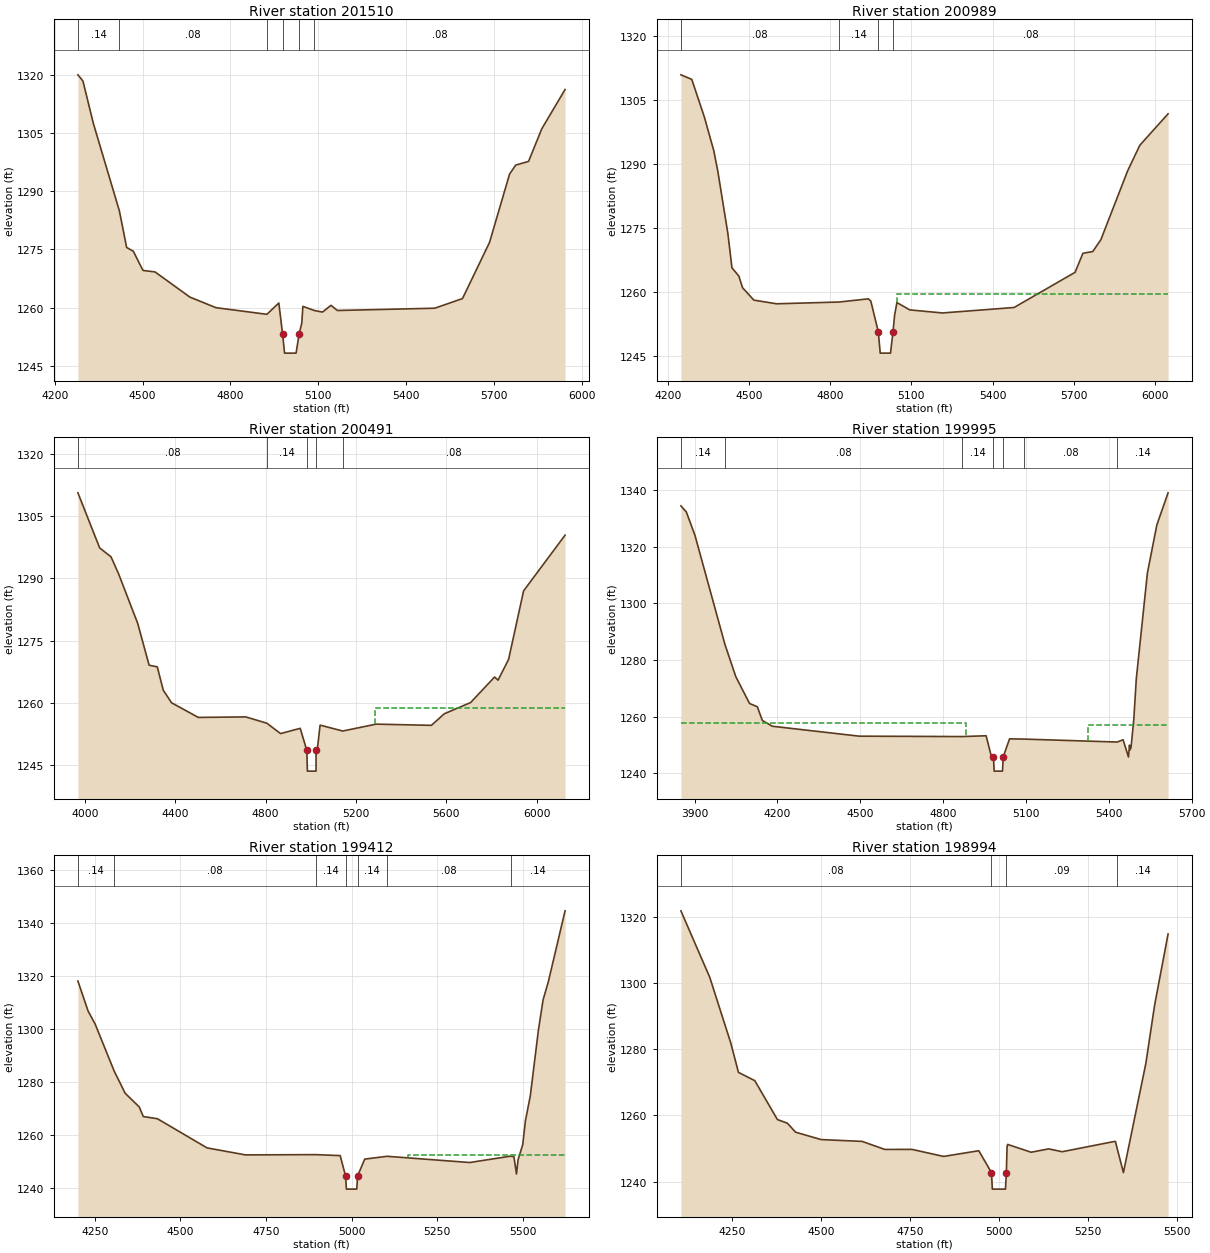
Type RM Length L Ch R = 1,201510,521,521,521
BEGIN DESCRIPTION:
Fisher River 403.0
END DESCRIPTION:
XS GIS Cut Line= 4
      1454913.16      1008180.34      1454763.21      1007705.49
      1454488.30      1007505.56      1453977.79      1006855.81
#Sta/Elev= 30
  4278.9 1319.92  4296.0 1318.35  4332.0 1307.34  4420.6 1284.90  4445.4 1275.50
  4468.3 1274.51  4501.2 1269.58  4542.4 1269.20  4661.3 1262.73  4750.3 1260.00
  4924.5 1258.29  4965.3 1261.19  4978.0 1253.30  4984.9 1248.30  5024.2 1248.30
  5034.8 1253.30  5043.7 1256.03  5047.5 1260.34  5086.8 1259.26  5114.5 1258.87
  5143.5 1260.60  5165.4 1259.27  5497.9 1259.86  5592.7 1262.34  5685.0 1276.78
  5753.6 1294.39  5774.5 1296.69  5818.4 1297.64  5863.4 1306.01  5943.1 1316.14
#Mann=6,-1,0
  4278.9    0.14       0  4420.6    0.08       0  4924.5    0.14       0
  4978.0    0.04       0  5034.8    0.14       0  5086.8    0.08       0
Bank Sta=4978,5034.8
XS Rating Curve= 0
Exp/Cntr=0.3,0.1

Type RM Length L Ch R = 1,200989,498,498,498
BEGIN DESCRIPTION:
Fisher River 402.0
END DESCRIPTION:
XS GIS Cut Line= 4
      1455234.47      1008008.93      1455059.54      1007427.01
      1454927.44      1007169.96      1454259.83      1006563.04
#Sta/Elev= 30
  4248.9 1310.85  4289.0 1309.79  4335.4 1300.98  4370.1 1293.12  4384.7 1288.46
  4422.4 1273.65  4437.4 1265.64  4462.9 1263.70  4476.5 1260.98  4518.2 1258.07
  4602.0 1257.21  4832.8 1257.62  4941.3 1258.37  4950.2 1257.83  4977.8 1250.65
  4984.9 1245.65  5022.8 1245.65  5032.2 1250.65  5037.8 1254.45  5046.5 1257.50
  5093.9 1255.78  5214.4 1255.06  5479.1 1256.34  5704.4 1264.58  5733.3 1269.04
  5769.7 1269.45  5799.6 1272.22  5898.8 1288.40  5943.4 1294.34  6047.8 1301.72
#Mann=4,-1,0
  4248.9    0.08       0  4832.8    0.14       0  4977.8    0.04       0
  5032.2    0.08       0
#XS Ineff=2,0
       0                 5047.30    0.00 1259.39
Permanent Ineff=
       F       F
Bank Sta=4977.8,5032.2
XS Rating Curve= 0
Exp/Cntr=0.3,0.1

Type RM Length L Ch R = 1,200491,496,496,496
BEGIN DESCRIPTION:
Fisher River 401.0
END DESCRIPTION:
XS GIS Cut Line= 4
      1455570.08      1007958.99      1455466.54      1007102.12
      1455259.47      1006848.64      1454438.28      1006341.65
#Sta/Elev= 30
  3969.5 1310.61  4065.9 1297.32  4116.0 1295.18  4149.9 1291.03  4234.2 1279.12
  4284.6 1269.05  4320.7 1268.65  4347.3 1263.01  4383.8 1260.00  4502.1 1256.46
  4712.6 1256.58  4805.7 1255.06  4866.2 1252.56  4953.1 1253.83  4982.4 1248.51
  4984.9 1243.51  5023.2 1243.51  5023.3 1248.51  5028.3 1248.52  5041.1 1254.60
  5141.3 1253.18  5289.2 1254.84  5533.7 1254.55  5590.7 1257.34  5707.0 1260.04
  5813.2 1266.20  5828.5 1265.44  5875.2 1270.46  5941.5 1286.97  6125.0 1300.40
#Mann=5,-1,0
  3969.5    0.08       0  4805.7    0.14       0  4982.4    0.04       0
  5023.3    0.14       0  5141.3    0.08       0
#XS Ineff=2,0
       0                 5285.10    0.00 1258.85
Permanent Ineff=
       F       F
Bank Sta=4982.4,5023.3
XS Rating Curve= 0
Exp/Cntr=0.3,0.1

Type RM Length L Ch R = 1,199995,583,583,583
BEGIN DESCRIPTION:
Fisher River 400.0
END DESCRIPTION:
XS GIS Cut Line= 4
      1455984.22      1007841.18      1455808.56      1006882.77
      1455745.01      1006576.95      1456077.03      1006234.22
#Sta/Elev= 30
  3850.7 1334.46  3870.2 1332.32  3901.6 1324.04  4010.0 1285.58  4049.4 1274.17
  4099.3 1264.68  4127.3 1263.54  4145.5 1258.71  4181.3 1256.66  4496.4 1253.15
  4868.6 1253.01  4955.8 1253.29  4973.0 1246.68  4982.4 1245.81  4984.9 1240.81
  5015.1 1240.81  5017.6 1245.81  5040.7 1252.21  5094.7 1252.11  5430.8 1251.08
  5451.7 1251.89  5471.3 1245.81  5474.9 1250.00  5476.9 1248.32  5480.5 1249.13
  5490.7 1259.32  5499.5 1273.35  5539.8 1310.77  5574.0 1327.74  5614.6 1339.05
#Mann=7,-1,0
  3850.7    0.14       0  4010.0    0.08       0  4868.6    0.14       0
  4982.4    0.04       0  5017.6    0.14       0  5094.7    0.08       0
  5430.8    0.14       0
#XS Ineff=2,0
    0.00 4883.90 1257.73 5326.00    0.00 1257.00
Permanent Ineff=
       F       F
Bank Sta=4982.4,5017.6
XS Rating Curve= 0
Exp/Cntr=0.3,0.1

Type RM Length L Ch R = 1,199412,418,418,418
BEGIN DESCRIPTION:
Fisher River 399.0
END DESCRIPTION:
XS GIS Cut Line= 4
      1456582.57      1007608.21      1456296.96      1007028.44
      1456259.83      1006731.39      1456151.30      1006265.83
#Sta/Elev= 30
  4200.2 1318.06  4230.0 1306.74  4250.8 1301.75  4306.0 1284.12  4338.3 1275.68
  4379.6 1270.49  4391.3 1266.87  4432.6 1266.05  4577.5 1255.04  4689.8 1252.39
  4895.1 1252.49  4966.7 1252.12  4982.4 1244.46  4984.9 1239.46  5015.1 1239.46
  5017.6 1244.46  5038.5 1250.80  5103.6 1251.86  5345.3 1249.51  5464.8 1251.92
  5474.4 1251.75  5481.9 1245.16  5486.5 1250.53  5500.1 1256.22  5508.1 1265.35
  5522.2 1274.59  5546.0 1299.53  5559.7 1310.99  5575.0 1317.79  5623.9 1344.58
#Mann=7,-1,0
  4200.2    0.14       0  4306.0    0.08       0  4895.1    0.14       0
  4982.4    0.04       0  5017.6    0.14       0  5103.6    0.08       0
  5464.8    0.14       0
#XS Ineff=2,0
       0                 5164.20    0.00 1252.20
Permanent Ineff=
       F       F
Bank Sta=4982.4,5017.6
XS Rating Curve= 0
Exp/Cntr=0.3,0.1

Type RM Length L Ch R = 1,198994,565,565,565
BEGIN DESCRIPTION:
Fisher River 398.0
END DESCRIPTION:
XS GIS Cut Line= 4
      1457268.05      1007118.97      1456616.85      1006656.28
      1456502.61      1006513.47      1456242.69      1006227.85
#Sta/Elev= 30
  4107.1 1321.73  4188.0 1301.69  4246.9 1281.93  4268.7 1272.96  4314.6 1270.46
  4378.1 1258.72  4406.1 1257.62  4429.1 1254.91  4500.6 1252.68  4615.8 1252.13
  4679.7 1249.70  4755.8 1249.72  4844.6 1247.59  4943.5 1249.31  4979.1 1242.72
  4981.6 1237.72  5018.4 1237.72  5020.9 1242.72  5023.0 1250.66  5024.6 1251.21
  5090.5 1248.86  5139.9 1249.87  5177.6 1249.01  5322.9 1252.08  5327.3 1252.10
  5331.4 1250.27  5349.6 1242.72  5412.5 1275.61  5437.2 1293.25  5475.0 1314.73
#Mann=4,-1,0
  4107.1    0.08       0  4979.1    0.04       0  5020.9    0.09       0
  5331.4    0.14       0
#XS Ineff=2,0
       0                 5029.90    0.00 1250.94
Permanent Ineff=
       F       F
Bank Sta=4979.1,5020.9
XS Rating Curve= 0
Exp/Cntr=0.3,0.1

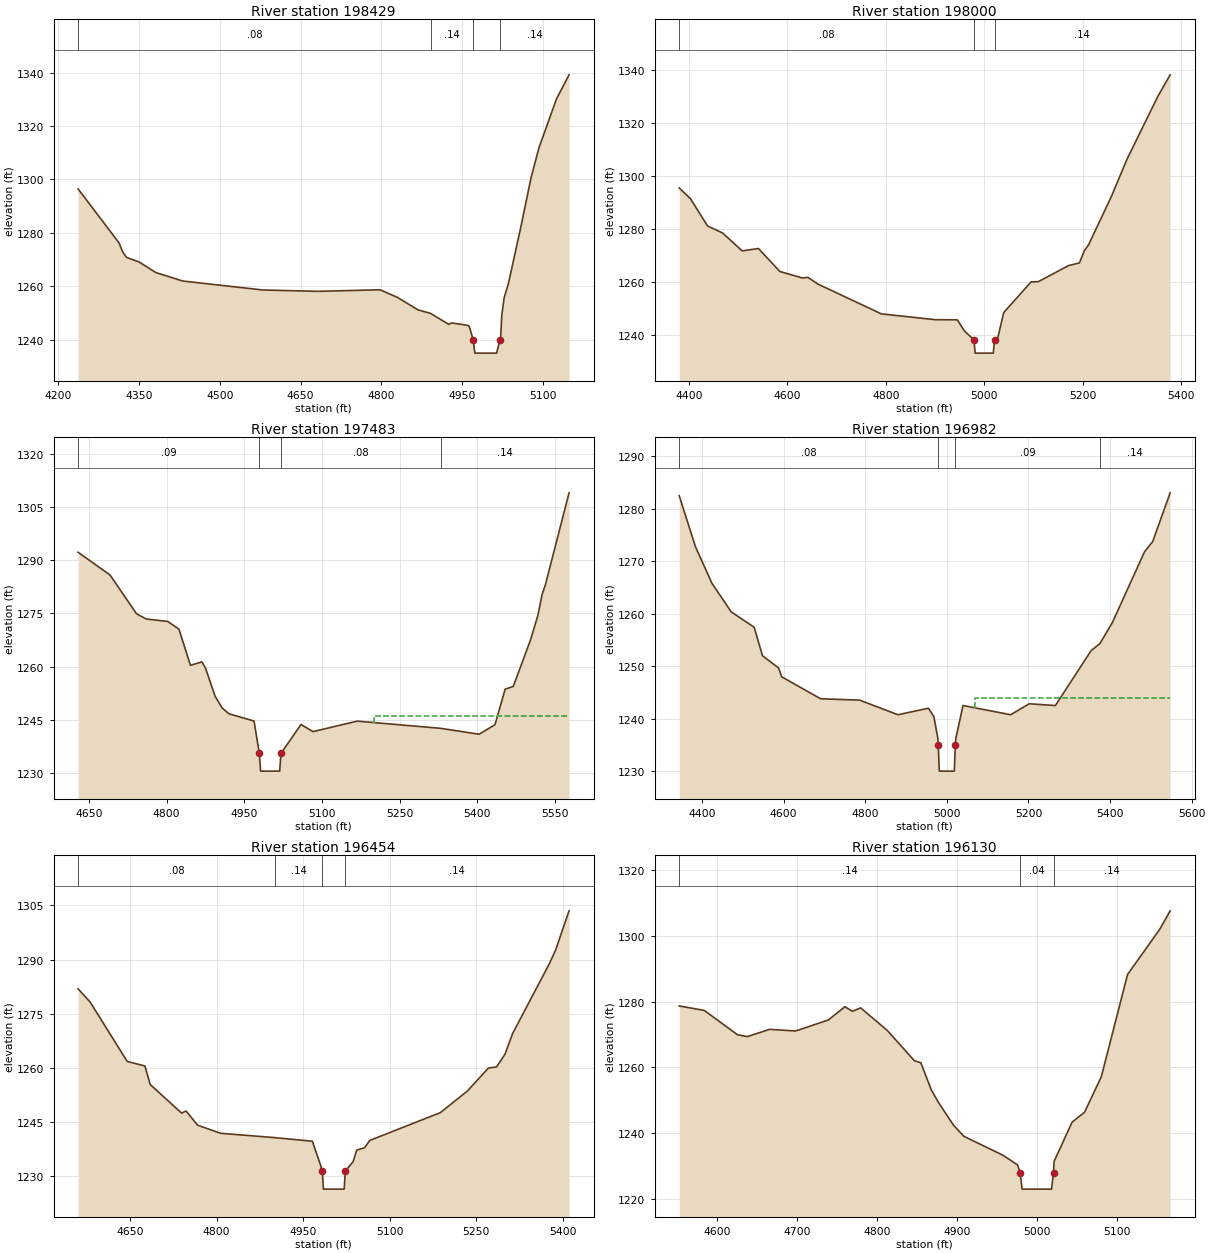
Type RM Length L Ch R = 1,198429,429,429,429
BEGIN DESCRIPTION:
Fisher River 397.0
END DESCRIPTION:
XS GIS Cut Line= 3
      1457405.13      1006270.69      1456862.48      1006219.29
      1456565.44      1006005.07
#Sta/Elev= 30
  4237.0 1296.48  4312.9 1276.31  4319.4 1273.04  4326.8 1270.86  4350.0 1269.17
  4381.3 1265.18  4431.4 1262.01  4579.6 1258.67  4682.3 1258.15  4797.4 1258.75
  4829.6 1255.92  4867.6 1251.27  4891.3 1249.90  4925.0 1245.81  4930.3 1246.34
  4960.3 1245.45  4963.0 1245.07  4970.4 1240.05  4973.5 1235.05  5013.9 1235.05
  5020.1 1240.05  5021.1 1240.05  5023.5 1249.30  5027.9 1255.82  5035.5 1260.86
  5058.5 1281.88  5077.8 1300.65  5092.5 1311.87  5125.0 1330.12  5148.3 1339.13
#Mann=4,-1,0
  4237.0    0.08       0  4891.3    0.14       0  4970.4    0.04       0
  5020.1    0.14       0
Bank Sta=4970.4,5020.1
XS Rating Curve= 0
Exp/Cntr=0.3,0.1

Type RM Length L Ch R = 1,198000,517,517,517
BEGIN DESCRIPTION:
Fisher River 396.0
END DESCRIPTION:
XS GIS Cut Line= 4
      1457445.14      1006187.87      1457378.16      1006045.67
      1456911.04      1005739.45      1456648.27      1005842.27
#Sta/Elev= 30
  4380.0 1295.35  4402.8 1291.32  4437.6 1281.01  4468.3 1278.35  4508.0 1271.60
  4541.1 1272.49  4584.7 1263.82  4630.6 1261.36  4641.8 1261.61  4662.1 1259.06
  4790.9 1247.83  4901.0 1245.62  4945.2 1245.59  4959.8 1241.36  4979.1 1238.01
  4981.6 1233.01  5018.4 1233.01  5020.9 1238.01  5026.6 1238.10  5039.7 1248.34
  5095.4 1259.92  5109.8 1259.97  5171.0 1266.03  5193.6 1267.06  5203.4 1271.63
  5212.0 1273.86  5258.1 1292.00  5290.1 1306.16  5352.6 1329.82  5377.9 1338.05
#Mann=3,-1,0
  4380.0    0.08       0  4979.1    0.04       0  5020.9    0.14       0
Bank Sta=4979.1,5020.9
XS Rating Curve= 0
Exp/Cntr=0.3,0.1

Type RM Length L Ch R = 1,197483,501,501,501
BEGIN DESCRIPTION:
Fisher River 395.0
END DESCRIPTION:
XS GIS Cut Line= 4
      1457348.04      1005425.00      1457208.08      1005359.30
      1456911.04      1005356.44      1456448.36      1005536.37
#Sta/Elev= 30
  4629.1 1292.21  4690.7 1285.82  4742.0 1274.87  4761.0 1273.39  4802.1 1272.72
  4823.9 1270.54  4846.1 1260.35  4868.1 1261.32  4875.1 1259.60  4893.7 1251.65
  4907.2 1248.35  4920.6 1246.68  4968.9 1244.65  4979.1 1235.53  4981.6 1230.53
  5018.4 1230.53  5020.9 1235.53  5059.6 1243.67  5082.9 1241.67  5168.1 1244.62
  5329.2 1242.59  5403.5 1240.93  5434.2 1243.61  5453.8 1253.63  5469.5 1254.40
  5503.1 1267.62  5517.0 1274.42  5525.1 1280.29  5531.4 1282.97  5577.2 1308.96
#Mann=4,-1,0
  4629.1    0.09       0  4979.1    0.04       0  5020.9    0.08       0
  5329.2    0.14       0
#XS Ineff=2,0
       0                 5200.00    0.00 1246.00
Permanent Ineff=
       F       F
Bank Sta=4979.1,5020.9
XS Rating Curve= 0
Exp/Cntr=0.3,0.1

Type RM Length L Ch R = 1,196982,528,528,528
BEGIN DESCRIPTION:
Fisher River 394.0
END DESCRIPTION:
XS GIS Cut Line= 4
      1457379.15      1005234.35      1456935.51      1004884.11
      1456764.26      1004884.11      1456308.86      1004985.31
#Sta/Elev= 30
  4344.3 1282.46  4384.4 1272.70  4424.4 1265.81  4471.7 1260.35  4528.0 1257.42
  4548.3 1252.01  4588.0 1249.66  4595.4 1247.99  4690.8 1243.81  4786.5 1243.55
  4880.3 1240.77  4955.0 1242.01  4968.3 1240.41  4978.2 1236.24  4978.5 1235.14
  4979.1 1235.04  4981.6 1230.04  5018.4 1230.04  5020.9 1235.04  5021.8 1236.11
  5039.7 1242.53  5156.5 1240.77  5202.1 1242.86  5266.1 1242.52  5353.5 1252.96
  5375.1 1254.31  5405.7 1258.31  5484.5 1271.78  5504.6 1273.74  5547.3 1283.00
#Mann=4,-1,0
  4344.3    0.08       0  4979.1    0.04       0  5020.9    0.09       0
  5375.1    0.14       0
#XS Ineff=2,0
       0                 5068.20    0.00 1244.04
Permanent Ineff=
       F       F
Bank Sta=4979.1,5020.9
XS Rating Curve= 0
Exp/Cntr=0.3,0.1

Type RM Length L Ch R = 1,196454,324,324,324
BEGIN DESCRIPTION:
Fisher River 393.0
END DESCRIPTION:
XS GIS Cut Line= 4
      1457433.69      1005024.23      1457219.62      1004786.81
      1457098.97      1004568.86      1456881.05      1004389.86
#Sta/Elev= 30
  4560.1 1281.90  4580.9 1278.26  4645.3 1261.78  4675.9 1260.54  4685.1 1255.41
  4739.4 1247.49  4747.3 1248.06  4767.3 1244.13  4807.2 1241.90  4901.5 1240.69
  4966.1 1239.70  4981.4 1232.55  4981.6 1231.44  4983.3 1231.44  4985.3 1226.44
  5021.2 1226.44  5023.2 1231.44  5036.8 1234.07  5042.9 1237.23  5056.5 1237.90
  5065.7 1239.93  5187.8 1247.61  5234.9 1253.62  5271.1 1259.96  5285.3 1260.28
  5300.0 1263.82  5313.0 1269.48  5377.0 1288.91  5387.7 1292.67  5410.9 1303.49
#Mann=4,-1,0
  4560.1    0.08       0  4901.5    0.14       0  4983.3    0.04       0
  5023.2    0.14       0
Bank Sta=4983.3,5023.2
XS Rating Curve= 0
Exp/Cntr=0.3,0.1

Type RM Length L Ch R = 1,196130,364,364,364
BEGIN DESCRIPTION:
Fisher River 392.0
END DESCRIPTION:
XS GIS Cut Line= 4
      1457616.49      1004852.18      1457402.64      1004534.15
      1457393.50      1004426.31      1457444.70      1004314.77
#Sta/Elev= 30
  4552.6 1278.66  4583.9 1277.31  4625.7 1269.90  4637.9 1269.35  4665.7 1271.56
  4698.3 1271.06  4739.0 1274.38  4760.0 1278.42  4769.2 1277.03  4779.7 1278.07
  4812.9 1271.23  4846.9 1262.02  4854.9 1261.42  4867.8 1253.29  4876.3 1249.62
  4895.9 1242.42  4908.8 1239.08  4957.8 1233.32  4975.9 1230.40  4979.1 1228.05
  4981.6 1223.05  5018.4 1223.05  5020.9 1228.05  5021.6 1231.45  5044.1 1243.38
  5059.7 1246.40  5080.6 1257.10  5113.5 1288.20  5154.0 1302.02  5166.8 1307.54
#Mann=3,-1,0
  4552.6    0.14       0  4979.1    0.04       0  5020.9    0.14       0
Bank Sta=4979.1,5020.9
XS Rating Curve= 0
Exp/Cntr=0.3,0.1

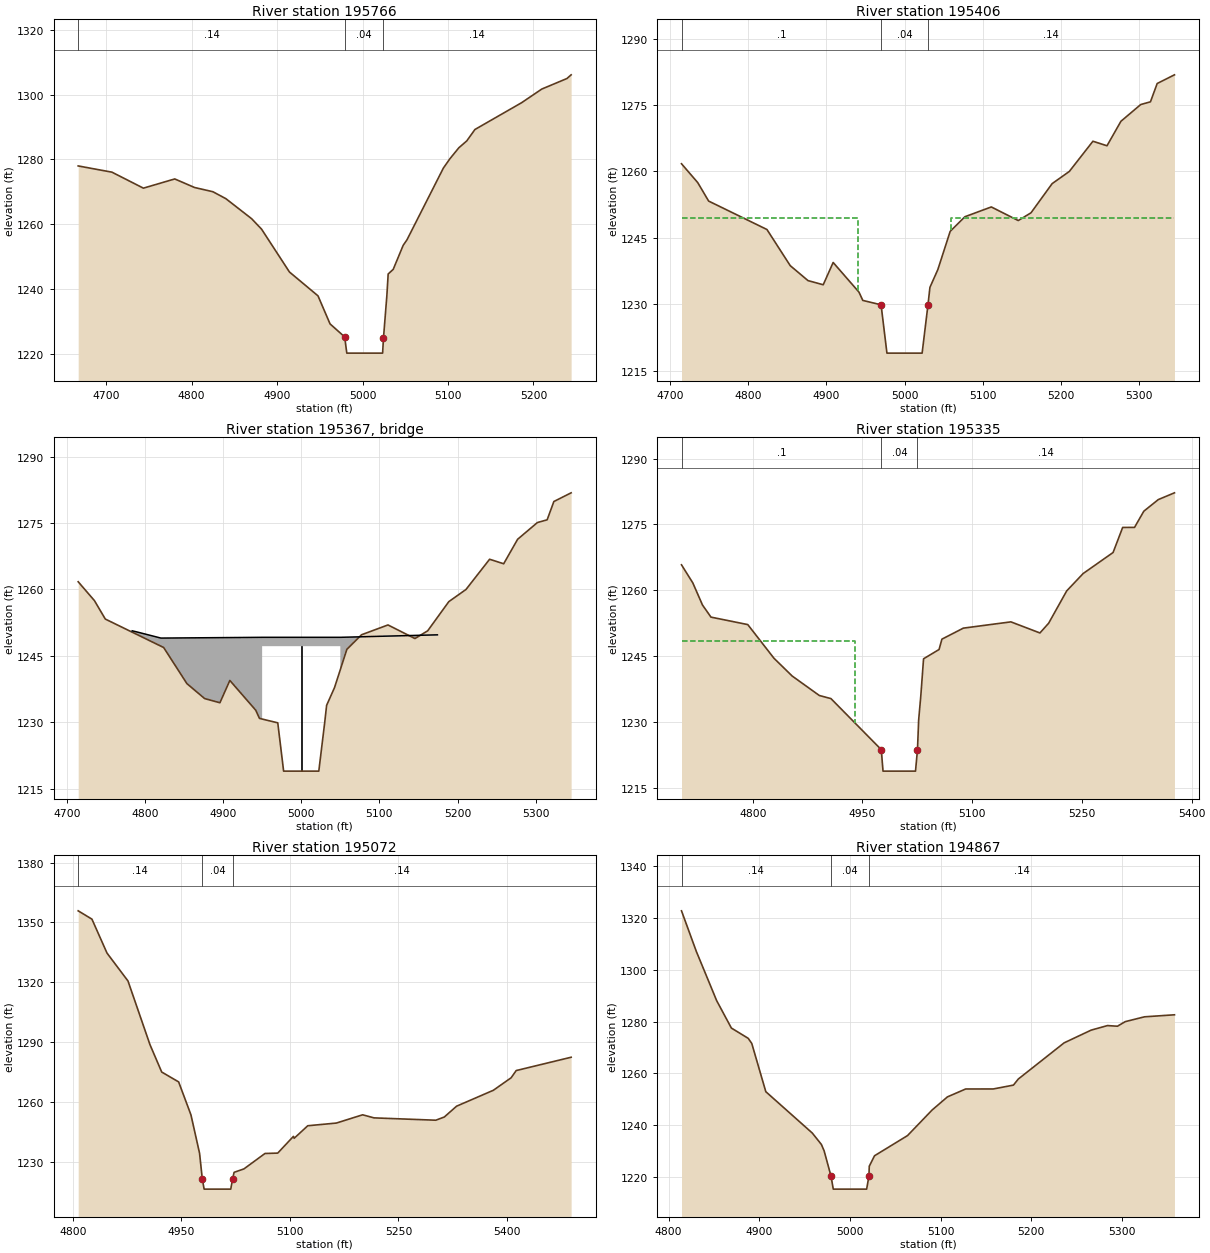
Type RM Length L Ch R = 1,195766,360,360,360
BEGIN DESCRIPTION:
Fisher River 391.0
END DESCRIPTION:
XS GIS Cut Line= 5
      1457634.79      1004855.92      1457640.27      1004698.67
      1457722.37      1004586.21      1457751.78      1004506.74
      1457706.09      1004316.67
#Sta/Elev= 30
  4667.3 1277.99  4706.8 1276.07  4743.6 1271.14  4780.3 1273.98  4803.5 1271.34
  4824.9 1270.04  4840.1 1267.90  4870.2 1261.73  4881.9 1258.49  4914.5 1245.29
  4947.9 1237.94  4962.0 1229.29  4979.1 1225.28  4981.6 1220.28  5023.5 1220.28
  5024.5 1224.88  5028.5 1238.10  5030.0 1244.68  5035.9 1246.10  5047.6 1253.53
  5051.9 1255.16  5094.6 1277.33  5102.1 1280.16  5112.6 1283.56  5122.0 1285.72
  5131.5 1289.22  5186.1 1297.48  5209.8 1301.70  5239.1 1304.93  5244.1 1306.08
#Mann=3,-1,0
  4667.3    0.14       0  4979.1    0.04       0  5024.5    0.14       0
Bank Sta=4979.1,5024.5
XS Rating Curve= 0
Exp/Cntr=0.5,0.3

Type RM Length L Ch R = 1,195406,71,71,71
BEGIN DESCRIPTION:
Hidden Valley RD (3) - US
END DESCRIPTION:
XS GIS Cut Line= 5
      1457929.07      1004876.01      1457991.24      1004740.71
      1458071.67      1004654.80      1458152.09      1004554.26
      1458018.65      1004360.49
#Sta/Elev= 30
  4714.7 1261.74  4735.5 1257.48  4749.4 1253.32  4824.0 1246.90  4853.8 1238.74
  4876.5 1235.37  4896.0 1234.43  4908.7 1239.46  4941.8 1232.75  4946.6 1230.90
  4970.0 1229.90  4977.5 1219.00  5022.5 1219.00  5030.0 1229.90  5032.5 1233.85
  5042.6 1237.85  5058.4 1246.48  5077.2 1249.78  5111.0 1251.99  5145.5 1248.92
  5161.8 1250.67  5188.8 1257.25  5210.8 1260.00  5241.0 1266.82  5259.0 1265.80
  5276.8 1271.32  5302.1 1275.10  5314.6 1275.72  5323.2 1279.85  5345.3 1281.81
#Mann=3,-1,0
  4714.7     0.1       0  4970.0    0.04       0  5030.0    0.14       0
#XS Ineff=2,0
    0.00 4940.00 1249.40 5060.00    0.00 1249.40
Permanent Ineff=
       F       F
Bank Sta=4970,5030
XS Rating Curve= 0
Exp/Cntr=0.5,0.3

Type RM Length L Ch R =3,195367,,,
BEGIN DESCRIPTION:
Hidden Valley RD (3) - TOR
Structure ID: LDS_FR_18
Approximate Survey Structure
END DESCRIPTION:
Bridge Culvert--1,0,-1,-1,0
Deck Dist Width WeirC Skew NumUp NumDn MinLoCord MaxHiCord MaxSubmerge Is_Ogee
26.5,25,3,,8,8,,,0.95,0,1,1,,,
  4783.8  4790.8  4820.5  4950.0  4950.0  5050.0  5050.0  5174.2
 1250.67 1250.37 1249.03 1249.20 1249.20 1249.20 1249.20 1249.76
 1199.00 1199.00 1199.00 1199.00 1247.20 1247.20 1199.00 1199.00
  4783.8  4790.8  4820.5  4950.0  4950.0  5050.0  5050.0  5174.2
 1250.67 1250.37 1249.03 1249.20 1249.20 1249.20 1249.20 1249.76
 1199.00 1199.00 1199.00 1199.00 1247.20 1247.20 1199.00 1199.00
Pier Skew, UpSta & Num, DnSta & Num=,5000,2,5000,2,0,0,0,0,0
       1       1
 1219.00 1247.20
       1       1
 1218.75 1247.20
BR Coef=1,1,0,1.25,0,,,0.8,0,2,0,
WSPro=,,,, 1 ,,,, 0 ,,,, 0 ,,,,-1 ,-1 ,-1 , 0 , 0 , 0 , 0 , 0
BC Design=,,0,,0,,,,,,

Type RM Length L Ch R = 1,195335,263,263,263
BEGIN DESCRIPTION:
Hidden Valley Rd (3) - DS
END DESCRIPTION:
XS GIS Cut Line= 6
      1457960.18      1004899.72      1458068.01      1004793.72
      1458126.50      1004698.67      1458164.12      1004646.52
      1458185.59      1004559.80      1458029.61      1004355.00
#Sta/Elev= 30
  4702.6 1265.77  4718.1 1261.64  4731.3 1256.61  4742.9 1253.85  4793.2 1252.15
  4829.0 1244.48  4853.8 1240.44  4891.0 1235.99  4906.9 1235.28  4975.7 1223.65
  4978.1 1218.75  5022.5 1218.75  5025.2 1223.65  5026.8 1230.38  5029.7 1235.81
  5033.5 1244.35  5054.7 1246.47  5058.6 1248.83  5087.9 1251.34  5152.9 1252.77
  5192.6 1250.24  5204.5 1252.46  5229.2 1259.83  5251.7 1263.79  5292.6 1268.58
  5305.7 1274.29  5321.9 1274.30  5334.6 1277.99  5354.4 1280.64  5376.5 1282.18
#Mann=3,-1,0
  4702.6     0.1       0  4975.7    0.04       0  5025.2    0.14       0
#XS Ineff=2,0
    0.00 4940.00 1248.30 5060.00    0.00 1248.30
Permanent Ineff=
       F       F
Bank Sta=4975.7,5025.2
XS Rating Curve= 0
Exp/Cntr=0.5,0.3

Type RM Length L Ch R = 1,195072,205,205,205
BEGIN DESCRIPTION:
Fisher River 390.5
END DESCRIPTION:
XS GIS Cut Line= 3
      1458570.12      1004646.70      1458258.77      1004642.81
      1458036.94      1004347.03
#Sta/Elev= 30
  4807.6 1355.83  4826.6 1351.66  4847.4 1334.68  4876.4 1320.70  4906.8 1288.80
  4923.0 1275.10  4946.4 1270.15  4963.4 1253.66  4975.3 1234.44  4979.1 1221.46
  4981.6 1216.46  5018.4 1216.46  5020.9 1221.46  5023.0 1224.87  5036.6 1226.59
  5065.7 1234.31  5083.3 1234.50  5105.0 1242.89  5106.0 1241.92  5124.8 1248.20
  5164.2 1249.54  5200.6 1253.68  5216.4 1252.14  5301.7 1250.97  5313.5 1252.59
  5330.4 1257.99  5381.2 1265.96  5405.8 1272.23  5412.8 1275.84  5488.7 1282.51
#Mann=3,-1,0
  4807.6    0.14       0  4979.1    0.04       0  5020.9    0.14       0
Bank Sta=4979.1,5020.9
XS Rating Curve= 0
Exp/Cntr=0.3,0.1

Type RM Length L Ch R = 1,194867,371,371,371
BEGIN DESCRIPTION:
Fisher River 390.0
END DESCRIPTION:
XS GIS Cut Line= 3
      1458492.29      1004382.04      1458208.18      1004491.02
      1458040.85      1004319.80
#Sta/Elev= 30
  4814.2 1322.79  4830.5 1307.17  4853.0 1288.10  4869.2 1277.54  4887.8 1273.56
  4891.7 1271.59  4907.2 1252.96  4958.4 1237.02  4968.5 1232.59  4971.5 1230.14
  4979.1 1220.35  4981.6 1215.35  5018.4 1215.35  5020.9 1220.35  5021.3 1224.20
  5027.1 1228.23  5063.5 1236.02  5090.6 1245.89  5107.5 1250.96  5127.6 1254.01
  5158.1 1254.02  5180.3 1255.51  5185.7 1257.86  5236.2 1271.82  5266.0 1276.73
  5284.0 1278.49  5295.0 1278.24  5303.6 1280.01  5324.8 1281.87  5357.9 1282.65
#Mann=3,-1,0
  4814.2    0.14       0  4979.1    0.04       0  5020.9    0.14       0
Bank Sta=4979.1,5020.9
XS Rating Curve= 0
Exp/Cntr=0.3,0.1

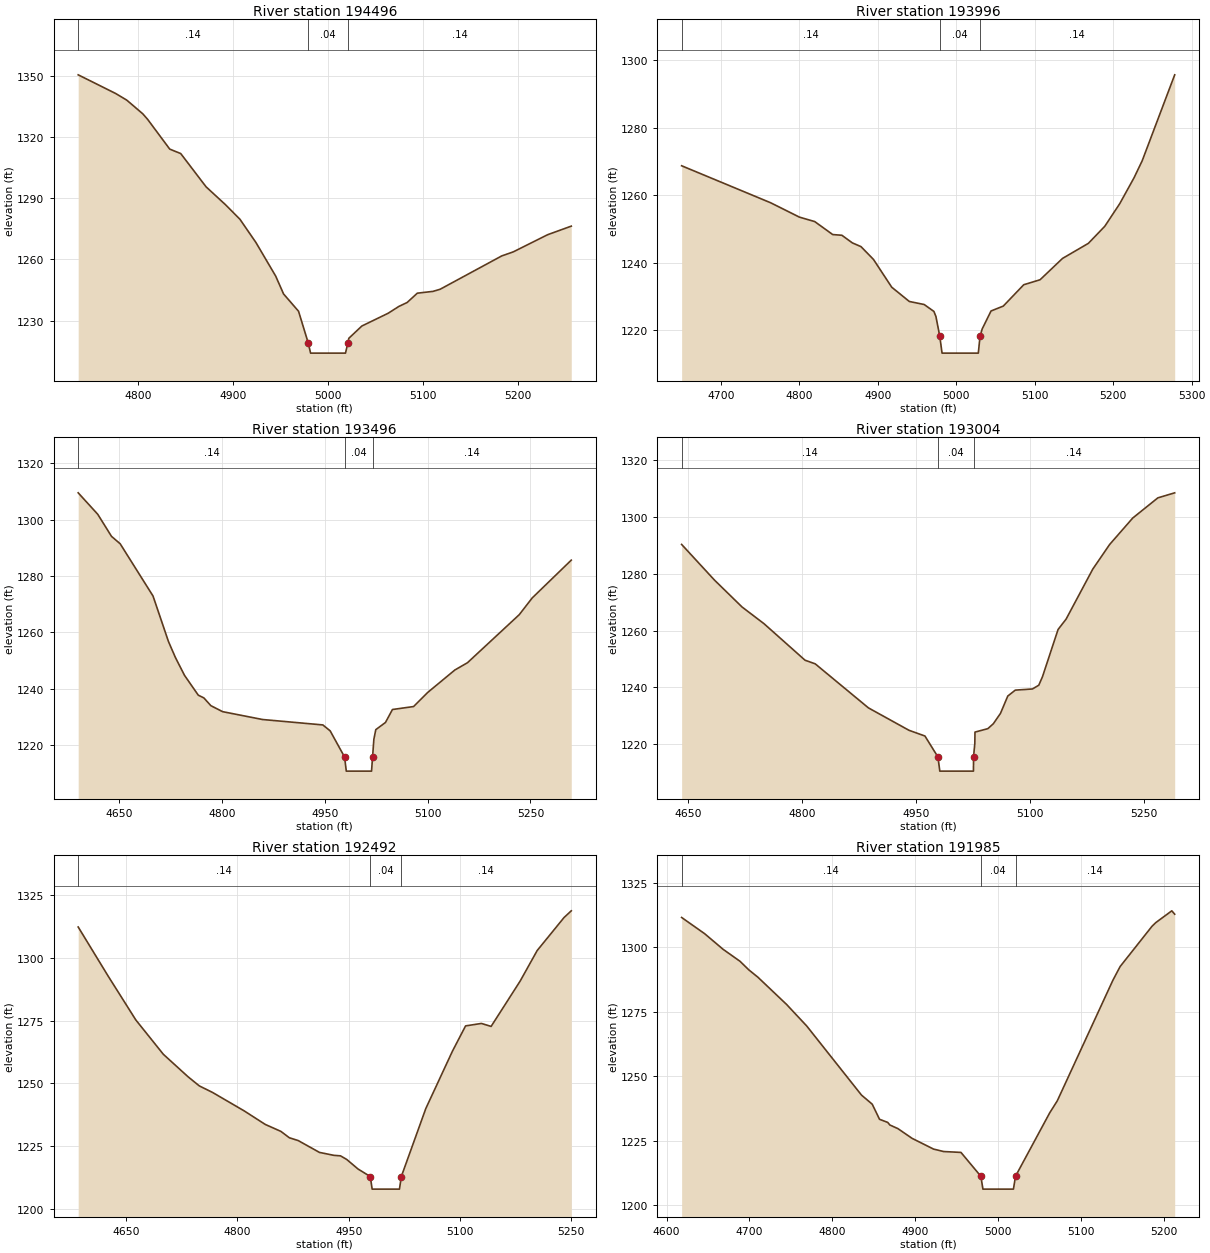
Type RM Length L Ch R = 1,194496,500,500,500
BEGIN DESCRIPTION:
Fisher River 389.0
END DESCRIPTION:
XS GIS Cut Line= 4
      1458488.40      1004048.11      1458286.02      1004071.47
      1458177.04      1004110.39      1457994.11      1004192.12
#Sta/Elev= 30
  4736.6 1350.44  4776.1 1341.29  4787.8 1338.04  4804.6 1331.37  4809.7 1328.68
  4833.1 1314.04  4844.7 1311.85  4871.4 1295.56  4892.0 1286.73  4907.1 1279.66
  4924.0 1268.24  4944.8 1251.80  4953.1 1243.05  4968.9 1234.57  4979.1 1219.04
  4981.6 1214.04  5018.4 1214.04  5020.9 1219.04  5021.9 1221.30  5035.6 1227.32
  5063.4 1233.59  5074.6 1236.91  5083.4 1238.86  5094.1 1243.42  5110.7 1244.31
  5118.2 1245.35  5183.1 1261.68  5195.3 1263.67  5231.5 1272.08  5256.4 1276.28
#Mann=3,-1,0
  4736.6    0.14       0  4979.1    0.04       0  5020.9    0.14       0
Bank Sta=4979.1,5020.9
XS Rating Curve= 0
Exp/Cntr=0.3,0.1

Type RM Length L Ch R = 1,193996,500,500,500
BEGIN DESCRIPTION:
Fisher River 388.0
END DESCRIPTION:
XS GIS Cut Line= 4
      1458402.81      1003631.67      1458142.01      1003631.67
      1457966.88      1003631.67      1457787.83      1003701.74
#Sta/Elev= 30
  4650.2 1268.75  4763.4 1257.79  4800.2 1253.51  4819.8 1252.18  4842.7 1248.33
  4854.4 1248.12  4867.6 1245.87  4878.7 1244.75  4894.6 1240.96  4917.9 1232.70
  4940.3 1228.47  4959.2 1227.57  4971.6 1225.52  4974.2 1224.01  4979.1 1218.14
  4982.0 1213.14  5028.2 1213.14  5030.4 1218.14  5033.1 1220.30  5044.4 1225.65
  5060.0 1227.10  5086.1 1233.44  5106.9 1234.92  5135.5 1241.25  5168.4 1245.72
  5189.3 1250.78  5208.4 1257.50  5226.7 1265.23  5237.0 1270.24  5278.4 1295.74
#Mann=3,-1,0
  4650.2    0.14       0  4979.1    0.04       0  5030.4    0.14       0
Bank Sta=4979.1,5030.4
XS Rating Curve= 0
Exp/Cntr=0.3,0.1

Type RM Length L Ch R = 1,193496,492,492,492
BEGIN DESCRIPTION:
Fisher River 387.0
END DESCRIPTION:
XS GIS Cut Line= 4
      1458558.45      1003131.56      1458204.29      1003174.37
      1458110.88      1003162.69      1457869.61      1003045.95
#Sta/Elev= 30
  4590.7 1309.53  4619.2 1301.92  4639.3 1294.08  4651.9 1291.46  4699.8 1272.93
  4722.3 1256.79  4732.6 1251.03  4745.7 1244.79  4765.8 1237.74  4773.9 1236.78
  4784.1 1234.03  4801.2 1231.90  4859.5 1229.11  4947.4 1227.19  4958.1 1225.08
  4979.1 1215.80  4981.6 1210.80  5018.4 1210.80  5019.9 1215.80  5021.8 1222.10
  5024.6 1225.51  5038.7 1228.06  5048.9 1232.66  5079.7 1233.71  5100.1 1238.67
  5139.9 1246.68  5158.3 1249.26  5233.8 1266.31  5252.7 1272.25  5309.6 1285.65
#Mann=3,-1,0
  4590.7    0.14       0  4979.1    0.04       0  5019.9    0.14       0
Bank Sta=4979.1,5019.9
XS Rating Curve= 0
Exp/Cntr=0.3,0.1

Type RM Length L Ch R = 1,193004,512,512,512
BEGIN DESCRIPTION:
Fisher River 386.0
END DESCRIPTION:
XS GIS Cut Line= 4
      1458679.13      1002820.21      1458375.53      1002730.69
      1458282.12      1002691.77      1458071.96      1002594.47
#Sta/Elev= 30
  4641.6 1290.39  4684.7 1277.87  4721.2 1268.34  4750.1 1262.46  4804.1 1249.60
  4817.5 1248.32  4887.6 1232.80  4940.9 1224.92  4962.0 1222.89  4979.1 1215.52
  4981.6 1210.52  5025.9 1210.52  5026.0 1215.52  5027.7 1220.34  5027.9 1224.27
  5044.8 1225.48  5052.1 1227.22  5061.5 1230.88  5071.1 1236.97  5081.0 1239.06
  5103.5 1239.46  5111.9 1240.78  5116.8 1243.79  5137.3 1260.41  5147.9 1264.08
  5183.0 1281.68  5205.2 1290.36  5235.7 1299.70  5268.7 1306.79  5290.9 1308.57
#Mann=3,-1,0
  4641.6    0.14       0  4979.1    0.04       0  5026.0    0.14       0
Bank Sta=4979.1,5026
XS Rating Curve= 0
Exp/Cntr=0.3,0.1

Type RM Length L Ch R = 1,192492,507,507,507
BEGIN DESCRIPTION:
Fisher River 385.0
END DESCRIPTION:
XS GIS Cut Line= 4
      1458900.93      1002454.34      1458605.16      1002275.33
      1458492.39      1002227.06      1458325.03      1002125.02
#Sta/Elev= 30
  4585.5 1312.24  4625.6 1292.82  4663.2 1275.22  4700.2 1261.57  4733.4 1252.65
  4748.7 1248.98  4766.6 1246.36  4809.3 1239.01  4837.5 1233.65  4858.7 1230.86
  4870.0 1228.33  4882.0 1227.21  4910.6 1222.50  4930.1 1221.33  4939.0 1221.13
  4947.4 1219.68  4962.5 1215.91  4979.1 1212.88  4981.6 1207.88  5018.4 1207.88
  5020.9 1212.88  5053.9 1239.96  5089.8 1262.81  5107.5 1272.87  5128.9 1273.84
  5141.9 1272.66  5181.0 1290.69  5204.0 1302.88  5240.1 1315.98  5249.9 1318.68
#Mann=3,-1,0
  4585.5    0.14       0  4979.1    0.04       0  5020.9    0.14       0
Bank Sta=4979.1,5020.9
XS Rating Curve= 0
Exp/Cntr=0.3,0.1

Type RM Length L Ch R = 1,191985,563,563,563
BEGIN DESCRIPTION:
Fisher River 384.0
END DESCRIPTION:
XS GIS Cut Line= 4
      1459130.55      1002162.43      1458963.22      1001932.83
      1458827.00      1001839.43      1458686.87      1001800.50
#Sta/Elev= 30
  4618.2 1311.57  4645.9 1305.29  4668.2 1299.22  4688.6 1294.57  4699.2 1291.25
  4710.2 1288.38  4744.8 1277.81  4769.0 1269.48  4835.1 1242.65  4848.1 1239.09
  4856.9 1233.24  4866.8 1232.02  4869.3 1231.03  4879.0 1229.63  4896.2 1225.83
  4922.0 1221.68  4934.2 1220.72  4955.1 1220.38  4979.1 1211.13  4981.6 1206.13
  5018.4 1206.13  5020.9 1211.13  5062.1 1235.71  5071.3 1240.41  5138.4 1287.23
  5147.1 1292.53  5185.5 1308.14  5190.1 1309.58  5209.4 1314.15  5212.9 1312.84
#Mann=3,-1,0
  4618.2    0.14       0  4979.1    0.04       0  5020.9    0.14       0
Bank Sta=4979.1,5020.9
XS Rating Curve= 0
Exp/Cntr=0.5,0.3