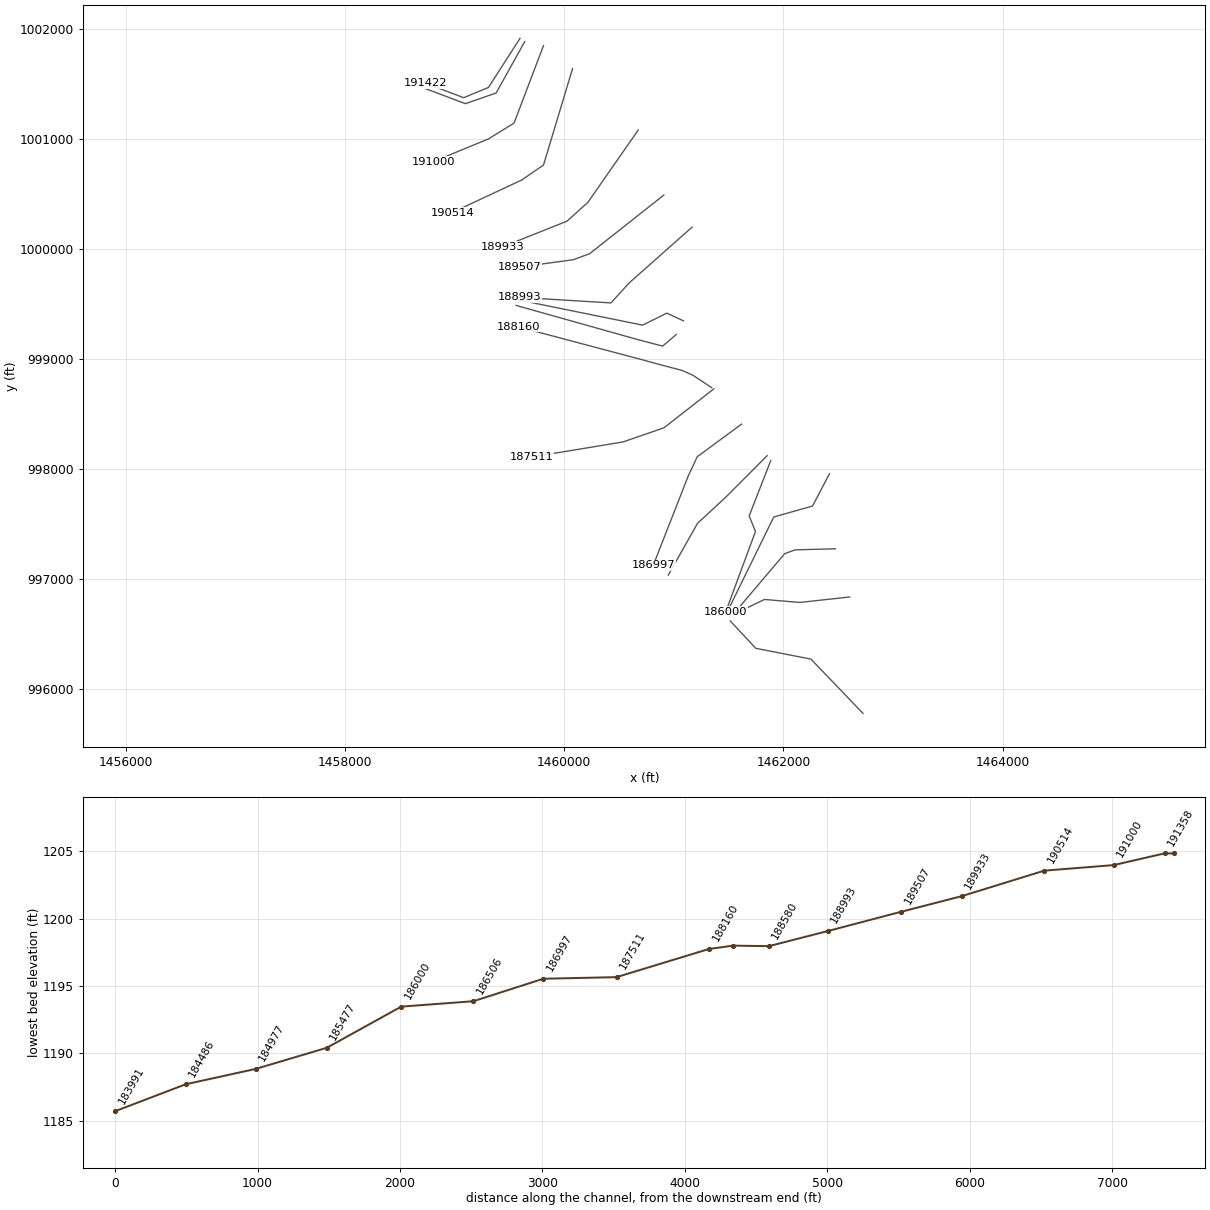
HEC-RAS study Fisher River.prj: Fisher River Limited Detail Study

--- Fisher River.g01 (geometry) --- (continued)

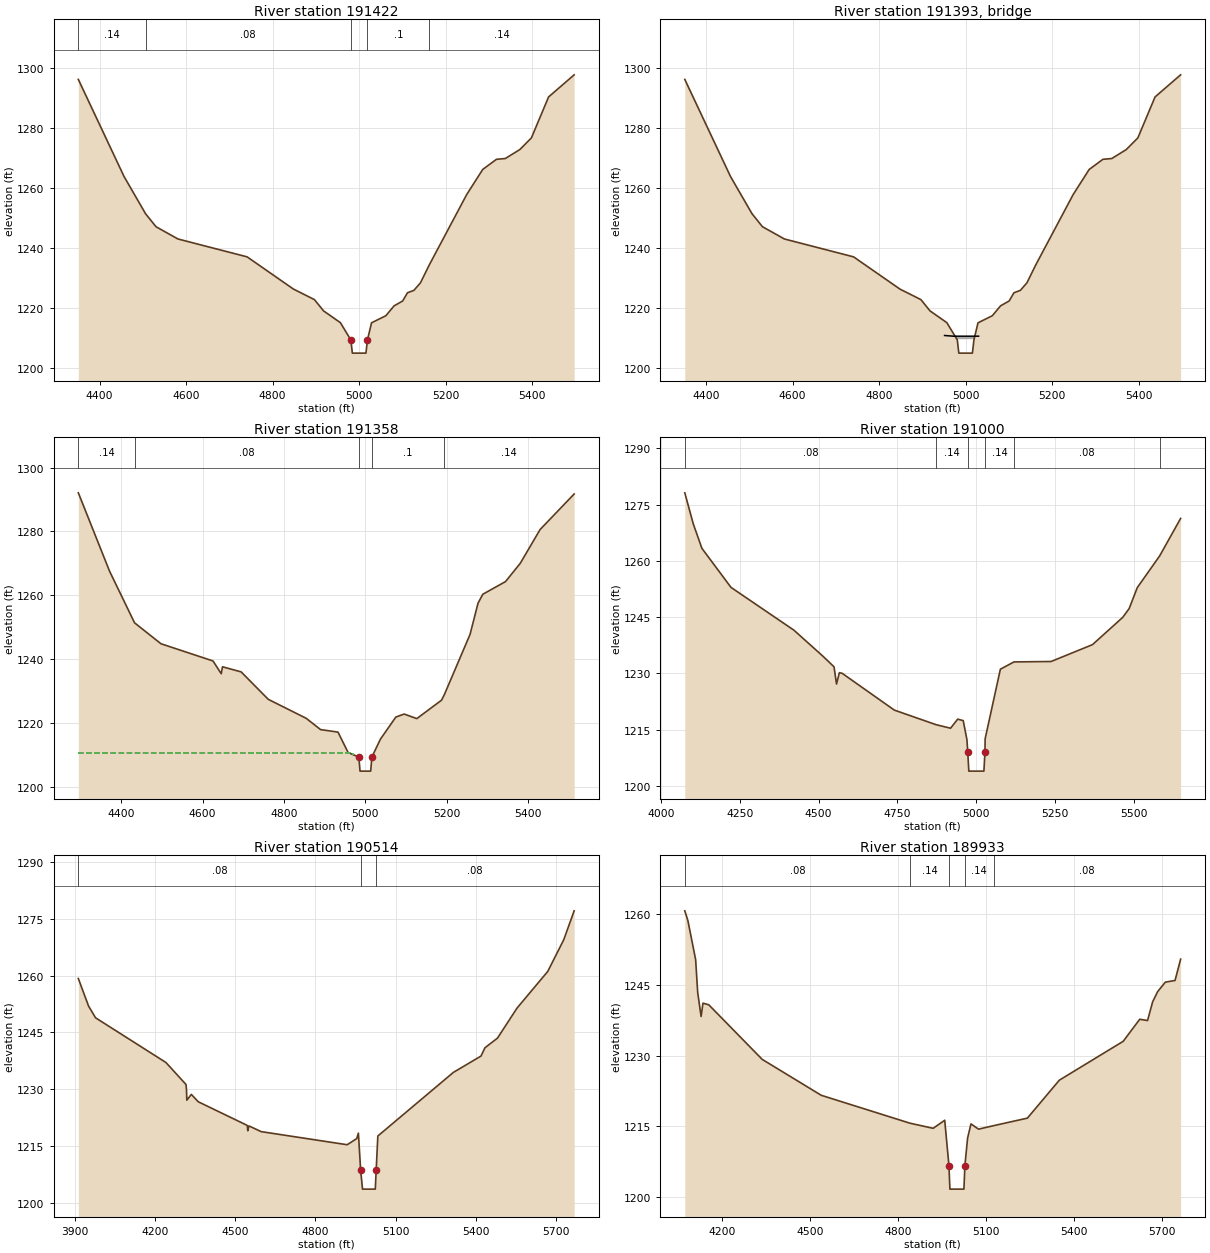
Type RM Length L Ch R = 1,191422,64,64,64
BEGIN DESCRIPTION:
Wahissa Tr - US
END DESCRIPTION:
XS GIS Cut Line= 4
      1459597.61      1001913.38      1459309.60      1001466.97
      1459083.87      1001373.56      1458737.52      1001504.70
#Sta/Elev= 30
  4351.0 1296.18  4456.7 1263.77  4506.4 1251.36  4530.5 1247.03  4581.2 1242.94
  4741.1 1236.97  4848.3 1226.21  4896.6 1222.71  4917.8 1218.94  4956.6 1215.02
  4980.8 1209.25  4984.3 1204.85  5015.7 1204.85  5019.2 1209.25  5028.6 1214.96
  5061.7 1217.33  5080.8 1220.63  5100.6 1222.25  5111.7 1224.99  5126.6 1225.80
  5141.7 1228.31  5162.0 1234.26  5248.6 1257.77  5285.6 1266.14  5317.3 1269.52
  5337.7 1269.78  5371.3 1272.77  5398.1 1276.67  5437.8 1290.33  5496.9 1297.71
#Mann=5,-1,0
  4351.0    0.14       0  4506.4    0.08       0  4980.8    0.04       0
  5019.2     0.1       0  5162.0    0.14       0
#XS Ineff=2,0
    0.00 4970.00 1211.50 5030.00    0.00 1211.50
Permanent Ineff=
       F       F
Bank Sta=4980.8,5019.2
XS Rating Curve= 0
Exp/Cntr=0.5,0.3

Type RM Length L Ch R =3,191393,,,
BEGIN DESCRIPTION:
Wahissa Tr - TOR
Structure ID: LDS_FR_17
Approximate Survey Structure
END DESCRIPTION:
Bridge Culvert--1,0,-1,-1,0
Deck Dist Width WeirC Skew NumUp NumDn MinLoCord MaxHiCord MaxSubmerge Is_Ogee
24,10,3,,7,7,,,0.95,0,1,1,,,
  4951.3  4972.1  4980.0  4980.0  5020.0  5020.0  5030.0
 1210.73 1210.50 1210.50 1210.50 1210.50 1210.50 1210.50
 1184.85 1184.85 1184.85 1209.50 1209.50 1184.85 1184.85
  4951.3  4972.1  4980.0  4980.0  5020.0  5020.0  5030.0
 1210.73 1210.50 1210.50 1210.50 1210.50 1210.50 1210.50
 1184.85 1184.85 1184.85 1209.50 1209.50 1184.85 1184.85
BR Coef=1,1,0,1.25,0,,,0.8,0,2,0,
WSPro=,,,, 1 ,,,, 0 ,,,, 0 ,,,,-1 ,-1 ,-1 , 0 , 0 , 0 , 0 , 0
BC Design=,,0,,0,,,,,,

Type RM Length L Ch R = 1,191358,358,358,358
BEGIN DESCRIPTION:
Wahissa Tr - DS
END DESCRIPTION:
XS GIS Cut Line= 4
      1459640.43      1001883.43      1459379.66      1001416.37
      1459099.44      1001319.07      1458737.57      1001455.26
#Sta/Elev= 30
  4294.8 1292.08  4371.5 1267.53  4433.0 1251.33  4497.9 1244.77  4625.7 1239.38
  4645.9 1235.38  4649.0 1237.55  4694.8 1235.96  4761.3 1227.37  4855.0 1221.38
  4889.9 1217.87  4932.8 1217.08  4957.6 1210.68  4984.0 1209.25  4986.9 1204.85
  5013.1 1204.85  5016.0 1209.25  5037.2 1214.91  5074.9 1221.80  5095.4 1222.74
  5126.4 1221.31  5187.2 1227.09  5194.3 1228.89  5257.2 1247.70  5276.9 1257.52
  5288.7 1260.30  5344.3 1264.25  5380.6 1269.99  5429.3 1280.57  5513.0 1291.72
#Mann=5,-1,0
  4294.8    0.14       0  4433.0    0.08       0  4984.0    0.04       0
  5016.0     0.1       0  5194.3    0.14       0
#XS Ineff=2,0
    0.00 4970.00 1210.53 5030.00    0.00 1210.43
Permanent Ineff=
       F       F
Bank Sta=4984,5016
XS Rating Curve= 0
Exp/Cntr=0.5,0.3

Type RM Length L Ch R = 1,191000,486,486,486
BEGIN DESCRIPTION:
Fisher River 382.0
END DESCRIPTION:
XS GIS Cut Line= 4
      1459811.66      1001847.19      1459543.12      1001142.77
      1459309.60      1000998.76      1458807.55      1000792.49
#Sta/Elev= 30
  4076.2 1278.11  4103.0 1269.86  4130.3 1263.34  4222.5 1252.93  4422.0 1241.52
  4514.4 1234.55  4549.0 1231.77  4556.9 1227.18  4566.0 1230.20  4574.9 1230.03
  4740.2 1220.23  4872.4 1216.35  4918.3 1215.41  4940.9 1217.83  4958.4 1217.43
  4970.2 1212.32  4972.8 1208.98  4976.1 1203.98  5023.9 1203.98  5027.2 1208.98
  5027.8 1212.58  5076.1 1231.13  5119.3 1233.07  5236.7 1233.18  5367.9 1237.67
  5463.8 1244.94  5484.2 1247.29  5509.8 1252.85  5580.8 1261.31  5647.2 1271.29
#Mann=6,-1,0
  4076.2    0.08       0  4872.4    0.14       0  4972.8    0.04       0
  5027.2    0.14       0  5119.3    0.08       0  5580.8    0.14       0
Bank Sta=4972.8,5027.2
XS Rating Curve= 0
Exp/Cntr=0.3,0.1

Type RM Length L Ch R = 1,190514,581,581,581
BEGIN DESCRIPTION:
Fisher River 381.0
END DESCRIPTION:
XS GIS Cut Line= 4
      1460076.31      1001637.01      1459811.66      1000761.35
      1459613.17      1000625.14      1458978.75      1000329.33
#Sta/Elev= 30
  3912.6 1259.22  3950.8 1251.96  3977.0 1248.84  4240.4 1237.03  4315.6 1231.21
  4317.5 1229.66  4318.6 1227.07  4335.5 1228.60  4361.4 1226.65  4542.2 1220.49
  4545.1 1220.33  4546.6 1219.00  4551.0 1220.27  4596.9 1218.76  4918.7 1215.30
  4954.4 1216.92  4960.7 1218.36  4969.1 1208.57  4976.1 1203.57  5023.9 1203.57
  5027.2 1208.57  5033.4 1217.60  5315.9 1234.40  5419.5 1238.73  5434.2 1240.91
  5481.2 1243.47  5554.2 1251.39  5669.4 1261.10  5729.2 1269.47  5768.1 1277.10
#Mann=3,-1,0
  3912.6    0.08       0  4969.1    0.04       0  5027.2    0.08       0
Bank Sta=4969.1,5027.2
XS Rating Curve= 0
Exp/Cntr=0.3,0.1

Type RM Length L Ch R = 1,189933,426,426,426
BEGIN DESCRIPTION:
Fisher River 380.0
END DESCRIPTION:
XS GIS Cut Line= 4
      1460675.69      1001079.74      1460216.43      1000421.98
      1460025.72      1000250.73      1459438.05      1000017.22
#Sta/Elev= 30
  4072.0 1260.75  4082.5 1258.69  4109.0 1250.39  4115.9 1243.46  4127.6 1238.33
  4134.0 1241.15  4153.8 1240.80  4335.9 1229.22  4537.3 1221.59  4839.7 1215.67
  4919.0 1214.58  4958.4 1216.29  4972.8 1206.67  4976.1 1201.67  5023.9 1201.67
  5027.2 1206.67  5036.4 1212.50  5047.9 1215.52  5073.7 1214.40  5125.7 1215.15
  5240.3 1216.74  5349.1 1224.79  5567.1 1233.05  5623.4 1237.73  5650.1 1237.46
  5667.5 1241.43  5684.6 1243.60  5710.8 1245.61  5743.9 1245.97  5762.9 1250.49
#Mann=5,-1,0
  4072.0    0.08       0  4839.7    0.14       0  4972.8    0.04       0
  5027.2    0.14       0  5125.7    0.08       0
Bank Sta=4972.8,5027.2
XS Rating Curve= 0
Exp/Cntr=0.3,0.1

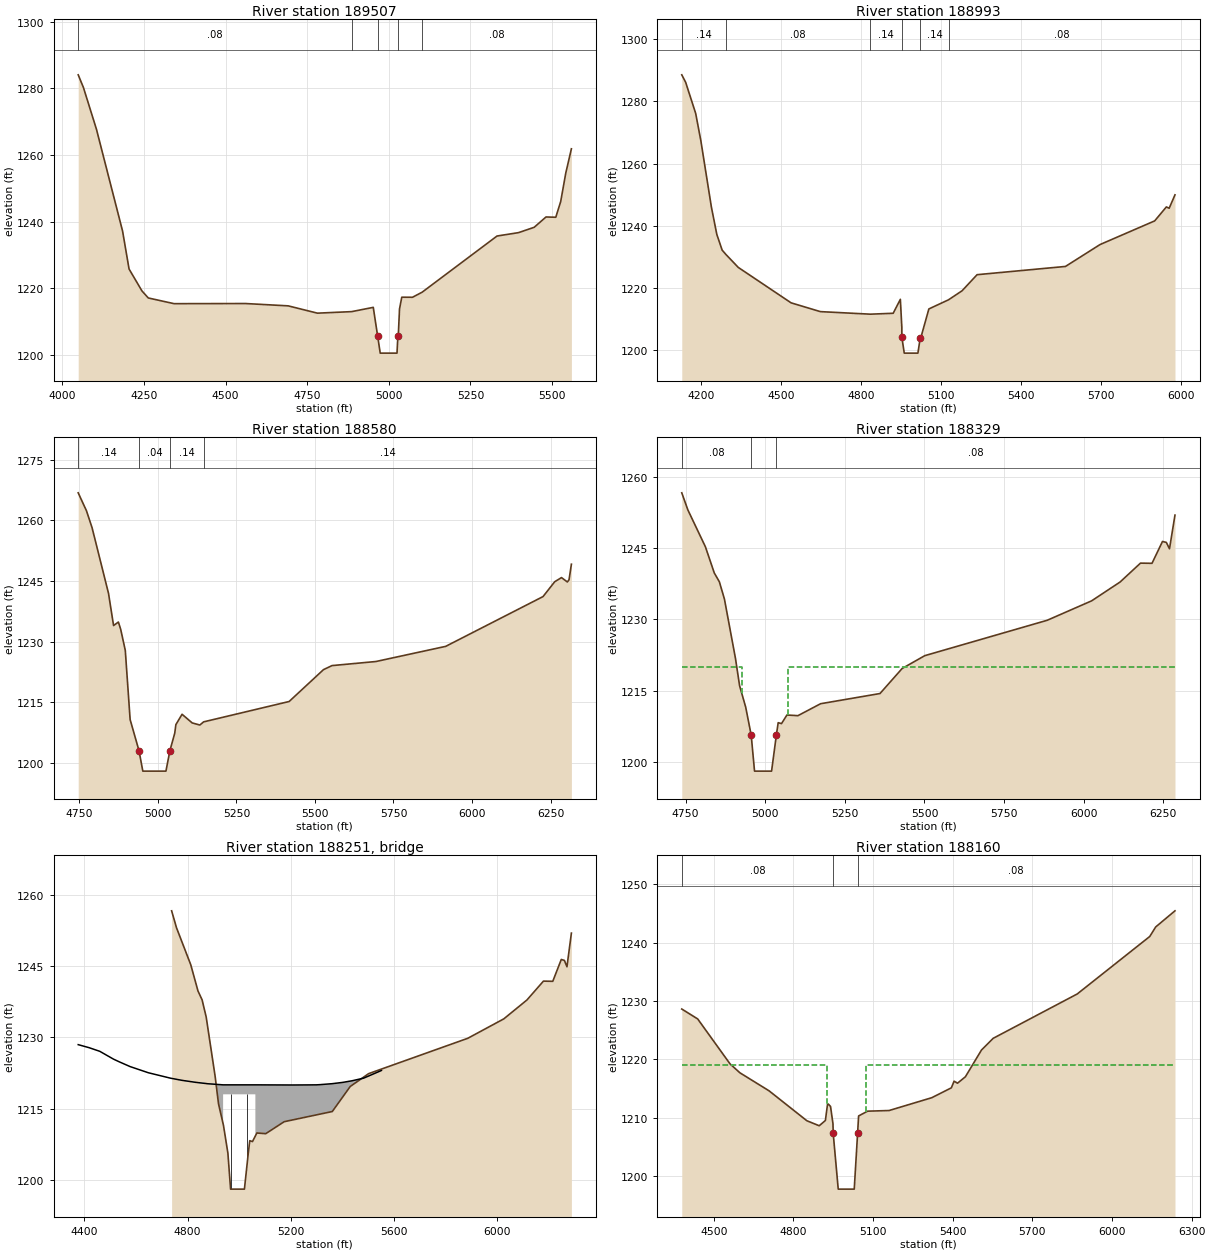
Type RM Length L Ch R = 1,189507,514,514,514
BEGIN DESCRIPTION:
Fisher River 379.0
END DESCRIPTION:
XS GIS Cut Line= 4
      1460909.22      1000488.15      1460232.00       999954.94
      1460084.10       999900.45      1459597.63       999834.29
#Sta/Elev= 30
  4048.8 1284.07  4064.8 1280.27  4104.7 1267.73  4184.7 1237.16  4204.6 1225.76
  4244.1 1219.18  4263.5 1217.07  4342.4 1215.36  4561.3 1215.40  4692.0 1214.70
  4781.5 1212.51  4886.4 1212.97  4952.5 1214.25  4966.1 1205.51  4973.8 1200.51
  5025.2 1200.51  5027.8 1205.51  5029.0 1205.55  5032.9 1213.78  5039.8 1217.30
  5072.7 1217.28  5102.4 1218.82  5331.5 1235.67  5397.5 1236.69  5445.3 1238.29
  5481.5 1241.39  5511.5 1241.31  5526.6 1246.06  5542.0 1254.54  5559.3 1261.86
#Mann=5,-1,0
  4048.8    0.08       0  4886.4    0.14       0  4966.1    0.04       0
  5027.8    0.14       0  5102.4    0.08       0
Bank Sta=4966.1,5027.8
XS Rating Curve= 0
Exp/Cntr=0.3,0.1

Type RM Length L Ch R = 1,188993,413,413,413
BEGIN DESCRIPTION:
Fisher River 378.0
END DESCRIPTION:
XS GIS Cut Line= 4
      1461166.05      1000196.23      1460593.95       999690.29
      1460426.59       999507.36      1459589.77       999557.96
#Sta/Elev= 30
  4128.3 1288.53  4142.8 1286.14  4180.4 1276.15  4199.8 1267.38  4239.4 1246.02
  4259.7 1237.25  4279.8 1232.18  4294.1 1230.77  4340.2 1226.63  4538.4 1215.24
  4648.2 1212.42  4835.9 1211.60  4921.3 1211.89  4948.2 1216.37  4953.7 1207.42
  4953.9 1204.18  4962.8 1199.08  5014.0 1199.08  5023.0 1204.08  5025.1 1204.08
  5055.1 1213.28  5128.9 1216.22  5179.8 1219.13  5236.0 1224.29  5567.5 1226.94
  5697.3 1233.98  5902.1 1241.58  5946.0 1246.07  5956.6 1245.66  5978.3 1249.95
#Mann=6,-1,0
  4128.3    0.14       0  4294.1    0.08       0  4835.9    0.14       0
  4953.9   0.042       0  5023.0    0.14       0  5128.9    0.08       0
Bank Sta=4953.9,5023
XS Rating Curve= 0
Exp/Cntr=0.3,0.1

Type RM Length L Ch R = 1,188580,251,251,251
BEGIN DESCRIPTION:
Fisher River 377.0
END DESCRIPTION:
XS GIS Cut Line= 4
      1461088.20       999344.30      1460936.44       999414.35
      1460714.60       999305.37      1459582.05       999535.00
#Sta/Elev= 30
  4746.5 1266.84  4772.7 1262.42  4790.5 1258.25  4843.0 1241.96  4859.1 1233.99
  4874.4 1234.86  4881.8 1233.05  4896.4 1227.84  4911.8 1210.73  4940.2 1202.96
  4952.2 1197.96  5025.8 1197.96  5038.2 1202.96  5053.8 1207.35  5057.4 1209.47
  5077.1 1212.03  5109.4 1209.89  5133.7 1209.37  5145.7 1210.15  5417.9 1215.19
  5527.3 1223.08  5554.5 1224.08  5694.3 1225.09  5916.3 1228.84  6226.1 1241.16
  6263.2 1244.83  6284.8 1245.86  6303.5 1244.78  6308.9 1245.33  6316.4 1249.17
#Mann=4,-1,0
  4746.5    0.14       0  4940.2    0.04       0  5038.2    0.14       0
  5145.7    0.14       0
Bank Sta=4940.2,5038.2
XS Rating Curve= 0
Exp/Cntr=0.5,0.3

Type RM Length L Ch R = 1,188329,169,169,169
BEGIN DESCRIPTION:
Ladonia Church Rd - US
END DESCRIPTION:
XS GIS Cut Line= 4
      1461022.10       999219.78      1460897.52       999114.67
      1460660.11       999176.94      1459562.61       999484.39
#Sta/Elev= 30
  4738.1 1256.71  4757.0 1253.14  4812.2 1245.34  4840.2 1239.80  4856.1 1237.94
  4872.0 1234.30  4906.6 1221.80  4919.6 1216.01  4938.8 1211.48  4956.0 1205.60
  4966.5 1198.00  5020.0 1198.00  5035.0 1205.60  5040.7 1208.22  5051.2 1208.03
  5068.2 1209.84  5102.7 1209.70  5173.9 1212.22  5360.3 1214.37  5429.8 1219.65
  5501.0 1222.36  5885.1 1229.82  6024.6 1233.92  6114.1 1237.90  6178.0 1241.88
  6214.2 1241.84  6247.1 1246.45  6259.2 1246.25  6269.1 1244.91  6286.3 1252.01
#Mann=3,-1,0
  4738.1    0.08       0  4956.0    0.04       0  5035.0    0.08       0
#XS Ineff=2,0
    0.00 4927.50 1220.00 5072.50    0.00 1220.00
Permanent Ineff=
       F       F
Bank Sta=4956,5035
XS Rating Curve= 0
Exp/Cntr=0.5,0.3

Type RM Length L Ch R =3,188251,,,
BEGIN DESCRIPTION:
Ladonia Church Rd - TOR
Structure ID: LDS_FR_16
Approximate Survey Structure
END DESCRIPTION:
Bridge Culvert--1,0,-1,-1,0
Deck Dist Width WeirC Skew NumUp NumDn MinLoCord MaxHiCord MaxSubmerge Is_Ogee
63,30,3,,23,23,,,0.95,0,1,1,,,
  4376.3  4419.1  4459.9  4513.1  4535.1  4577.4  4648.0  4734.3  4778.3  4829.6
  4878.7  4937.5  4937.5  5062.5  5062.5  5206.0  5298.7  5314.2  5358.6  5399.7
  5436.0  5481.6  5550.7
 1228.48 1227.83 1227.07 1225.42 1224.86 1223.85 1222.55 1221.40 1220.95 1220.54
 1220.23 1220.00 1220.00 1220.00 1220.00 1219.97 1220.00 1220.05 1220.24 1220.51
 1220.85 1221.41 1223.03
 1178.00 1178.00 1178.00 1178.00 1178.00 1178.00 1178.00 1178.00 1178.00 1178.00
 1178.00 1178.00 1218.00 1218.00 1178.00 1178.00 1178.00 1178.00 1178.00 1178.00
 1178.00 1178.00 1178.00
  4376.3  4419.1  4459.9  4513.1  4535.1  4577.4  4648.0  4734.3  4778.3  4829.6
  4878.7  4937.5  4937.5  5062.5  5062.5  5206.0  5298.7  5314.2  5358.6  5399.7
  5436.0  5481.6  5550.7
 1228.48 1227.83 1227.07 1225.42 1224.86 1223.85 1222.55 1221.40 1220.95 1220.54
 1220.23 1220.00 1220.00 1220.00 1220.00 1219.97 1220.00 1220.05 1220.24 1220.51
 1220.85 1221.41 1223.03
 1178.00 1178.00 1178.00 1178.00 1178.00 1178.00 1178.00 1178.00 1178.00 1178.00
 1178.00 1178.00 1218.00 1218.00 1178.00 1178.00 1178.00 1178.00 1178.00 1178.00
 1178.00 1178.00 1178.00
Pier Skew, UpSta & Num, DnSta & Num=,4968.8,2,4968.8,2,0,0,0,0,0
       1       1
 1210.65 1218.00
       1       1
 1210.40 1218.00
Pier Skew, UpSta & Num, DnSta & Num=,5031.3,2,5031.3,2,0,0,0,0,0
       1       1
 1210.75 1218.00
       1       1
 1210.50 1218.00
Abutment Skew #Up #Dn=,2,2
  4937.5  4957.5
 1218.00 1203.29
  4937.5  4949.9
 1218.00 1205.31
Abutment Skew #Up #Dn=,2,2
  5042.5  5062.5
 1208.19 1218.00
  5042.5  5062.5
 1208.69 1218.00
BR Coef=1,1,0,1.25,0,,,0.8,0,2,0,
WSPro=,,,, 1 ,,,, 0 ,,,, 0 ,,,,-1 ,-1 ,-1 , 0 , 0 , 0 , 0 , 0
BC Design=,,0,,0,,,,,,

Type RM Length L Ch R = 1,188160,649,649,649
BEGIN DESCRIPTION:
Ladonia Church Rd - DS
END DESCRIPTION:
XS GIS Cut Line= 6
      1461345.08       998737.16      1461173.85       998850.01
      1461076.55       998892.82      1460870.28       998947.31
      1460699.03       998994.02      1459582.06       999289.80
#Sta/Elev= 30
  4379.5 1228.64  4439.4 1226.94  4561.1 1219.24  4598.5 1217.70  4708.3 1214.61
  4850.6 1209.48  4897.1 1208.62  4920.4 1209.52  4928.6 1212.35  4931.4 1212.34
  4939.8 1211.93  4949.0 1208.97  4949.8 1207.35  4968.8 1197.75  5029.1 1197.75
  5041.8 1207.35  5045.5 1210.30  5079.5 1211.12  5160.3 1211.23  5321.2 1213.43
  5394.8 1215.12  5405.2 1216.26  5418.2 1215.92  5447.8 1217.02  5508.3 1221.60
  5552.3 1223.61  5869.0 1231.22  6142.2 1241.08  6164.5 1242.71  6237.2 1245.48
#Mann=3,-1,0
  4379.5    0.08       0  4949.8    0.04       0  5041.8    0.08       0
#XS Ineff=2,0
    0.00 4927.50 1219.00 5072.50    0.00 1219.00
Permanent Ineff=
       F       F
Bank Sta=4949.8,5041.8
XS Rating Curve= 0
Exp/Cntr=0.5,0.3

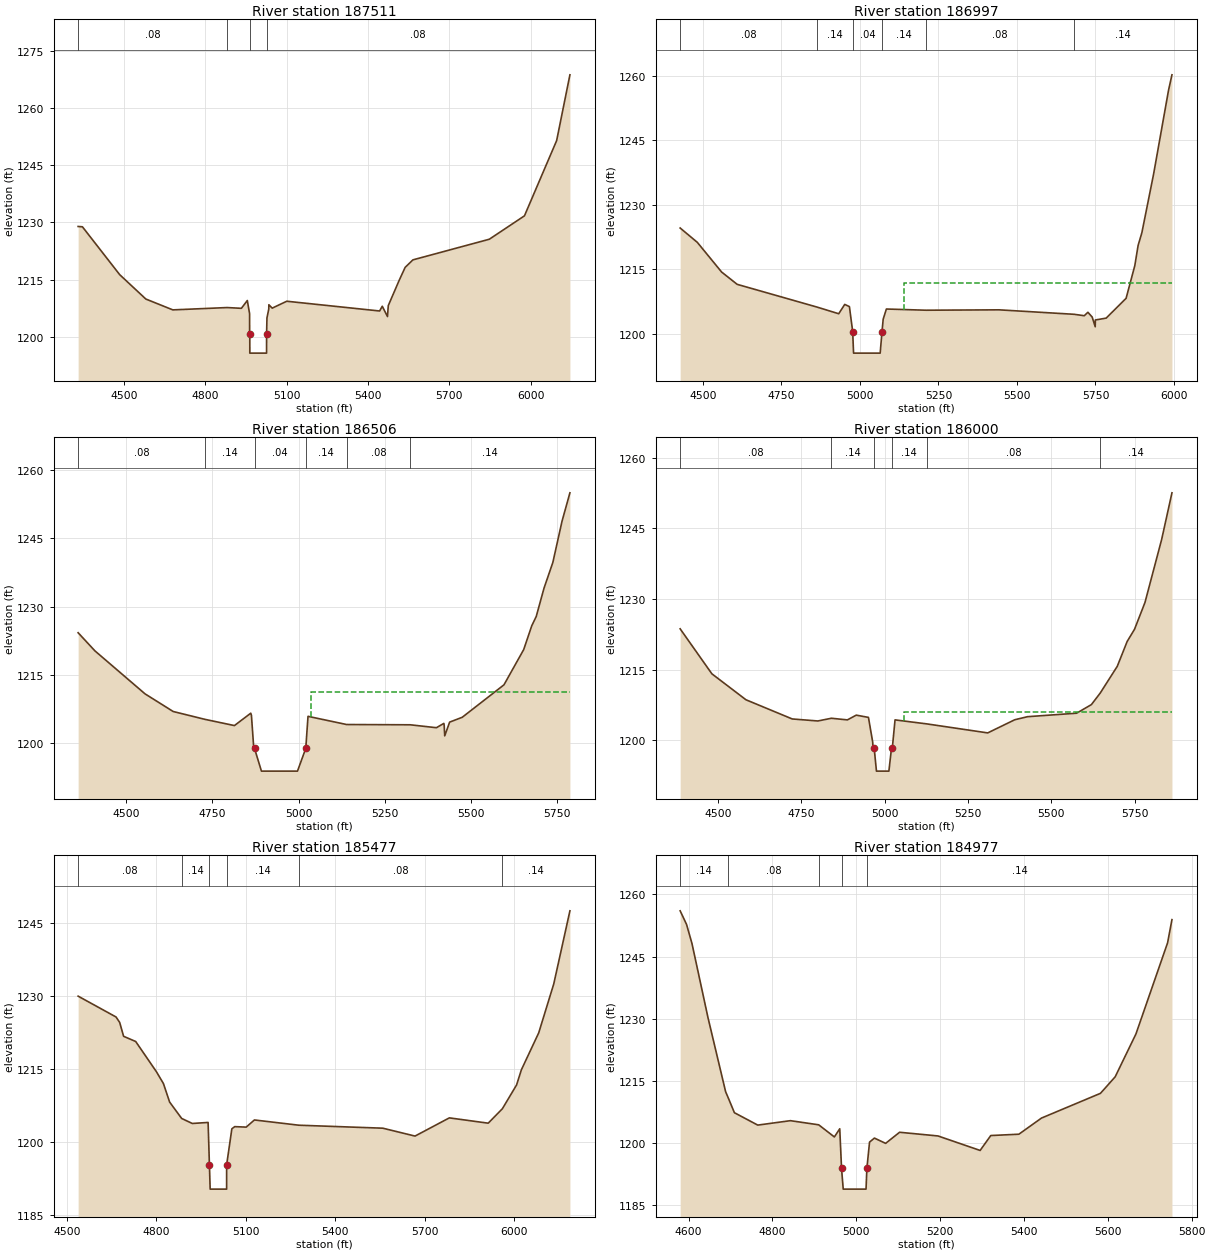
Type RM Length L Ch R = 1,187511,514,514,514
BEGIN DESCRIPTION:
Fisher River 375.0
END DESCRIPTION:
XS GIS Cut Line= 4
      1461364.58       998725.49      1460909.20       998371.30
      1460535.57       998242.87      1459706.58       998106.65
#Sta/Elev= 30
  4332.0 1228.93  4347.8 1228.85  4485.2 1216.27  4581.5 1209.87  4680.9 1207.02
  4881.0 1207.63  4933.6 1207.43  4955.4 1209.48  4963.8 1206.02  4963.9 1200.66
  4964.5 1200.66  4964.6 1195.66  5026.3 1195.66  5026.4 1200.66  5027.8 1204.93
  5034.5 1207.25  5034.8 1208.37  5047.1 1207.48  5100.8 1209.29  5442.8 1206.73
  5452.7 1207.97  5471.9 1205.27  5474.8 1208.14  5514.7 1214.74  5537.0 1218.19
  5565.6 1220.16  5847.1 1225.58  5976.6 1231.73  6095.2 1251.50  6144.1 1268.77
#Mann=4,-1,0
  4332.0    0.08       0  4881.0    0.14       0  4964.5    0.04       0
  5026.4    0.08       0
#XS Ineff=2,0
    0.00 4955.40 1209.48 5100.80    0.00 1209.29
Permanent Ineff=
       F       F
Bank Sta=4964.5,5026.4
XS Rating Curve= 0
Exp/Cntr=0.3,0.1

Type RM Length L Ch R = 1,186997,491,491,491
BEGIN DESCRIPTION:
Fisher River 374.0
END DESCRIPTION:
XS GIS Cut Line= 4
      1461617.40       998405.18      1461213.86       998108.75
      1461131.66       997934.39      1460812.85       997122.41
#Sta/Elev= 30
  4427.7 1224.64  4482.3 1221.31  4559.6 1214.41  4609.2 1211.54  4864.0 1206.24
  4932.5 1204.70  4951.7 1206.87  4966.6 1206.36  4977.0 1200.54  4979.8 1195.54
  5064.5 1195.54  5070.4 1200.54  5074.1 1203.44  5084.3 1205.80  5210.6 1205.52
  5442.8 1205.61  5682.5 1204.57  5714.3 1204.24  5725.9 1205.04  5739.5 1203.93
  5749.2 1201.67  5749.6 1203.25  5784.0 1203.68  5847.5 1208.29  5875.2 1215.88
  5885.7 1220.57  5897.8 1223.57  5934.9 1237.12  5982.7 1256.71  5993.5 1260.27
#Mann=6,-1,0
  4427.7    0.08       0  4864.0    0.14       0  4977.0    0.04       0
  5070.4    0.14       0  5210.6    0.08       0  5682.5    0.14       0
#XS Ineff=2,0
       0                 5141.30    0.00 1211.95
Permanent Ineff=
       F       F
Bank Sta=4977,5070.4
XS Rating Curve= 0
Exp/Cntr=0.3,0.1

Type RM Length L Ch R = 1,186506,506,506,506
BEGIN DESCRIPTION:
Fisher River 373.0
END DESCRIPTION:
XS GIS Cut Line= 4
      1461851.49       998118.68      1461472.91       997740.10
      1461216.35       997503.47      1460949.83       997032.69
#Sta/Elev= 30
  4361.1 1224.28  4409.7 1220.30  4555.0 1210.85  4636.6 1206.97  4729.1 1205.24
  4814.1 1203.88  4861.5 1206.60  4863.4 1206.13  4870.2 1198.87  4872.3 1198.87
  4892.4 1193.87  4996.9 1193.87  5020.9 1198.87  5027.4 1205.91  5139.3 1204.11
  5323.8 1204.05  5399.6 1203.41  5421.1 1204.36  5422.0 1203.96  5423.6 1201.62
  5437.9 1204.64  5474.4 1205.70  5595.3 1212.83  5652.5 1220.57  5675.9 1225.81
  5688.8 1227.84  5711.5 1234.09  5737.0 1239.72  5763.7 1248.81  5786.5 1255.02
#Mann=6,-1,0
  4361.1    0.08       0  4729.1    0.14       0  4872.3    0.04       0
  5020.9    0.14       0  5139.3    0.08       0  5323.8    0.14       0
#XS Ineff=2,0
       0                 5037.40    0.00 1211.18
Permanent Ineff=
       F       F
Bank Sta=4872.3,5020.9
XS Rating Curve= 0
Exp/Cntr=0.3,0.1

Type RM Length L Ch R = 1,186000,523,523,523
BEGIN DESCRIPTION:
Fisher River 372.0
END DESCRIPTION:
XS GIS Cut Line= 4
      1461883.91       998073.91      1461687.12       997570.73
      1461744.41       997428.75      1461472.92       996696.45
#Sta/Elev= 30
  4387.1 1223.66  4482.2 1214.12  4584.4 1208.61  4723.1 1204.54  4799.9 1204.11
  4840.6 1204.69  4888.4 1204.34  4915.1 1205.35  4951.6 1204.87  4964.3 1199.65
  4965.2 1198.47  4968.6 1198.47  4975.6 1193.47  5012.9 1193.47  5020.9 1198.47
  5023.3 1198.47  5031.3 1204.34  5126.8 1203.49  5309.2 1201.58  5390.2 1204.37
  5428.4 1205.02  5575.7 1205.76  5620.1 1207.59  5646.5 1210.04  5697.5 1215.70
  5727.3 1220.99  5749.3 1223.57  5780.6 1229.25  5830.6 1242.62  5861.5 1252.52
#Mann=6,-1,0
  4387.1    0.08       0  4840.6    0.14       0  4968.6    0.04       0
  5020.9    0.14       0  5126.8    0.08       0  5646.5    0.14       0
#XS Ineff=2,0
    0.00 4915.10 1205.35 5058.20    0.00 1206.00
Permanent Ineff=
       F       F
Bank Sta=4968.6,5020.9
XS Rating Curve= 0
Exp/Cntr=0.3,0.1

Type RM Length L Ch R = 1,185477,500,500,500
BEGIN DESCRIPTION:
Fisher River 371.0
END DESCRIPTION:
XS GIS Cut Line= 4
      1462419.45       997954.34      1462265.00       997660.40
      1461911.30       997560.76      1461492.85       996708.91
#Sta/Elev= 30
  4537.9 1230.06  4664.9 1225.78  4677.2 1224.66  4690.3 1221.81  4730.9 1220.74
  4800.7 1214.50  4823.9 1212.09  4844.6 1208.30  4885.0 1204.93  4920.5 1203.90
  4973.6 1204.11  4978.0 1195.41  4980.5 1190.41  5035.7 1190.41  5035.8 1195.41
  5053.2 1202.80  5062.9 1203.25  5101.3 1203.15  5128.8 1204.62  5278.0 1203.54
  5559.2 1202.93  5667.3 1201.31  5782.3 1205.05  5912.6 1203.96  5960.1 1206.93
  6007.7 1211.82  6023.8 1214.93  6081.9 1222.52  6132.3 1232.57  6186.5 1247.59
#Mann=6,-1,0
  4537.9    0.08       0  4885.0    0.14       0  4978.0    0.04       0
  5035.8    0.14       0  5278.0    0.08       0  5960.1    0.14       0
#XS Ineff=2,0
       0                 5128.80    0.00 1204.62
Permanent Ineff=
       F       F
Bank Sta=4978,5035.8
XS Rating Curve= 0
Exp/Cntr=0.3,0.1

Type RM Length L Ch R = 1,184977,491,491,491
BEGIN DESCRIPTION:
Fisher River 370.0
END DESCRIPTION:
XS GIS Cut Line= 4
      1462474.22       997271.82      1462105.59       997261.86
      1462010.93       997226.99      1461555.11       996691.45
#Sta/Elev= 30
  4580.1 1256.04  4595.3 1252.77  4608.3 1248.14  4646.6 1230.19  4688.5 1212.37
  4694.8 1210.87  4709.5 1207.29  4765.2 1204.30  4843.1 1205.37  4910.5 1204.37
  4947.9 1201.44  4960.7 1203.41  4965.0 1193.84  4969.0 1188.84  5023.4 1188.84
  5025.4 1193.84  5031.8 1200.20  5043.4 1201.16  5070.1 1199.89  5103.4 1202.57
  5195.0 1201.68  5295.5 1198.18  5320.9 1201.78  5387.9 1202.10  5441.9 1206.00
  5582.5 1211.97  5617.6 1215.96  5667.1 1226.30  5742.6 1248.32  5753.0 1253.91
#Mann=5,-1,0
  4580.1    0.14       0  4694.8    0.08       0  4910.5    0.14       0
  4965.0    0.04       0  5025.4    0.14       0
#XS Ineff=2,0
       0                 5103.40    0.00 1202.57
Permanent Ineff=
       F       F
Bank Sta=4965,5025.4
XS Rating Curve= 0
Exp/Cntr=0.3,0.1

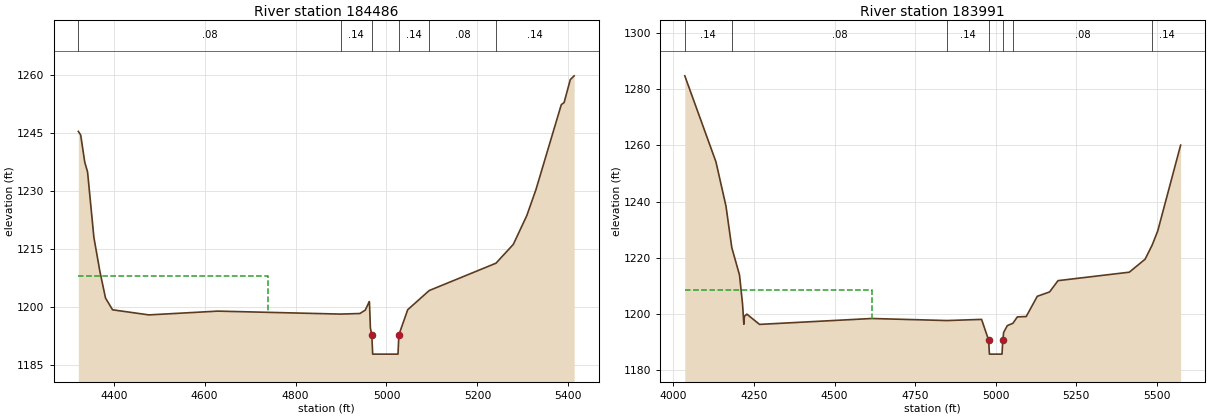
Type RM Length L Ch R = 1,184486,495,495,495
BEGIN DESCRIPTION:
Fisher River 369.0
END DESCRIPTION:
XS GIS Cut Line= 4
      1462603.75       996833.43      1462147.93       996783.62
      1461826.61       996811.01      1461547.66       996676.52
#Sta/Elev= 30
  4322.2 1245.45  4327.4 1244.50  4336.4 1237.42  4342.5 1234.95  4356.4 1217.99
  4369.6 1209.16  4382.0 1202.24  4397.5 1199.19  4477.5 1197.87  4629.3 1198.85
  4899.1 1198.08  4941.5 1198.23  4953.3 1199.10  4962.2 1201.32  4962.6 1201.17
  4964.7 1194.46  4967.8 1192.70  4969.7 1187.70  5025.4 1187.70  5027.3 1192.70
  5046.8 1199.22  5094.1 1204.19  5240.9 1211.27  5279.1 1216.16  5308.7 1223.61
  5328.9 1230.37  5384.6 1252.38  5390.8 1252.93  5404.4 1258.87  5412.9 1259.85
#Mann=6,-1,0
  4322.2    0.08       0  4899.1    0.14       0  4967.8    0.04       0
  5027.3    0.14       0  5094.1    0.08       0  5240.9    0.14       0
#XS Ineff=2,0
    0.00 4740.20 1208.06               0
Permanent Ineff=
       F       F
Bank Sta=4967.8,5027.3
XS Rating Curve= 0
Exp/Cntr=0.3,0.1

Type RM Length L Ch R = 1,183991,384,384,384
BEGIN DESCRIPTION:
Fisher River 368.0
END DESCRIPTION:
XS GIS Cut Line= 4
      1462725.03       995774.96      1462250.06       996268.51
      1461747.90       996366.40      1461514.73       996615.51
#Sta/Elev= 30
  4035.7 1284.74  4132.3 1254.14  4163.4 1238.38  4181.4 1223.64  4205.4 1213.85
  4214.8 1203.53  4218.9 1196.34  4220.3 1199.08  4228.1 1199.94  4267.5 1196.28
  4615.6 1198.38  4849.1 1197.65  4956.2 1198.06  4978.0 1190.70  4980.5 1185.70
  5019.5 1185.70  5022.0 1190.70  5024.6 1193.40  5035.9 1195.84  5053.4 1196.68
  5067.1 1198.95  5094.6 1199.08  5128.9 1206.28  5167.1 1207.83  5193.2 1211.85
  5414.3 1214.86  5463.3 1219.48  5485.4 1224.55  5502.6 1229.58  5573.5 1260.07
#Mann=7,-1,0
  4035.7    0.14       0  4181.4    0.08       0  4849.1    0.14       0
  4978.0    0.04       0  5022.0    0.14       0  5053.4    0.08       0
  5485.4    0.14       0
#XS Ineff=2,0
    0.00 4616.10 1208.69               0
Permanent Ineff=
       F       F
Bank Sta=4978,5022
XS Rating Curve= 0
Exp/Cntr=0.3,0.1