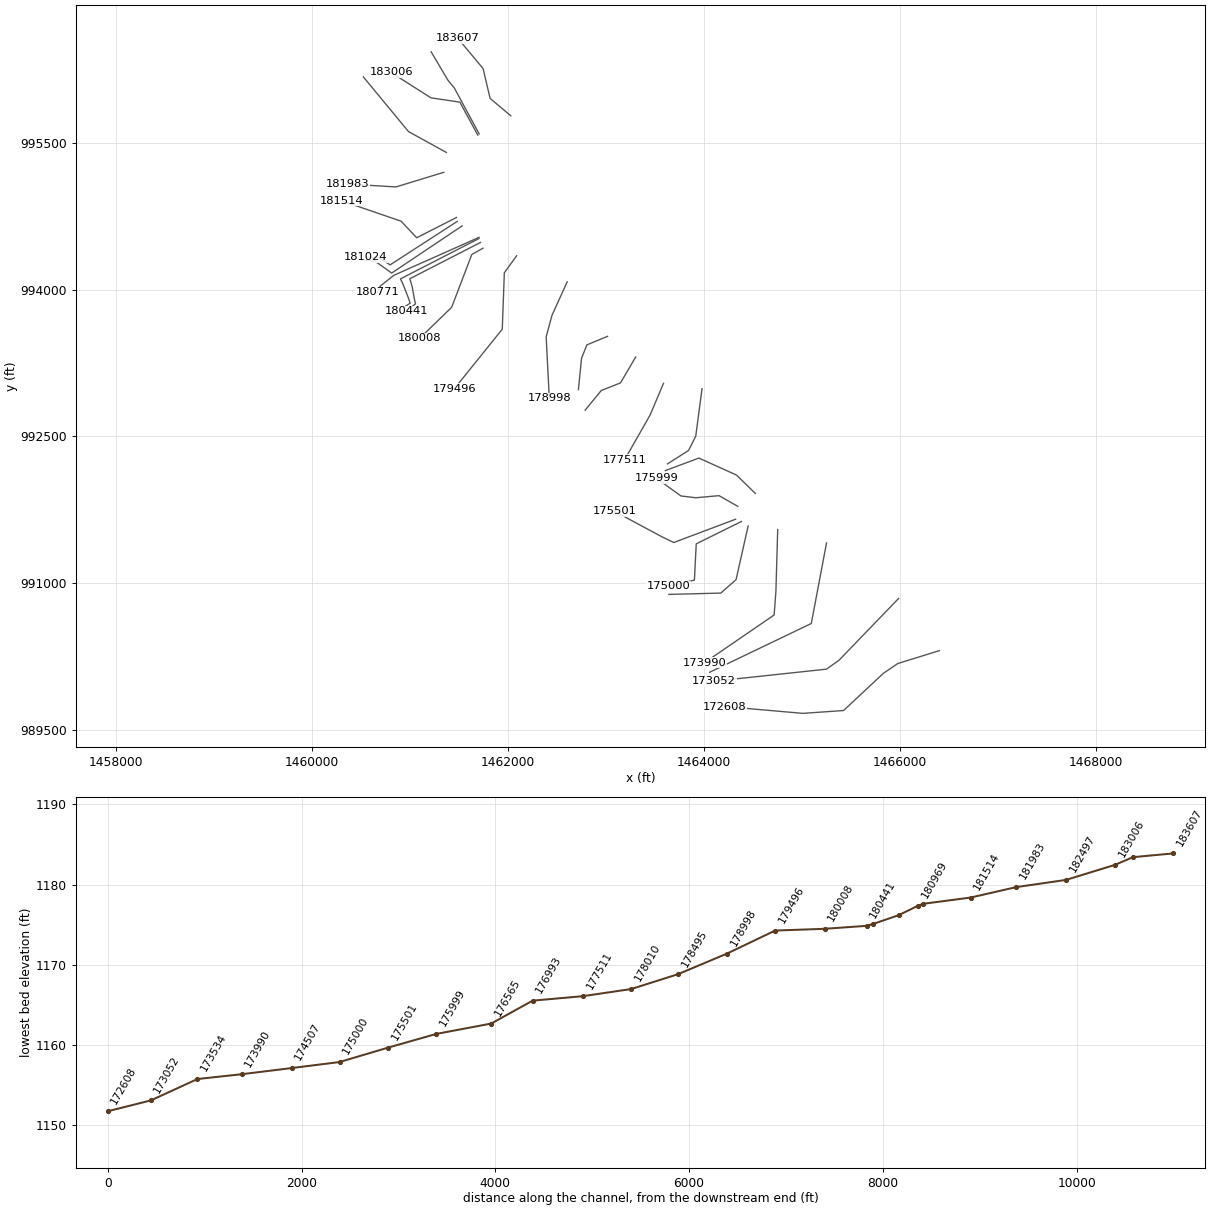
HEC-RAS study Fisher River.prj: Fisher River Limited Detail Study

--- Fisher River.g01 (geometry) --- (continued)

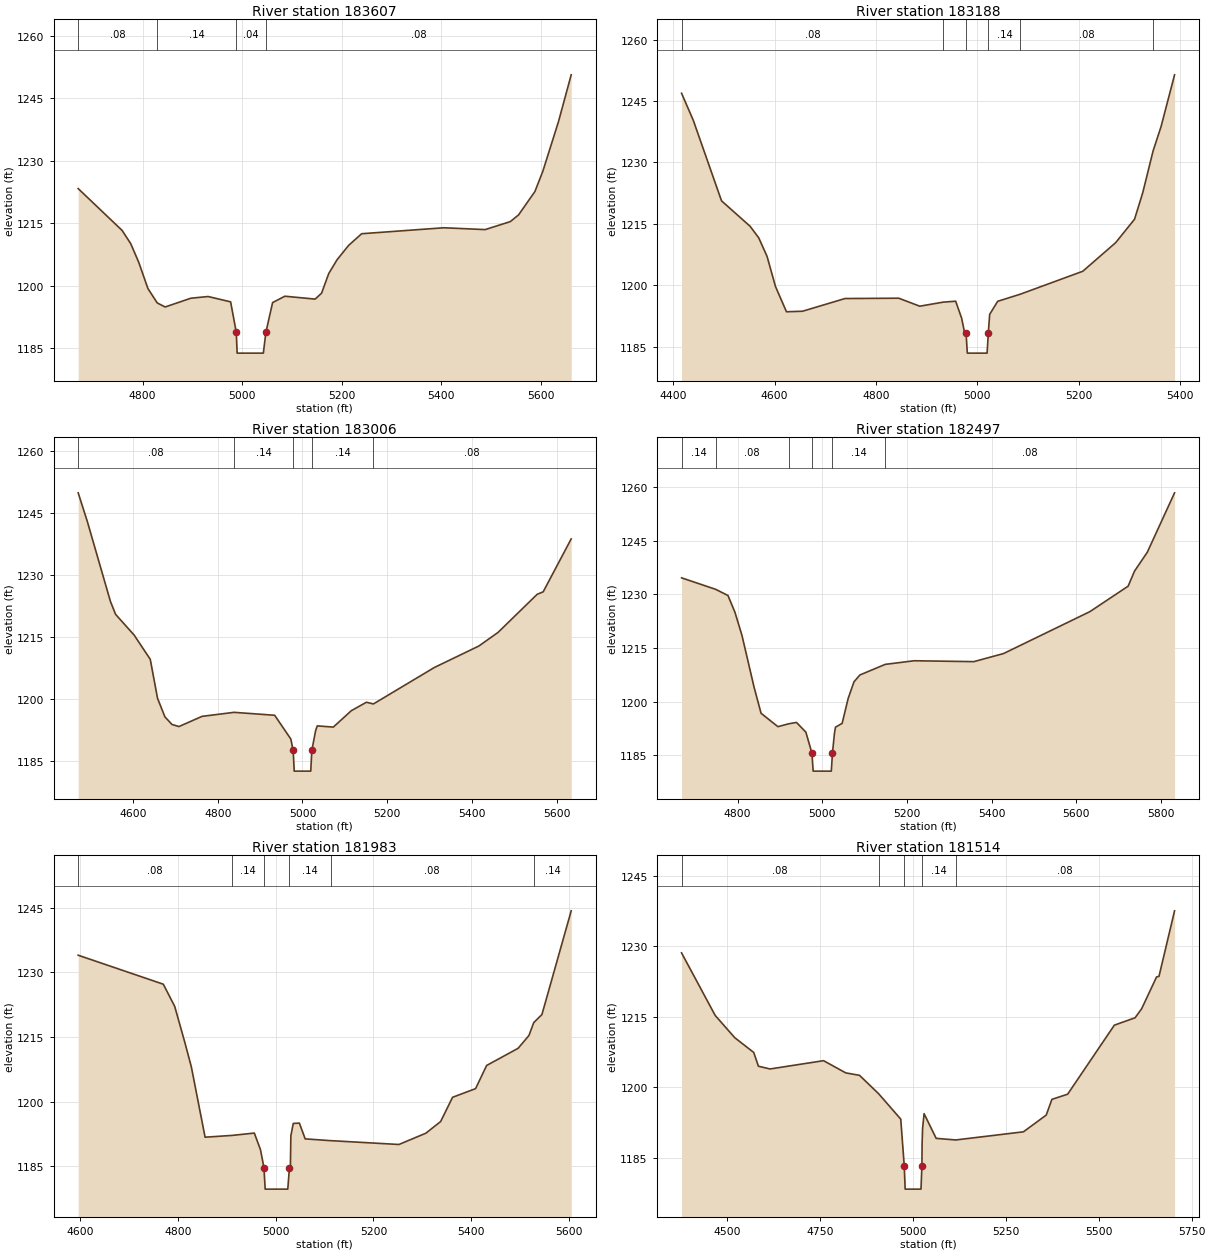
Type RM Length L Ch R = 1,183607,419,419,419
BEGIN DESCRIPTION:
Fisher River 367.0
END DESCRIPTION:
XS GIS Cut Line= 4
      1462026.91       995774.54      1461815.65       995952.12
      1461743.91       996257.00      1461486.87       996565.85
#Sta/Elev= 30
  4670.7 1223.33  4759.0 1213.30  4776.4 1210.11  4792.5 1205.64  4810.8 1199.39
  4829.6 1195.92  4845.5 1194.95  4897.1 1197.05  4931.9 1197.46  4977.1 1196.18
  4988.5 1188.89  4990.2 1183.89  5042.9 1183.89  5048.0 1188.89  5061.5 1196.01
  5086.2 1197.53  5147.0 1196.84  5159.9 1198.25  5174.3 1202.96  5191.0 1206.26
  5214.4 1209.73  5240.5 1212.51  5405.8 1213.94  5488.7 1213.50  5539.2 1215.41
  5555.9 1217.02  5588.8 1222.63  5604.7 1227.49  5636.1 1239.36  5661.7 1250.60
#Mann=4,-1,0
  4670.7    0.08       0  4829.6    0.14       0  4988.5    0.04       0
  5048.0    0.08       0
Bank Sta=4988.5,5048
XS Rating Curve= 0
Exp/Cntr=0.3,0.1

Type RM Length L Ch R = 1,183188,182,182,182
BEGIN DESCRIPTION:
Fisher River 366.5
END DESCRIPTION:
XS GIS Cut Line= 4
      1461704.06       995589.44      1461450.99       996057.73
      1461383.24       996141.42      1461213.85       996428.38
#Sta/Elev= 30
  4416.4 1246.88  4439.5 1240.29  4495.3 1220.61  4551.6 1214.41  4568.6 1211.61
  4585.1 1207.08  4601.8 1199.70  4623.5 1193.52  4655.2 1193.65  4739.1 1196.75
  4845.2 1196.83  4886.6 1194.88  4932.8 1195.87  4957.5 1196.10  4969.3 1191.94
  4975.1 1188.42  4978.0 1188.42  4980.5 1183.42  5019.5 1183.42  5022.0 1188.42
  5024.6 1192.88  5040.4 1196.07  5085.3 1197.82  5208.4 1203.41  5273.3 1210.39
  5310.6 1216.12  5326.7 1222.55  5347.1 1232.74  5363.0 1238.77  5389.6 1251.38
#Mann=6,-1,0
  4416.4    0.08       0  4932.8    0.14       0  4978.0    0.04       0
  5022.0    0.14       0  5085.3    0.08       0  5347.1    0.14       0
Bank Sta=4978,5022
XS Rating Curve= 0
Exp/Cntr=0.3,0.1

Type RM Length L Ch R = 1,183006,509,509,509
BEGIN DESCRIPTION:
Fisher River 366.0
END DESCRIPTION:
XS GIS Cut Line= 4
      1461690.10       995577.52      1461506.78       995914.26
      1461211.87       995958.10      1460805.35       996217.15
#Sta/Elev= 30
  4470.6 1249.89  4492.2 1242.94  4546.7 1223.58  4558.9 1220.45  4602.6 1215.44
  4640.7 1209.56  4657.9 1200.11  4675.3 1195.62  4691.9 1193.78  4708.4 1193.27
  4763.0 1195.74  4838.4 1196.71  4934.4 1196.00  4972.5 1190.24  4978.0 1187.47
  4980.5 1182.47  5019.5 1182.47  5022.0 1187.47  5031.1 1192.32  5034.9 1193.43
  5072.8 1193.14  5115.4 1197.12  5151.0 1199.16  5167.3 1198.74  5311.5 1207.59
  5416.1 1212.77  5461.5 1216.07  5553.8 1225.30  5568.1 1225.91  5634.2 1238.73
#Mann=5,-1,0
  4470.6    0.08       0  4838.4    0.14       0  4978.0    0.04       0
  5022.0    0.14       0  5167.3    0.08       0
Bank Sta=4978,5022
XS Rating Curve= 0
Exp/Cntr=0.3,0.1

Type RM Length L Ch R = 1,182497,514,514,514
BEGIN DESCRIPTION:
Fisher River 365.0
END DESCRIPTION:
XS GIS Cut Line= 4
      1461369.30       995400.34      1461134.77       995529.58
      1460982.71       995613.56      1460522.41       996171.50
#Sta/Elev= 30
  4667.7 1234.62  4748.3 1231.41  4777.4 1229.68  4794.0 1224.94  4810.5 1218.50
  4839.1 1204.02  4855.5 1196.77  4895.3 1193.01  4920.9 1193.81  4939.2 1194.20
  4961.4 1191.48  4975.8 1185.58  4978.6 1180.58  5021.5 1180.58  5024.2 1185.58
  5028.8 1191.01  5031.3 1192.86  5047.1 1193.93  5061.3 1200.89  5075.0 1205.53
  5089.0 1207.46  5148.9 1210.43  5217.5 1211.44  5358.2 1211.19  5428.4 1213.45
  5632.4 1225.17  5722.8 1232.29  5737.9 1236.50  5768.1 1241.78  5832.5 1258.39
#Mann=6,-1,0
  4667.7    0.14       0  4748.3    0.08       0  4920.9    0.14       0
  4975.8    0.04       0  5024.2    0.14       0  5148.9    0.08       0
Bank Sta=4975.8,5024.2
XS Rating Curve= 0
Exp/Cntr=0.3,0.1

Type RM Length L Ch R = 1,181983,469,469,469
BEGIN DESCRIPTION:
Fisher River 364.0
END DESCRIPTION:
XS GIS Cut Line= 3
      1461343.41       995197.50      1460855.18       995048.04
      1460358.97       995077.93
#Sta/Elev= 30
  4596.5 1233.96  4770.5 1227.23  4793.8 1222.08  4814.3 1213.80  4827.7 1208.10
  4855.9 1191.73  4911.6 1192.15  4956.5 1192.69  4969.1 1188.83  4976.2 1184.68
  4978.7 1179.68  5024.9 1179.68  5028.3 1184.68  5030.2 1184.68  5031.2 1192.05
  5036.1 1194.92  5048.6 1195.00  5060.5 1191.34  5112.4 1190.93  5252.1 1190.04
  5307.2 1192.66  5337.4 1195.37  5361.7 1200.99  5408.8 1203.00  5431.3 1208.37
  5495.7 1212.36  5517.8 1215.32  5527.6 1218.32  5544.4 1220.20  5604.2 1244.26
#Mann=6,-1,0
  4596.5    0.08       0  4911.6    0.14       0  4976.2    0.04       0
  5028.3    0.14       0  5112.4    0.08       0  5527.6    0.14       0
Bank Sta=4976.2,5028.3
XS Rating Curve= 0
Exp/Cntr=0.3,0.1

Type RM Length L Ch R = 1,181514,490,490,490
BEGIN DESCRIPTION:
Fisher River 363.0
END DESCRIPTION:
XS GIS Cut Line= 4
      1461472.92       994736.19      1461066.40       994528.94
      1460906.99       994698.32      1460303.16       994905.58
#Sta/Elev= 30
  4376.7 1228.59  4467.3 1215.29  4520.0 1210.56  4571.0 1207.43  4583.7 1204.50
  4615.0 1203.92  4759.0 1205.68  4819.0 1203.08  4855.7 1202.57  4907.0 1198.68
  4966.8 1193.26  4976.2 1183.38  4978.7 1178.38  5021.3 1178.38  5023.8 1183.38
  5024.3 1188.01  5025.6 1191.23  5029.6 1194.42  5062.2 1189.17  5114.9 1188.83
  5297.1 1190.56  5358.5 1194.12  5373.8 1197.46  5416.2 1198.56  5541.9 1213.23
  5597.7 1214.80  5615.4 1216.72  5655.6 1223.49  5662.0 1223.59  5704.0 1237.53
#Mann=5,-1,0
  4376.7    0.08       0  4907.0    0.14       0  4976.2    0.04       0
  5023.8    0.14       0  5114.9    0.08       0
Bank Sta=4976.2,5023.8
XS Rating Curve= 0
Exp/Cntr=0.5,0.3

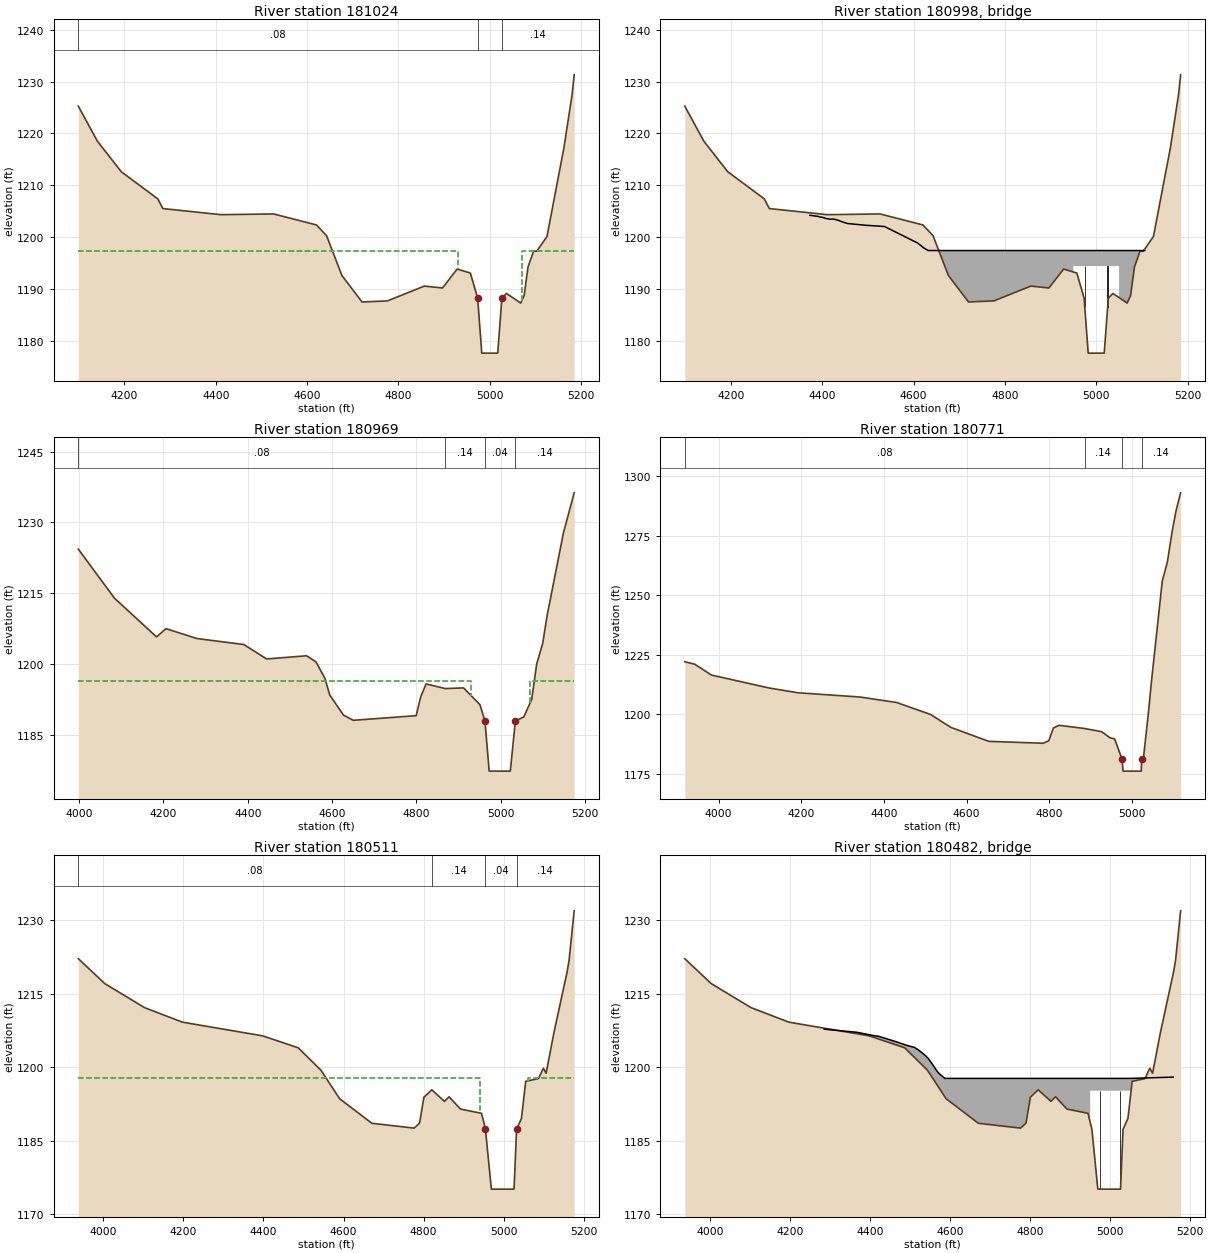
Type RM Length L Ch R = 1,181024,55,55,55
BEGIN DESCRIPTION:
Hidden Valley Rd (2) - US
END DESCRIPTION:
XS GIS Cut Line= 4
      1461480.84       994696.30      1460795.40       994251.96
      1460679.82       994325.69      1460548.32       994331.67
#Sta/Elev= 30
  4099.2 1225.26  4140.9 1218.51  4193.2 1212.61  4273.4 1207.36  4284.2 1205.50
  4411.7 1204.32  4526.8 1204.46  4620.5 1202.34  4642.7 1200.27  4676.3 1192.58
  4720.4 1187.47  4776.0 1187.68  4856.9 1190.54  4896.5 1190.17  4928.7 1193.83
  4957.6 1193.05  4973.5 1188.20  4982.5 1177.60  5017.5 1177.60  5026.5 1188.20
  5036.7 1189.12  5067.8 1187.26  5075.3 1188.71  5083.8 1194.24  5096.0 1197.27
  5102.9 1197.27  5125.3 1200.10  5162.6 1217.32  5180.5 1227.63  5184.8 1231.31
#Mann=3,-1,0
  4099.2    0.08       0  4973.5    0.04       0  5026.5    0.14       0
#XS Ineff=2,0
    0.00 4930.00 1197.40 5070.00    0.00 1197.40
Permanent Ineff=
       F       F
Bank Sta=4973.5,5026.5
XS Rating Curve= 0
Exp/Cntr=0.5,0.3

Type RM Length L Ch R =3,180998,,,
BEGIN DESCRIPTION:
Hidden Valley Rd (2) - TOR
Structure ID: LDS_FR_15
Approximate Survey Structure
END DESCRIPTION:
Bridge Culvert--1,0,-1,-1,0
Deck Dist Width WeirC Skew NumUp NumDn MinLoCord MaxHiCord MaxSubmerge Is_Ogee
17,18,3,,23,23,,,0.95,0,1,1,,,
  4373.0  4391.0  4393.5  4402.6  4410.0  4413.6  4417.1  4422.7  4426.1  4433.7
  4443.6  4454.6  4454.7  4496.1  4536.4  4609.4  4622.8  4632.2  4950.0  4950.0
  5050.0  5050.0  5106.3
 1204.20 1203.99 1203.91 1203.76 1203.53 1203.52 1203.43 1203.48 1203.45 1203.28
 1202.94 1202.63 1202.62 1202.27 1202.04 1198.83 1197.88 1197.40 1197.40 1197.40
 1197.40 1197.40 1197.40
 1157.60 1157.60 1157.60 1157.60 1157.60 1157.60 1157.60 1157.60 1157.60 1157.60
 1157.60 1157.60 1157.60 1157.60 1157.60 1157.60 1157.60 1157.60 1157.60 1194.40
 1194.40 1157.60 1157.60
  4373.0  4391.0  4393.5  4402.6  4410.0  4413.6  4417.1  4422.7  4426.1  4433.7
  4443.6  4454.6  4454.7  4496.1  4536.4  4609.4  4622.8  4632.2  4950.0  4950.0
  5050.0  5050.0  5106.3
 1204.20 1203.99 1203.91 1203.76 1203.53 1203.52 1203.43 1203.48 1203.45 1203.28
 1202.94 1202.63 1202.62 1202.27 1202.04 1198.83 1197.88 1197.40 1197.40 1197.40
 1197.40 1197.40 1197.40
 1157.60 1157.60 1157.60 1157.60 1157.60 1157.60 1157.60 1157.60 1157.60 1157.60
 1157.60 1157.60 1157.60 1157.60 1157.60 1157.60 1157.60 1157.60 1157.60 1194.40
 1194.40 1157.60 1157.60
Pier Skew, UpSta & Num, DnSta & Num=,4975,2,4975,2,0,0,0,0,0
       1       1
 1191.43 1194.40
       1       1
 1191.18 1194.40
Pier Skew, UpSta & Num, DnSta & Num=,5025,2,5025,2,0,0,0,0,0
       1       1
 1191.43 1194.40
       1       1
 1191.18 1194.40
BR Coef=1,1,0,1.25,0,,,0.8,0,2,0,
WSPro=,,,, 1 ,,,, 0 ,,,, 0 ,,,,-1 ,-1 ,-1 , 0 , 0 , 0 , 0 , 0
BC Design=,,0,,0,,,,,,

Type RM Length L Ch R = 1,180969,198,198,198
BEGIN DESCRIPTION:
Hidden Valley Rd (2) - DS
END DESCRIPTION:
XS GIS Cut Line= 4
      1461530.68       994650.49      1460811.34       994168.27
      1460643.95       994287.83      1460540.30       994301.78
#Sta/Elev= 30
  3998.0 1224.35  4083.6 1213.98  4183.5 1205.77  4206.0 1207.51  4279.4 1205.42
  4390.4 1204.16  4444.7 1201.10  4539.5 1201.77  4561.8 1200.48  4583.1 1196.97
  4594.4 1193.47  4627.1 1189.21  4650.3 1188.11  4799.4 1189.09  4810.2 1193.07
  4823.0 1195.81  4868.6 1194.83  4912.0 1194.97  4950.7 1191.43  4962.7 1187.95
  4972.7 1177.35  5022.8 1177.35  5034.8 1187.95  5054.8 1188.82  5073.6 1192.54
  5085.5 1200.05  5099.5 1204.33  5110.5 1210.45  5148.8 1227.75  5174.3 1236.27
#Mann=4,-1,0
  3998.0    0.08       0  4868.6    0.14       0  4962.7    0.04       0
  5034.8    0.14       0
#XS Ineff=2,0
    0.00 4930.00 1196.50 5070.00    0.00 1196.50
Permanent Ineff=
       F       F
Bank Sta=4962.7,5034.8
XS Rating Curve= 0
Exp/Cntr=0.5,0.3

Type RM Length L Ch R = 1,180771,260,260,260
BEGIN DESCRIPTION:
Fisher River 362.0
END DESCRIPTION:
XS GIS Cut Line= 4
      1461702.03       994532.91      1460835.25       994146.35
      1460693.77       994034.76      1460663.87       993970.98
#Sta/Elev= 30
  3918.3 1222.05  3942.3 1221.04  3982.9 1216.47  4123.2 1211.02  4192.0 1209.05
  4342.6 1207.26  4430.6 1204.98  4513.3 1199.93  4561.7 1194.55  4653.8 1188.67
  4785.3 1187.88  4799.0 1188.90  4810.3 1194.31  4824.0 1195.40  4885.9 1194.05
  4926.8 1192.72  4947.6 1190.12  4958.4 1189.67  4976.2 1181.18  4978.7 1176.18
  5022.7 1176.18  5023.8 1181.18  5027.8 1181.26  5039.4 1199.52  5047.3 1213.53
  5073.5 1255.76  5086.0 1263.97  5097.7 1276.89  5107.0 1285.46  5118.0 1292.92
#Mann=4,-1,0
  3918.3    0.08       0  4885.9    0.14       0  4976.2    0.04       0
  5023.8    0.14       0
#XS Ineff=2,0
    0.00 4824.00 1195.40               0
Permanent Ineff=
       F       F
Bank Sta=4976.2,5023.8
XS Rating Curve= 0
Exp/Cntr=0.5,0.3

Type RM Length L Ch R = 1,180511,70,70,70
BEGIN DESCRIPTION:
Hidden Valley Rd - US
END DESCRIPTION:
XS GIS Cut Line= 6
      1461702.05       994520.96      1460901.09       994109.25
      1460926.68       994054.42      1460977.85       993924.65
      1460999.79       993860.68      1460941.26       993822.28
#Sta/Elev= 30
  3937.7 1222.13  4003.5 1217.06  4102.9 1212.15  4197.5 1209.18  4398.2 1206.38
  4486.9 1203.94  4543.6 1199.37  4590.3 1193.55  4670.8 1188.54  4776.3 1187.55
  4789.8 1188.57  4800.7 1193.85  4820.3 1195.37  4852.1 1193.01  4863.5 1193.94
  4892.0 1191.44  4944.6 1190.57  4954.4 1187.30  4969.1 1175.10  5025.8 1175.10
  5032.1 1187.30  5044.3 1189.51  5054.9 1197.10  5086.9 1197.66  5099.0 1199.77
  5105.9 1198.76  5125.4 1207.03  5158.4 1219.46  5163.2 1221.78  5175.9 1231.90
#Mann=4,-1,0
  3937.7    0.08       0  4820.3    0.14       0  4954.4    0.04       0
  5032.1    0.14       0
#XS Ineff=2,0
    0.00 4940.00 1197.70 5060.00    0.00 1197.70
Permanent Ineff=
       F       F
Bank Sta=4954.4,5032.1
XS Rating Curve= 0
Exp/Cntr=0.5,0.3

Type RM Length L Ch R =3,180482,,,
BEGIN DESCRIPTION:
Hidden Valley Rd - TOR
Structure ID: LDS_FR_14
Approximate Survey Structure
END DESCRIPTION:
Bridge Culvert--1,0,-1,-1,0
Deck Dist Width WeirC Skew NumUp NumDn MinLoCord MaxHiCord MaxSubmerge Is_Ogee
35,20,3,,19,19,,,0.95,0,1,1,,,
  4285.7  4367.9  4406.7  4421.4  4465.9  4492.1  4511.4  4522.0  4534.9  4545.0
  4557.7  4564.7  4571.0  4587.1  4950.0  4950.0  5050.0  5050.0  5157.2
 1207.75 1207.11 1206.47 1206.30 1205.17 1204.44 1204.02 1203.45 1202.62 1201.84
 1200.41 1199.52 1198.83 1197.70 1197.70 1197.70 1197.70 1197.70 1197.96
 1155.10 1155.10 1155.10 1155.10 1155.10 1155.10 1155.10 1155.10 1155.10 1155.10
 1155.10 1155.10 1155.10 1155.10 1155.10 1195.20 1195.20 1155.10 1155.10
  4285.7  4367.9  4406.7  4421.4  4465.9  4492.1  4511.4  4522.0  4534.9  4545.0
  4557.7  4564.7  4571.0  4587.1  4950.0  4950.0  5050.0  5050.0  5157.2
 1207.75 1207.11 1206.47 1206.30 1205.17 1204.44 1204.02 1203.45 1202.62 1201.84
 1200.41 1199.52 1198.83 1197.70 1197.70 1197.70 1197.70 1197.70 1197.96
 1155.10 1155.10 1155.10 1155.10 1155.10 1155.10 1155.10 1155.10 1155.10 1155.10
 1155.10 1155.10 1155.10 1155.10 1155.10 1195.20 1195.20 1155.10 1155.10
Pier Skew, UpSta & Num, DnSta & Num=,4975,2,4975,2,0,0,0,0,0
       1       1
 1186.70 1195.20
       1       1
 1186.45 1195.20
Pier Skew, UpSta & Num, DnSta & Num=,5025,2,5025,2,0,0,0,0,0
       1       1
 1186.70 1195.20
       1       1
 1186.45 1195.20
BR Coef=1,1,0,1.25,0,,,0.8,0,2,0,
WSPro=,,,, 1 ,,,, 0 ,,,, 0 ,,,,-1 ,-1 ,-1 , 0 , 0 , 0 , 0 , 0
BC Design=,,0,,0,,,,,,

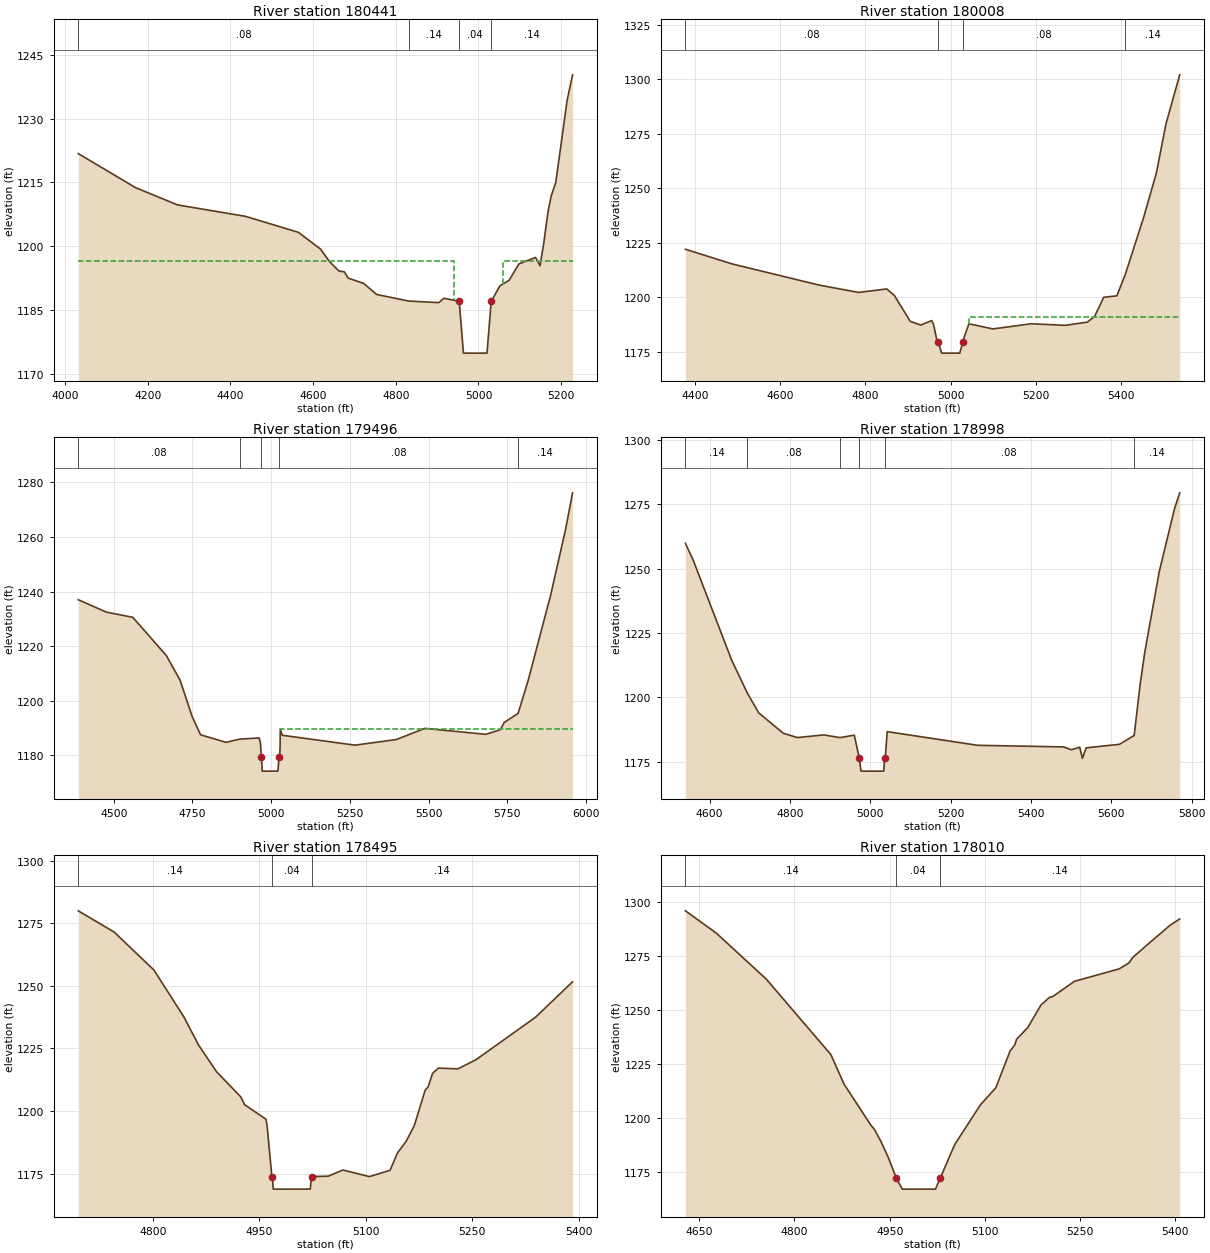
Type RM Length L Ch R = 1,180441,433,433,433
BEGIN DESCRIPTION:
Hidden Valley Rd - DS
END DESCRIPTION:
XS GIS Cut Line= 6
      1461718.04       994481.14      1460996.66       994110.48
      1461020.57       994028.78      1461042.49       993905.23
      1461054.45       993853.42      1460958.78       993779.68
#Sta/Elev= 30
  4032.0 1221.80  4170.5 1213.79  4272.2 1209.72  4436.6 1207.03  4564.3 1203.28
  4618.2 1199.31  4640.3 1196.32  4662.4 1194.18  4675.6 1193.98  4685.1 1192.49
  4722.5 1191.25  4753.9 1188.65  4831.3 1187.10  4904.2 1186.73  4916.5 1187.76
  4953.5 1187.05  4963.7 1174.85  5020.7 1174.85  5030.9 1187.05  5052.2 1190.71
  5073.9 1191.95  5098.0 1195.84  5138.1 1197.37  5149.0 1195.41  5157.5 1200.40
  5168.4 1208.15  5175.9 1211.82  5187.0 1214.95  5214.3 1234.21  5227.6 1240.33
#Mann=4,-1,0
  4032.0    0.08       0  4831.3    0.14       0  4953.5    0.04       0
  5030.9    0.14       0
#XS Ineff=2,0
    0.00 4940.00 1196.50 5060.00    0.00 1196.50
Permanent Ineff=
       F       F
Bank Sta=4953.5,5030.9
XS Rating Curve= 0
Exp/Cntr=0.5,0.3

Type RM Length L Ch R = 1,180008,512,512,512
BEGIN DESCRIPTION:
Fisher River 360.0
END DESCRIPTION:
XS GIS Cut Line= 4
      1461743.30       994422.20      1461629.01       994358.20
      1461423.33       993818.88      1461098.83       993503.51
#Sta/Elev= 30
  4377.2 1222.12  4486.6 1215.40  4691.2 1205.68  4783.9 1202.31  4849.9 1203.93
  4868.0 1200.90  4905.0 1189.09  4929.7 1187.35  4955.4 1189.40  4960.0 1187.52
  4968.7 1179.48  4971.4 1179.48  4978.7 1174.48  5021.3 1174.48  5028.7 1179.48
  5030.6 1179.48  5030.9 1181.38  5042.9 1187.93  5099.3 1185.58  5189.0 1187.94
  5269.6 1187.23  5320.8 1188.69  5338.1 1191.31  5359.5 1200.10  5390.4 1200.75
  5410.2 1210.63  5452.6 1236.34  5483.0 1257.00  5505.5 1279.50  5537.9 1302.11
#Mann=4,-1,0
  4377.2    0.08       0  4971.4    0.04       0  5028.7    0.08       0
  5410.2    0.14       0
#XS Ineff=2,0
       0                 5042.90    0.00 1191.00
Permanent Ineff=
       F       F
Bank Sta=4971.4,5028.7
XS Rating Curve= 0
Exp/Cntr=0.3,0.1

Type RM Length L Ch R = 1,179496,498,498,498
BEGIN DESCRIPTION:
Fisher River 359.0
END DESCRIPTION:
XS GIS Cut Line= 4
      1462086.08       994344.51      1461960.84       994171.21
      1461939.80       993594.92      1461450.75       992987.02
#Sta/Elev= 30
  4387.0 1237.04  4476.5 1232.49  4560.1 1230.61  4666.8 1216.62  4710.6 1207.57
  4748.7 1194.34  4775.7 1187.57  4856.3 1184.81  4899.5 1185.96  4962.1 1186.42
  4965.9 1184.58  4969.1 1179.26  4971.8 1174.26  5021.3 1174.26  5025.2 1179.26
  5026.6 1179.26  5028.3 1182.59  5029.0 1189.50  5035.7 1187.39  5266.2 1183.77
  5397.6 1185.82  5488.1 1189.91  5682.5 1187.74  5728.2 1189.43  5740.6 1192.09
  5784.8 1195.42  5816.9 1207.55  5887.9 1238.60  5935.6 1262.80  5957.7 1276.19
#Mann=5,-1,0
  4387.0    0.08       0  4899.5    0.14       0  4969.1    0.04       0
  5025.2    0.08       0  5784.8    0.14       0
#XS Ineff=2,0
       0                 5029.10    0.00 1189.60
Permanent Ineff=
       F       F
Bank Sta=4969.1,5025.2
XS Rating Curve= 0
Exp/Cntr=0.3,0.1

Type RM Length L Ch R = 1,178998,503,503,503
BEGIN DESCRIPTION:
Fisher River 358.0
END DESCRIPTION:
XS GIS Cut Line= 4
      1462602.55       994079.44      1462447.14       993736.61
      1462387.72       993517.22      1462419.71       992891.04
#Sta/Elev= 30
  4539.7 1259.87  4559.1 1253.31  4654.8 1214.52  4694.0 1201.66  4722.1 1194.03
  4783.5 1186.09  4818.4 1184.42  4884.2 1185.46  4924.5 1184.40  4960.1 1185.36
  4972.7 1176.38  4976.9 1171.38  5033.5 1171.38  5035.6 1176.38  5037.8 1177.90
  5042.2 1186.72  5267.4 1181.41  5481.2 1180.79  5500.5 1179.70  5521.4 1180.65
  5528.2 1176.38  5537.5 1180.43  5620.2 1181.79  5655.9 1185.12  5657.0 1185.27
  5671.7 1204.78  5683.6 1217.77  5719.5 1248.92  5757.4 1273.29  5770.4 1279.51
#Mann=6,-1,0
  4539.7    0.14       0  4694.0    0.08       0  4924.5    0.14       0
  4972.7    0.04       0  5035.6    0.08       0  5655.9    0.14       0
#XS Ineff=2,0
       0                 5042.20    0.00 1186.72
Permanent Ineff=
       F       F
Bank Sta=4972.7,5035.6
XS Rating Curve= 0
Exp/Cntr=0.3,0.1

Type RM Length L Ch R = 1,178495,485,485,485
BEGIN DESCRIPTION:
Fisher River 357.0
END DESCRIPTION:
XS GIS Cut Line= 4
      1463013.86       993521.78      1462803.64       993434.95
      1462748.79       993297.83      1462716.79       992977.85
#Sta/Elev= 30
  4694.9 1279.97  4745.6 1271.47  4801.7 1256.28  4844.0 1237.49  4864.6 1226.31
  4889.8 1215.72  4924.0 1205.65  4929.4 1202.53  4959.5 1196.74  4961.2 1193.80
  4967.6 1174.44  4968.5 1173.82  4969.7 1168.82  5021.9 1168.82  5023.8 1173.82
  5047.2 1173.99  5068.0 1176.46  5105.2 1173.82  5134.4 1176.34  5144.8 1183.26
  5157.0 1187.90  5168.4 1194.07  5183.9 1208.36  5188.0 1209.62  5194.3 1215.05
  5202.6 1217.16  5229.9 1216.84  5255.2 1220.45  5339.4 1237.46  5391.6 1251.63
#Mann=3,-1,0
  4694.9    0.14       0  4968.5    0.04       0  5023.8    0.14       0
Bank Sta=4968.5,5023.8
XS Rating Curve= 0
Exp/Cntr=0.3,0.1

Type RM Length L Ch R = 1,178010,499,499,499
BEGIN DESCRIPTION:
Fisher River 356.0
END DESCRIPTION:
XS GIS Cut Line= 4
      1463301.81       993311.52      1463146.43       993046.45
      1462949.90       992968.75      1462785.37       992767.67
#Sta/Elev= 30
  4628.4 1296.08  4676.9 1285.77  4755.8 1264.38  4857.5 1229.36  4878.1 1215.73
  4920.5 1196.60  4926.0 1194.69  4935.7 1189.43  4947.6 1181.89  4960.6 1171.96
  4969.9 1166.96  5022.2 1166.96  5029.5 1171.96  5052.5 1187.66  5092.8 1206.01
  5117.2 1213.98  5139.7 1231.06  5147.0 1233.85  5150.0 1236.51  5167.5 1241.93
  5188.5 1252.47  5202.1 1256.00  5206.8 1256.30  5241.1 1263.38  5311.6 1269.15
  5326.7 1271.88  5333.1 1274.51  5354.6 1280.05  5391.7 1289.43  5406.8 1292.31
#Mann=3,-1,0
  4628.4    0.14       0  4960.6    0.04       0  5029.5    0.14       0
Bank Sta=4960.6,5029.5
XS Rating Curve= 0
Exp/Cntr=0.3,0.1

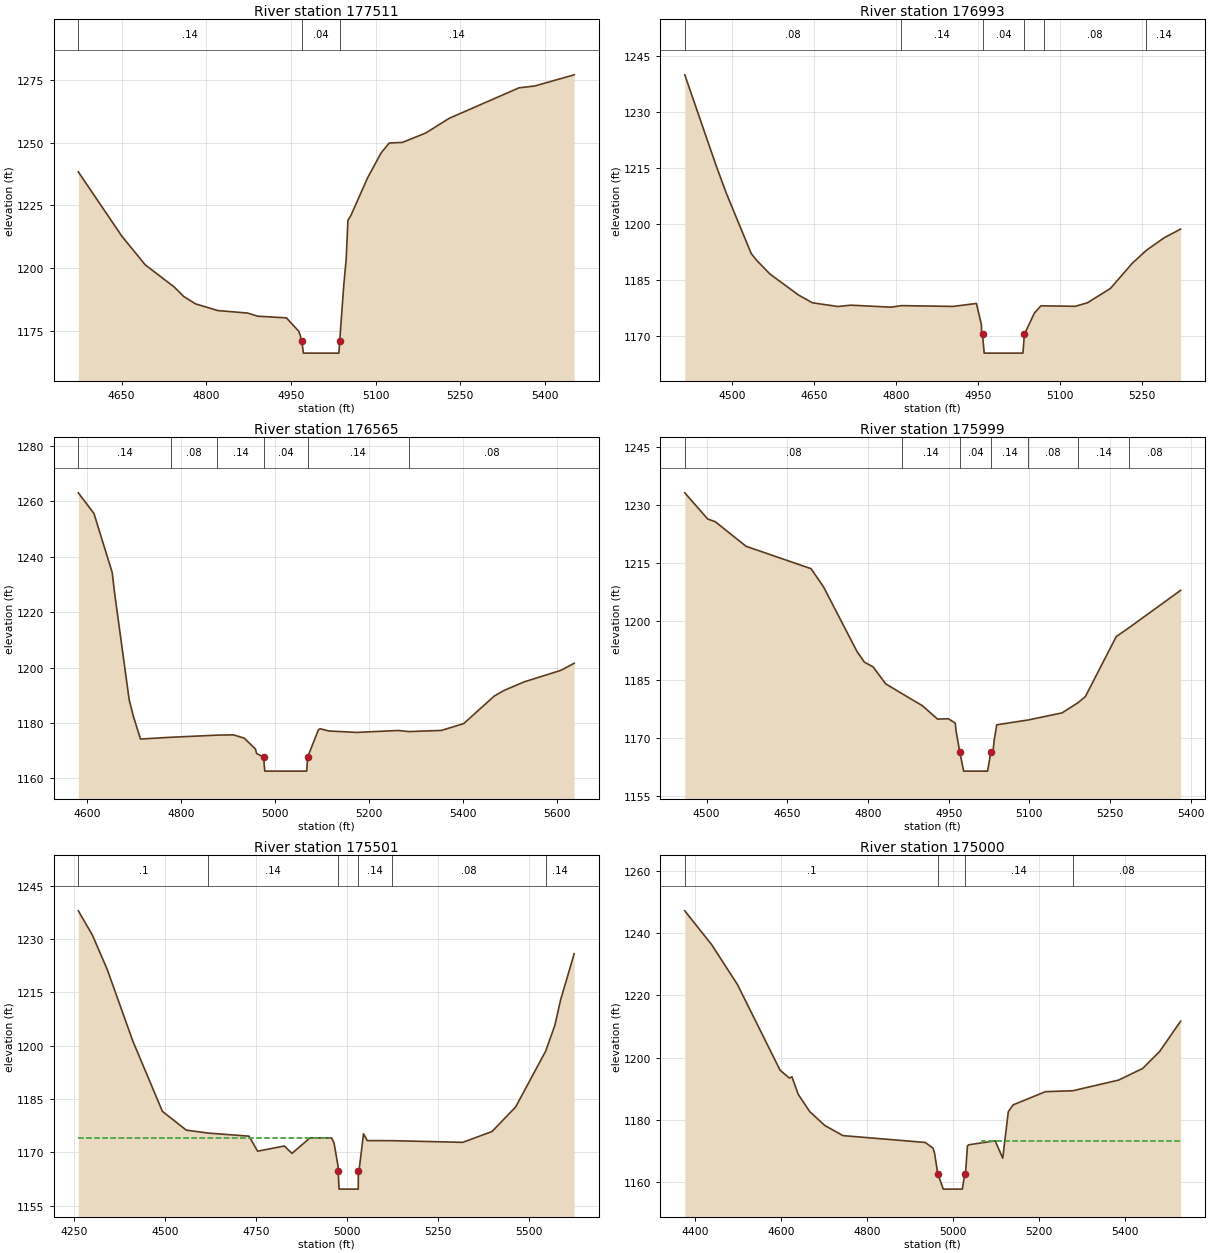
Type RM Length L Ch R = 1,177511,518,518,518
BEGIN DESCRIPTION:
Fisher River 355.0
END DESCRIPTION:
XS GIS Cut Line= 3
      1463585.21       993041.91      1463448.09       992717.37
      1463187.57       992260.33
#Sta/Elev= 30
  4573.4 1238.31  4650.5 1212.69  4691.9 1201.27  4743.0 1192.48  4760.1 1188.66
  4781.2 1185.70  4820.4 1183.04  4873.2 1182.05  4891.0 1180.79  4942.1 1180.12
  4964.0 1174.75  4967.0 1172.83  4967.6 1171.08  4969.2 1171.07  4972.2 1166.07
  5035.0 1166.07  5036.5 1171.07  5043.7 1193.26  5047.9 1203.48  5051.0 1218.98
  5056.3 1220.97  5086.1 1236.07  5109.7 1245.84  5124.2 1249.84  5147.5 1250.07
  5189.0 1253.82  5230.3 1259.66  5354.3 1271.84  5381.5 1272.53  5451.8 1277.01
#Mann=3,-1,0
  4573.4    0.14       0  4969.2    0.04       0  5036.5    0.14       0
Bank Sta=4969.2,5036.5
XS Rating Curve= 0
Exp/Cntr=0.3,0.1

Type RM Length L Ch R = 1,176993,428,428,428
BEGIN DESCRIPTION:
Fisher River 354.0
END DESCRIPTION:
XS GIS Cut Line= 4
      1463978.27       992987.02      1463914.28       992502.56
      1463841.15       992356.30      1463626.36       992219.20
#Sta/Elev= 30
  4413.6 1239.98  4470.4 1215.90  4489.2 1208.43  4535.1 1192.16  4545.4 1190.29
  4569.5 1186.66  4621.7 1181.05  4647.0 1178.98  4693.4 1177.99  4717.2 1178.34
  4791.1 1177.81  4810.0 1178.22  4904.4 1178.01  4947.1 1178.80  4956.2 1173.10
  4956.5 1170.51  4958.2 1170.51  4961.3 1165.51  5032.2 1165.51  5034.7 1170.51
  5053.2 1176.25  5065.1 1178.18  5071.0 1178.16  5128.0 1178.04  5150.2 1178.99
  5192.2 1182.82  5231.9 1189.52  5257.8 1193.00  5290.4 1196.37  5320.6 1198.70
#Mann=6,-1,0
  4413.6    0.08       0  4810.0    0.14       0  4958.2    0.04       0
  5034.7    0.14       0  5071.0    0.08       0  5257.8    0.14       0
Bank Sta=4958.2,5034.7
XS Rating Curve= 0
Exp/Cntr=0.3,0.1

Type RM Length L Ch R = 1,176565,566,566,566
BEGIN DESCRIPTION:
Fisher River 353.0
END DESCRIPTION:
XS GIS Cut Line= 4
      1464522.16       991917.54      1464330.20       992104.92
      1463946.28       992278.60      1463603.52       992150.64
#Sta/Elev= 30
  4580.9 1263.01  4614.2 1255.55  4653.0 1234.28  4658.2 1226.74  4689.1 1188.41
  4697.8 1182.57  4713.3 1174.22  4778.1 1174.86  4876.7 1175.63  4911.0 1175.73
  4933.8 1174.57  4958.1 1170.60  4960.3 1169.05  4975.3 1167.65  4977.8 1162.65
  5067.1 1162.65  5068.9 1167.65  5092.0 1177.57  5095.7 1177.94  5114.2 1177.13
  5173.7 1176.61  5261.7 1177.31  5284.8 1176.91  5353.8 1177.33  5401.3 1179.79
  5466.4 1189.73  5487.2 1191.75  5529.7 1194.82  5608.4 1199.01  5636.4 1201.55
#Mann=6,-1,0
  4580.9    0.14       0  4778.1    0.08       0  4876.7    0.14       0
  4975.3    0.04       0  5068.9    0.14       0  5284.8    0.08       0
#XS Ineff=2,0
       0                 5095.70    0.00 1177.94
Permanent Ineff=
       F       F
Bank Sta=4975.3,5068.9
XS Rating Curve= 0
Exp/Cntr=0.3,0.1

Type RM Length L Ch R = 1,175999,498,498,498
BEGIN DESCRIPTION:
Fisher River 352.0
END DESCRIPTION:
XS GIS Cut Line= 5
      1464343.95       991784.96      1464151.95       991894.68
      1463914.28       991873.19      1463763.45       991891.48
      1463512.10       992072.90
#Sta/Elev= 30
  4459.4 1233.19  4502.0 1226.43  4516.0 1225.74  4573.3 1219.39  4694.0 1213.62
  4717.0 1208.99  4779.7 1192.19  4793.3 1189.49  4809.4 1188.27  4832.9 1183.89
  4863.7 1181.32  4900.8 1178.27  4929.3 1174.79  4949.3 1174.88  4962.2 1173.76
  4963.6 1171.78  4970.5 1166.36  4977.8 1161.36  5022.2 1161.36  5028.5 1166.36
  5032.4 1166.40  5034.3 1169.18  5039.3 1173.32  5097.6 1174.56  5160.7 1176.39
  5190.2 1179.00  5204.0 1180.59  5261.4 1196.08  5285.7 1198.43  5381.1 1208.02
#Mann=7,-1,0
  4459.4    0.08       0  4863.7    0.14       0  4970.5    0.04       0
  5028.5    0.14       0  5097.6    0.08       0  5190.2    0.14       0
  5285.7    0.08       0
Bank Sta=4970.5,5028.5
XS Rating Curve= 0
Exp/Cntr=0.3,0.1

Type RM Length L Ch R = 1,175501,501,501,501
BEGIN DESCRIPTION:
Fisher River 351.0
END DESCRIPTION:
XS GIS Cut Line= 4
      1464321.07       991653.81      1463690.32       991416.14
      1463566.92       991475.56      1463082.43       991736.08
#Sta/Elev= 30
  4262.0 1237.92  4300.5 1231.12  4341.5 1221.39  4411.5 1201.32  4492.8 1181.52
  4558.4 1176.24  4618.7 1175.41  4730.8 1174.54  4754.1 1170.32  4827.5 1171.78
  4848.6 1169.71  4897.8 1174.05  4957.3 1174.04  4963.9 1172.68  4974.9 1166.14
  4975.3 1164.65  4977.8 1159.65  5030.5 1159.65  5030.6 1164.65  5032.4 1164.75
  5044.9 1175.22  5055.0 1173.30  5123.3 1173.28  5317.4 1172.81  5397.4 1175.84
  5462.5 1182.76  5545.1 1198.50  5570.3 1205.78  5585.7 1212.81  5623.1 1225.84
#Mann=6,-1,0
  4262.0     0.1       0  4618.7    0.14       0  4975.3    0.04       0
  5030.6    0.14       0  5123.3    0.08       0  5545.1    0.14       0
#XS Ineff=2,0
    0.00 4952.40 1174.08 5044.90    0.00 1175.22
Permanent Ineff=
       F       F
Bank Sta=4975.3,5030.6
XS Rating Curve= 0
Exp/Cntr=0.3,0.1

Type RM Length L Ch R = 1,175000,493,493,493
BEGIN DESCRIPTION:
Fisher River 350.0
END DESCRIPTION:
XS GIS Cut Line= 4
      1464380.50       991630.97      1463919.28       991402.41
      1463900.57       991032.21      1463640.03       990968.22
#Sta/Elev= 30
  4376.4 1247.11  4439.2 1236.20  4498.9 1223.47  4598.1 1196.00  4619.6 1193.47
  4625.6 1193.89  4640.5 1188.22  4667.0 1182.74  4702.2 1178.26  4744.3 1175.02
  4936.0 1172.82  4954.2 1170.95  4957.6 1169.35  4965.0 1162.85  4977.8 1157.85
  5022.2 1157.85  5027.9 1162.85  5029.6 1162.86  5034.1 1171.69  5036.9 1172.07
  5098.7 1173.33  5116.2 1167.77  5129.1 1182.66  5140.5 1184.88  5215.7 1189.12
  5279.0 1189.40  5385.8 1192.82  5441.8 1196.56  5481.2 1201.99  5530.1 1211.71
#Mann=4,-1,0
  4376.4     0.1       0  4965.0    0.04       0  5027.9    0.14       0
  5279.0    0.08       0
#XS Ineff=2,0
       0                 5067.60    0.00 1173.43
Permanent Ineff=
       F       F
Bank Sta=4965,5027.9
XS Rating Curve= 0
Exp/Cntr=0.3,0.1

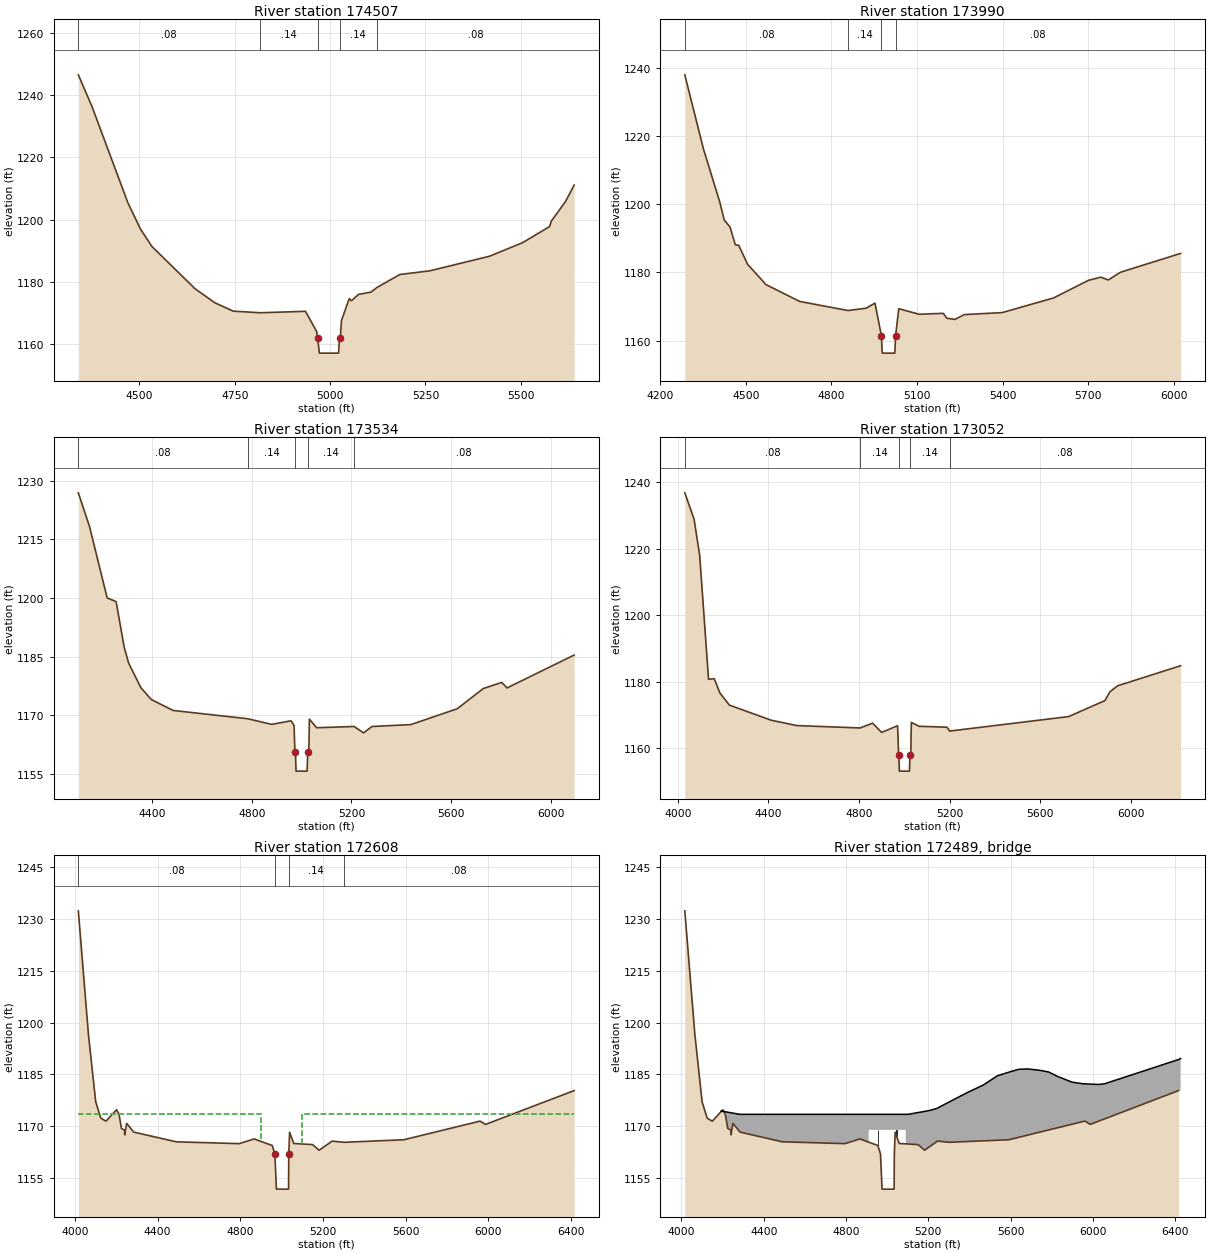
Type RM Length L Ch R = 1,174507,517,517,517
BEGIN DESCRIPTION:
Fisher River 349.0
END DESCRIPTION:
XS GIS Cut Line= 4
      1464449.03       991585.22      1464325.63       991036.78
      1464170.23       990899.67      1463640.00       990885.95
#Sta/Elev= 30
  4340.0 1246.48  4375.5 1236.39  4469.8 1205.42  4502.9 1196.95  4532.9 1191.36
  4645.8 1177.80  4697.5 1173.30  4746.2 1170.58  4816.8 1170.06  4935.5 1170.53
  4964.8 1164.01  4967.4 1161.89  4971.9 1157.10  5022.2 1157.10  5024.7 1162.10
  5026.9 1162.11  5029.9 1167.60  5050.3 1174.63  5055.9 1173.91  5074.7 1175.97
  5107.5 1176.71  5122.5 1178.15  5182.6 1182.35  5261.1 1183.52  5417.7 1188.21
  5504.4 1192.56  5575.1 1197.72  5580.1 1199.53  5616.9 1205.74  5639.8 1211.06
#Mann=5,-1,0
  4340.0    0.08       0  4816.8    0.14       0  4967.4    0.04       0
  5024.7    0.14       0  5122.5    0.08       0
Bank Sta=4967.4,5024.7
XS Rating Curve= 0
Exp/Cntr=0.3,0.1

Type RM Length L Ch R = 1,173990,456,456,456
BEGIN DESCRIPTION:
Fisher River 348.0
END DESCRIPTION:
XS GIS Cut Line= 4
      1464750.69       991548.68      1464732.41       990917.95
      1464714.13       990675.71      1464001.15       990186.68
#Sta/Elev= 30
  4285.7 1237.98  4350.9 1216.31  4408.5 1200.61  4424.0 1195.40  4444.2 1193.34
  4462.7 1188.16  4474.9 1187.94  4505.8 1182.41  4570.5 1176.43  4688.8 1171.49
  4858.2 1168.83  4921.4 1169.51  4952.6 1171.00  4975.3 1161.33  4977.8 1156.33
  5022.2 1156.33  5024.7 1161.33  5036.0 1169.36  5107.7 1167.73  5191.8 1168.01
  5204.8 1166.55  5233.0 1166.23  5266.0 1167.64  5398.6 1168.22  5578.5 1172.51
  5700.7 1177.68  5744.8 1178.62  5770.7 1177.79  5813.3 1180.06  6024.2 1185.59
#Mann=4,-1,0
  4285.7    0.08       0  4858.2    0.14       0  4975.3    0.04       0
  5024.7    0.08       0
Bank Sta=4975.3,5024.7
XS Rating Curve= 0
Exp/Cntr=0.3,0.1

Type RM Length L Ch R = 1,173534,482,482,482
BEGIN DESCRIPTION:
Fisher River 347.0
END DESCRIPTION:
XS GIS Cut Line= 3
      1465248.87       991411.54      1465093.48       990588.87
      1464056.00       990090.70
#Sta/Elev= 30
  4104.8 1226.86  4149.9 1218.20  4220.3 1200.01  4256.3 1199.05  4288.9 1187.35
  4306.4 1183.34  4355.6 1177.06  4397.1 1174.04  4485.3 1171.23  4784.0 1169.12
  4879.8 1167.68  4957.5 1168.59  4969.9 1167.40  4973.1 1160.73  4975.3 1160.73
  4977.8 1155.73  5022.2 1155.73  5024.7 1160.73  5029.0 1160.73  5031.3 1169.02
  5060.2 1166.82  5210.6 1167.14  5248.5 1165.50  5282.0 1167.14  5438.0 1167.62
  5624.1 1171.67  5728.5 1176.84  5802.6 1178.40  5823.7 1176.99  6092.9 1185.40
#Mann=5,-1,0
  4104.8    0.08       0  4784.0    0.14       0  4975.3    0.04       0
  5024.7    0.14       0  5210.6    0.08       0
Bank Sta=4975.3,5024.7
XS Rating Curve= 0
Exp/Cntr=0.3,0.1

Type RM Length L Ch R = 1,173052,444,444,444
BEGIN DESCRIPTION:
Fisher River 346.0
END DESCRIPTION:
XS GIS Cut Line= 4
      1465984.75       990844.84      1465376.86       990214.08
      1465248.88       990122.67      1464101.67       989999.27
#Sta/Elev= 30
  4031.3 1236.87  4072.2 1228.96  4097.0 1218.01  4136.0 1180.72  4161.2 1180.89
  4186.2 1176.60  4227.9 1172.95  4411.9 1168.40  4524.7 1166.78  4804.6 1166.06
  4859.5 1167.51  4899.6 1164.72  4969.7 1166.73  4971.5 1164.24  4973.8 1159.07
  4975.3 1158.06  4977.8 1153.06  5022.2 1153.06  5024.7 1158.06  5028.6 1159.06
  5029.3 1163.47  5030.8 1167.73  5064.6 1166.56  5188.0 1166.29  5199.3 1165.12
  5724.6 1169.49  5884.2 1174.29  5907.4 1177.00  5940.7 1178.76  6218.4 1184.80
#Mann=5,-1,0
  4031.3    0.08       0  4804.6    0.14       0  4975.3    0.04       0
  5024.7    0.14       0  5199.3    0.08       0
Bank Sta=4975.3,5024.7
XS Rating Curve= 0
Exp/Cntr=0.5,0.3

Type RM Length L Ch R = 1,172608,194,194,194
BEGIN DESCRIPTION:
Haystack Rd - US
END DESCRIPTION:
XS GIS Cut Line= 6
      1466399.88       990311.43      1465975.78       990179.81
      1465829.52       990080.35      1465422.93       989700.08
      1465007.56       989670.83      1464208.94       989741.04
#Sta/Elev= 30
  4016.5 1232.42  4065.2 1196.72  4100.5 1177.06  4125.0 1172.32  4150.1 1171.42
  4201.4 1174.73  4213.6 1173.35  4225.0 1169.30  4240.3 1168.82  4240.9 1167.45
  4250.3 1170.78  4285.1 1168.24  4490.3 1165.43  4795.1 1164.90  4867.1 1166.27
  4954.7 1164.36  4967.5 1161.91  4975.0 1151.71  5033.7 1151.71  5034.7 1161.78
  5038.8 1168.22  5058.6 1164.95  5150.0 1164.62  5181.8 1162.99  5244.7 1165.64
  5301.8 1165.29  5591.2 1166.03  5960.4 1171.44  5986.7 1170.48  6415.6 1180.28
#Mann=4,-1,0
  4016.5    0.08       0  4967.5    0.04       0  5034.7    0.14       0
  5301.8    0.08       0
#XS Ineff=2,0
    0.00 4900.00 1173.40 5100.00    0.00 1173.40
Permanent Ineff=
       F       F
Bank Sta=4967.5,5034.7
XS Rating Curve= 0
Exp/Cntr=0.5,0.3

Type RM Length L Ch R =3,172489,,,
BEGIN DESCRIPTION:
Haystack Rd - TOR
Structure ID: LDS_FR_12
Approximate Survey Structure
END DESCRIPTION:
Bridge Culvert--1,0,-1,-1,0
Deck Dist Width WeirC Skew NumUp NumDn MinLoCord MaxHiCord MaxSubmerge Is_Ogee
104,30,3,,24,24,,,0.95,0,1,1,,,
  4193.3  4284.1  4910.0  4910.0  5090.0  5090.0  5101.2  5203.3  5240.3  5387.5
  5466.5  5536.5  5608.6  5638.1  5681.4  5739.0  5784.9  5825.9  5899.1  5951.5
  6027.2  6055.9  6419.3  6426.0
 1174.35 1173.40 1173.40 1173.40 1173.40 1173.40 1173.40 1174.48 1175.09 1179.66
 1181.89 1184.61 1185.94 1186.44 1186.57 1186.19 1185.68 1184.44 1182.72 1182.27
 1182.06 1182.25 1189.36 1189.60
 1131.71 1131.71 1131.71 1168.90 1168.90 1131.71 1131.71 1131.71 1131.71 1131.71
 1131.71 1131.71 1131.71 1131.71 1131.71 1131.71 1131.71 1131.71 1131.71 1131.71
 1131.71 1131.71 1131.71 1131.71
  4193.3  4284.1  4910.0  4910.0  5090.0  5090.0  5101.2  5203.3  5240.3  5387.5
  5466.5  5536.5  5608.6  5638.1  5681.4  5739.0  5784.9  5825.9  5899.1  5951.5
  6027.2  6055.9  6419.3  6426.0
 1174.35 1173.40 1173.40 1173.40 1173.40 1173.40 1173.40 1174.48 1175.09 1179.66
 1181.89 1184.61 1185.94 1186.44 1186.57 1186.19 1185.68 1184.44 1182.72 1182.27
 1182.06 1182.25 1189.36 1189.60
 1131.71 1131.71 1131.71 1168.90 1168.90 1131.71 1131.71 1131.71 1131.71 1131.71
 1131.71 1131.71 1131.71 1131.71 1131.71 1131.71 1131.71 1131.71 1131.71 1131.71
 1131.71 1131.71 1131.71 1131.71
Pier Skew, UpSta & Num, DnSta & Num=,4955,2,4955,2,0,0,0,0,0
       3       3
 1164.30 1168.90
       3       3
 1163.73 1168.90
Pier Skew, UpSta & Num, DnSta & Num=,5045,2,5045,2,0,0,0,0,0
       3       3
 1166.76 1168.90
       3       3
 1163.30 1168.90
BR Coef=1,1,0,1.25,0,,,0.8,0,2,0,
WSPro=,,,, 1 ,,,, 0 ,,,, 0 ,,,,-1 ,-1 ,-1 , 0 , 0 , 0 , 0 , 0
BC Design=,,0,,0,,,,,,