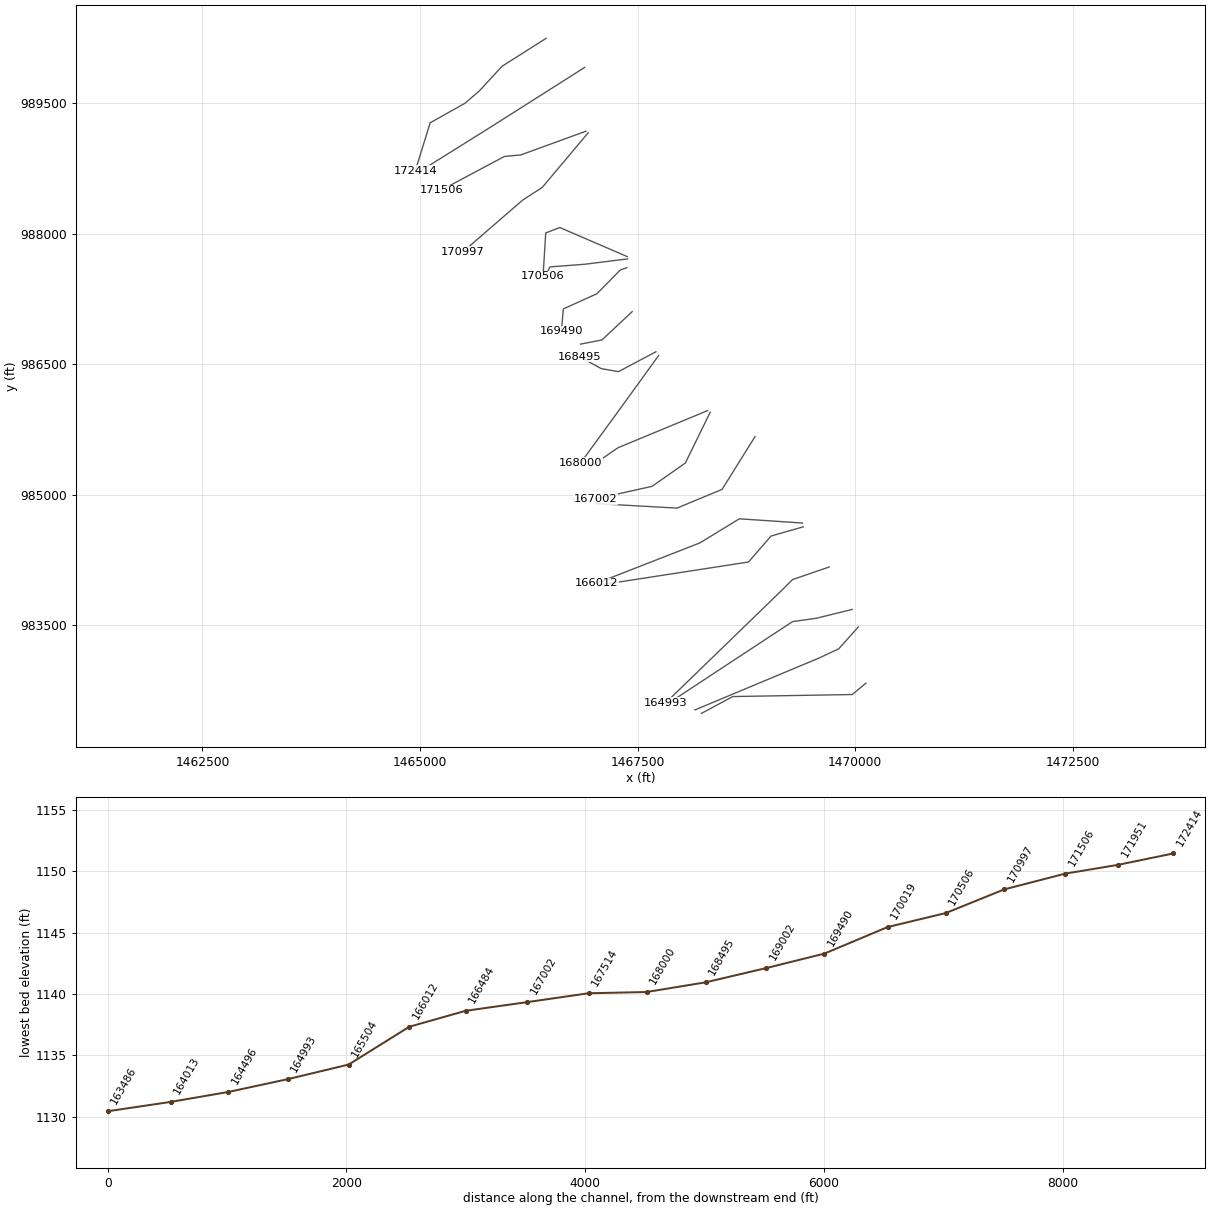
HEC-RAS study Fisher River.prj: Fisher River Limited Detail Study

--- Fisher River.g01 (geometry) --- (continued)

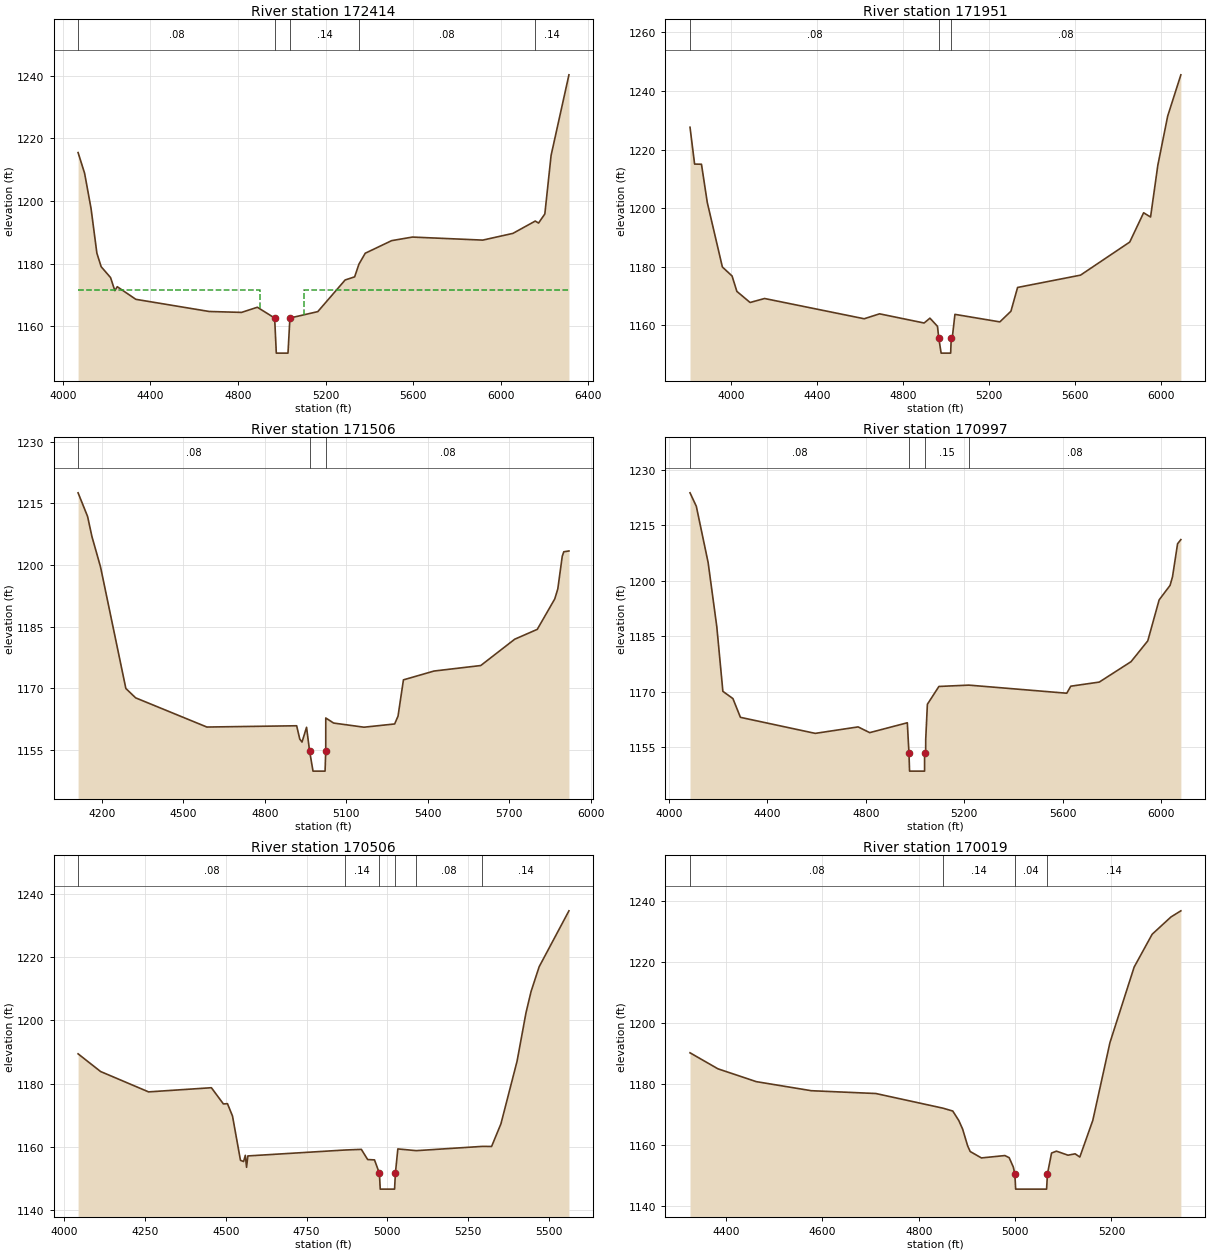
Type RM Length L Ch R = 1,172414,463,463,463
BEGIN DESCRIPTION:
Haystack Rd - DS
END DESCRIPTION:
XS GIS Cut Line= 6
      1466448.32       990245.38      1465942.83       989924.51
      1465683.51       989643.21      1465516.81       989498.99
      1465116.51       989274.00      1464945.10       988720.21
#Sta/Elev= 30
  4070.0 1215.47  4099.7 1208.88  4129.2 1197.63  4155.8 1183.37  4175.4 1179.04
  4218.3 1175.57  4237.8 1171.41  4248.8 1172.66  4333.8 1168.63  4668.7 1164.75
  4816.2 1164.46  4888.6 1166.10  4967.5 1162.66  4975.0 1151.46  5028.4 1151.46
  5037.2 1162.66  5164.5 1164.71  5289.4 1174.81  5332.7 1175.80  5352.2 1179.84
  5381.1 1183.34  5501.6 1187.36  5596.4 1188.50  5917.6 1187.53  6055.1 1189.67
  6157.4 1193.61  6172.4 1192.98  6201.1 1195.88  6229.7 1214.60  6311.1 1240.28
#Mann=5,-1,0
  4070.0    0.08       0  4967.5    0.04       0  5037.2    0.14       0
  5352.2    0.08       0  6157.4    0.14       0
#XS Ineff=2,0
    0.00 4900.00 1171.50 5100.00    0.00 1171.50
Permanent Ineff=
       F       F
Bank Sta=4967.5,5037.2
XS Rating Curve= 0
Exp/Cntr=0.5,0.3

Type RM Length L Ch R = 1,171951,445,445,445
BEGIN DESCRIPTION:
Fisher River 344.0
END DESCRIPTION:
XS GIS Cut Line= 3
      1466892.23       989911.33      1465784.60       989208.07
      1464962.65       988693.80
#Sta/Elev= 30
  3810.6 1227.61  3831.9 1215.04  3863.8 1214.99  3890.9 1201.92  3961.0 1179.92
  4006.0 1176.86  4028.4 1171.60  4089.8 1167.81  4157.2 1169.17  4620.1 1162.26
  4691.7 1163.94  4898.8 1160.81  4925.8 1162.46  4960.9 1159.67  4967.2 1155.53
  4977.8 1150.53  5022.2 1150.53  5024.7 1155.53  5029.3 1155.57  5042.0 1163.76
  5250.8 1161.19  5302.3 1164.83  5333.2 1172.94  5625.6 1177.14  5854.5 1188.43
  5919.1 1198.43  5951.3 1196.97  5985.2 1214.70  6030.9 1231.42  6092.2 1245.50
#Mann=3,-1,0
  3810.6    0.08       0  4967.2    0.04       0  5024.7    0.08       0
Bank Sta=4967.2,5024.7
XS Rating Curve= 0
Exp/Cntr=0.3,0.1

Type RM Length L Ch R = 1,171506,509,509,509
BEGIN DESCRIPTION:
Fisher River 343.0
END DESCRIPTION:
XS GIS Cut Line= 4
      1466905.42       989177.30      1466158.21       988904.79
      1465969.21       988887.21      1465243.98       988500.42
#Sta/Elev= 30
  4112.9 1217.54  4147.8 1211.81  4163.9 1206.90  4195.5 1199.52  4288.8 1169.92
  4324.9 1167.64  4587.1 1160.54  4917.6 1160.85  4929.0 1157.63  4937.3 1156.88
  4954.0 1160.48  4965.0 1154.81  4977.8 1149.81  5022.2 1149.81  5024.7 1154.81
  5024.8 1162.74  5053.7 1161.51  5165.6 1160.50  5278.4 1161.29  5290.8 1163.19
  5310.7 1172.02  5423.3 1174.17  5595.4 1175.51  5720.5 1181.92  5803.4 1184.31
  5867.8 1191.72  5879.0 1194.15  5895.4 1202.11  5901.1 1203.19  5920.0 1203.39
#Mann=3,-1,0
  4112.9    0.08       0  4965.0    0.04       0  5024.7    0.08       0
Bank Sta=4965,5024.7
XS Rating Curve= 0
Exp/Cntr=0.3,0.1

Type RM Length L Ch R = 1,170997,491,491,491
BEGIN DESCRIPTION:
Fisher River 342.0
END DESCRIPTION:
XS GIS Cut Line= 4
      1466931.80       989159.74      1466404.35       988531.19
      1466180.18       988386.14      1465494.52       987792.77
#Sta/Elev= 30
  4085.8 1223.80  4111.4 1220.16  4159.4 1204.94  4194.6 1187.60  4219.3 1170.11
  4260.1 1168.15  4290.6 1163.08  4594.5 1158.74  4768.8 1160.49  4815.9 1158.94
  4968.7 1161.61  4975.3 1153.53  4977.8 1148.53  5038.7 1148.53  5038.8 1153.53
  5043.3 1153.58  5043.4 1157.04  5050.2 1166.61  5097.0 1171.43  5218.8 1171.79
  5616.4 1169.60  5632.8 1171.50  5748.5 1172.61  5877.6 1178.13  5945.6 1183.76
  5991.8 1194.84  6036.2 1198.77  6046.1 1201.08  6066.7 1210.03  6080.1 1211.15
#Mann=4,-1,0
  4085.8    0.08       0  4975.3    0.04       0  5038.8    0.15       0
  5218.8    0.08       0
Bank Sta=4975.3,5038.8
XS Rating Curve= 0
Exp/Cntr=0.3,0.1

Type RM Length L Ch R = 1,170506,487,487,487
BEGIN DESCRIPTION:
Fisher River 341.0
END DESCRIPTION:
XS GIS Cut Line= 4
      1467380.14       987735.62      1466606.53       988069.68
      1466443.90       988008.14      1466413.14       987507.12
#Sta/Elev= 30
  4043.1 1189.44  4112.7 1183.84  4261.2 1177.39  4455.5 1178.71  4492.6 1173.58
  4505.3 1173.65  4520.8 1169.75  4545.5 1155.72  4555.1 1155.34  4560.5 1157.31
  4564.3 1153.51  4568.3 1157.11  4869.6 1158.99  4919.4 1159.19  4939.0 1155.96
  4960.1 1155.86  4975.3 1151.60  4977.8 1146.60  5022.2 1146.60  5024.7 1151.60
  5032.3 1159.33  5089.4 1158.78  5293.2 1160.13  5322.3 1160.11  5351.2 1167.27
  5401.1 1187.09  5428.7 1202.42  5444.4 1209.16  5469.4 1217.00  5561.6 1234.72
#Mann=6,-1,0
  4043.1    0.08       0  4869.6    0.14       0  4975.3    0.04       0
  5024.7    0.08       0  5089.4    0.08       0  5293.2    0.14       0
Bank Sta=4975.3,5024.7
XS Rating Curve= 0
Exp/Cntr=0.3,0.1

Type RM Length L Ch R = 1,170019,529,529,529
BEGIN DESCRIPTION:
Fisher River 340.0
END DESCRIPTION:
XS GIS Cut Line= 4
      1467384.48       987709.25      1466892.23       987647.72
      1466492.25       987616.96      1466439.52       987507.09
#Sta/Elev= 30
  4325.1 1190.12  4383.0 1184.88  4462.7 1180.67  4577.0 1177.70  4711.0 1176.78
  4850.3 1171.98  4870.6 1171.04  4883.0 1167.97  4891.1 1165.13  4901.5 1159.64
  4906.8 1157.78  4930.1 1155.68  4978.8 1156.46  4987.7 1155.76  4996.4 1152.67
  4999.5 1150.46  5001.2 1145.46  5065.4 1145.46  5067.2 1150.46  5075.7 1157.28
  5085.8 1157.90  5109.9 1156.58  5124.7 1157.02  5134.4 1155.97  5161.4 1168.01
  5197.0 1193.49  5247.2 1218.21  5284.6 1228.96  5323.7 1234.63  5344.2 1236.63
#Mann=4,-1,0
  4325.1    0.08       0  4850.3    0.14       0  4999.5    0.04       0
  5067.2    0.14       0
Bank Sta=4999.5,5067.2
XS Rating Curve= 0
Exp/Cntr=0.3,0.1

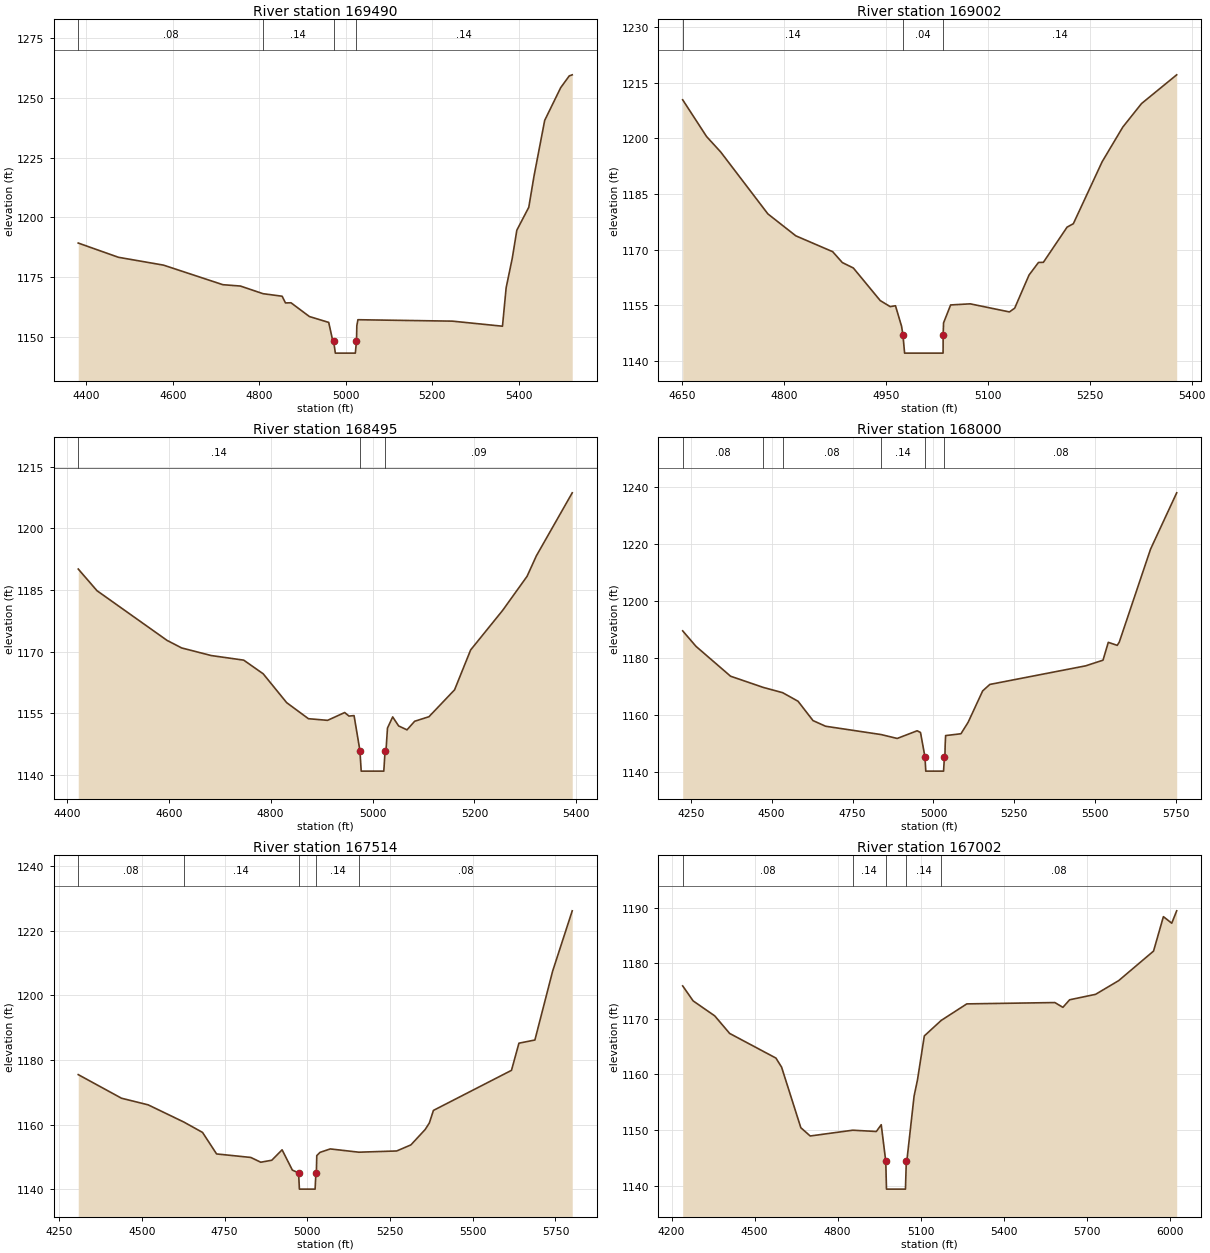
Type RM Length L Ch R = 1,169490,488,488,488
BEGIN DESCRIPTION:
Fisher River 339.0
END DESCRIPTION:
XS GIS Cut Line= 5
      1467375.74       987608.17      1467301.00       987581.79
      1467032.88       987309.28      1466646.09       987133.47
      1466624.11       986878.54
#Sta/Elev= 30
  4381.4 1189.31  4474.3 1183.36  4578.6 1180.08  4715.9 1171.90  4756.4 1171.34
  4808.6 1168.15  4852.9 1167.08  4860.6 1164.29  4873.4 1164.34  4916.0 1158.59
  4960.6 1156.14  4970.1 1148.30  4972.0 1148.30  4975.9 1143.30  5022.2 1143.30
  5024.7 1148.30  5024.9 1148.48  5025.6 1154.74  5028.1 1157.26  5246.4 1156.67
  5362.4 1154.55  5370.9 1170.65  5385.1 1183.01  5395.6 1194.68  5423.2 1204.25
  5435.2 1217.19  5460.0 1240.57  5497.0 1254.25  5516.8 1259.17  5523.7 1259.62
#Mann=4,-1,0
  4381.4    0.08       0  4808.6    0.14       0  4972.0    0.04       0
  5024.7    0.14       0
Bank Sta=4972,5024.7
XS Rating Curve= 0
Exp/Cntr=0.3,0.1

Type RM Length L Ch R = 1,169002,507,507,507
BEGIN DESCRIPTION:
Fisher River 338.0
END DESCRIPTION:
XS GIS Cut Line= 3
      1467437.25       987102.70      1467090.02       986777.44
      1466843.89       986729.10
#Sta/Elev= 30
  4651.4 1210.37  4686.5 1200.48  4707.4 1196.29  4776.7 1179.63  4817.8 1173.72
  4872.0 1169.45  4886.2 1166.52  4902.4 1165.06  4942.0 1156.27  4956.6 1154.65
  4964.4 1154.88  4973.3 1149.38  4975.3 1147.12  4977.8 1142.12  5034.4 1142.12
  5034.5 1147.12  5035.1 1150.27  5045.5 1155.10  5074.3 1155.40  5132.0 1153.22
  5139.7 1154.23  5160.8 1163.15  5174.7 1166.55  5181.9 1166.58  5216.8 1176.07
  5226.0 1176.99  5268.4 1193.70  5298.8 1203.04  5326.3 1209.36  5378.0 1217.10
#Mann=3,-1,0
  4651.4    0.14       0  4975.3    0.04       0  5034.5    0.14       0
Bank Sta=4975.3,5034.5
XS Rating Curve= 0
Exp/Cntr=0.3,0.1

Type RM Length L Ch R = 1,168495,495,495,495
BEGIN DESCRIPTION:
Fisher River 337.0
END DESCRIPTION:
XS GIS Cut Line= 4
      1467709.72       986641.17      1467279.02       986412.63
      1467081.23       986447.79      1466835.10       986584.04
#Sta/Elev= 30
  4422.3 1190.11  4459.1 1184.84  4596.7 1172.75  4625.3 1170.92  4683.3 1169.07
  4747.2 1167.95  4785.4 1164.63  4831.5 1157.61  4874.2 1153.71  4911.8 1153.31
  4945.4 1155.21  4953.8 1154.35  4963.8 1154.46  4975.3 1145.96  4977.8 1140.96
  5022.2 1140.96  5024.7 1145.96  5026.5 1145.99  5029.4 1151.43  5039.6 1154.14
  5051.3 1151.95  5067.7 1151.00  5082.8 1153.09  5110.8 1154.19  5161.1 1160.73
  5192.7 1170.44  5255.4 1180.04  5303.4 1188.33  5321.7 1193.32  5392.1 1208.64
#Mann=3,-1,0
  4422.3    0.14       0  4975.3    0.04       0  5024.7    0.09       0
Bank Sta=4975.3,5024.7
XS Rating Curve= 0
Exp/Cntr=0.3,0.1

Type RM Length L Ch R = 1,168000,486,486,486
BEGIN DESCRIPTION:
Fisher River 336.0
END DESCRIPTION:
XS GIS Cut Line= 3
      1467740.54       986597.25      1467286.50       985969.55
      1466843.92       985362.20
#Sta/Elev= 30
  4225.3 1189.45  4266.4 1184.01  4373.2 1173.52  4474.3 1169.58  4534.2 1167.73
  4581.7 1164.72  4628.0 1157.92  4666.8 1155.94  4838.7 1153.01  4888.0 1151.65
  4949.7 1154.35  4960.0 1153.75  4973.8 1145.17  4976.3 1140.17  5031.3 1140.17
  5033.9 1145.17  5035.5 1145.18  5036.2 1149.31  5037.6 1152.66  5085.0 1153.30
  5107.0 1157.30  5152.1 1168.36  5174.2 1170.63  5470.2 1177.16  5523.9 1179.15
  5540.2 1185.42  5567.8 1184.36  5574.2 1185.53  5670.7 1218.15  5751.5 1237.95
#Mann=6,-1,0
  4225.3    0.08       0  4474.3    0.14       0  4534.2    0.08       0
  4838.7    0.14       0  4973.8    0.04       0  5033.9    0.08       0
Bank Sta=4973.8,5033.9
XS Rating Curve= 0
Exp/Cntr=0.3,0.1

Type RM Length L Ch R = 1,167514,512,512,512
BEGIN DESCRIPTION:
Fisher River 335.0
END DESCRIPTION:
XS GIS Cut Line= 3
      1468303.11       985964.30      1467274.62       985537.96
      1466962.57       985322.60
#Sta/Elev= 30
  4308.1 1175.48  4438.8 1168.18  4519.4 1166.13  4627.4 1160.80  4683.6 1157.61
  4726.1 1150.95  4829.3 1149.87  4859.6 1148.39  4892.9 1149.00  4924.0 1152.23
  4955.0 1145.96  4973.8 1145.07  4976.3 1140.07  5023.7 1140.07  5026.2 1145.07
  5027.5 1145.07  5028.8 1150.43  5038.4 1151.43  5069.5 1152.50  5156.0 1151.49
  5270.3 1151.87  5313.2 1153.75  5356.3 1158.51  5368.9 1160.53  5381.2 1164.41
  5617.0 1176.80  5639.6 1185.20  5687.8 1186.18  5741.4 1207.48  5800.6 1226.13
#Mann=5,-1,0
  4308.1    0.08       0  4627.4    0.14       0  4973.8    0.04       0
  5026.2    0.14       0  5156.0    0.08       0
Bank Sta=4973.8,5026.2
XS Rating Curve= 0
Exp/Cntr=0.3,0.1

Type RM Length L Ch R = 1,167002,518,518,518
BEGIN DESCRIPTION:
Fisher River 334.0
END DESCRIPTION:
XS GIS Cut Line= 4
      1468333.92       985946.77      1468048.20       985362.14
      1467665.81       985094.03      1467015.31       984948.98
#Sta/Elev= 30
  4240.3 1175.95  4278.0 1173.25  4356.1 1170.55  4409.9 1167.39  4577.1 1162.95
  4597.4 1161.33  4667.0 1150.41  4700.9 1148.92  4854.4 1149.96  4939.7 1149.73
  4957.4 1150.95  4973.8 1144.35  4976.3 1139.35  5044.9 1139.35  5047.9 1144.35
  5049.7 1144.35  5076.0 1156.09  5088.3 1159.02  5113.0 1166.94  5173.9 1169.73
  5266.4 1172.71  5584.5 1172.95  5613.6 1172.09  5637.8 1173.45  5731.5 1174.43
  5815.0 1176.90  5940.9 1182.22  5976.5 1188.42  6006.6 1187.24  6024.5 1189.47
#Mann=5,-1,0
  4240.3    0.08       0  4854.4    0.14       0  4973.8    0.04       0
  5047.9    0.14       0  5173.9    0.08       0
Bank Sta=4973.8,5047.9
XS Rating Curve= 0
Exp/Cntr=0.3,0.1

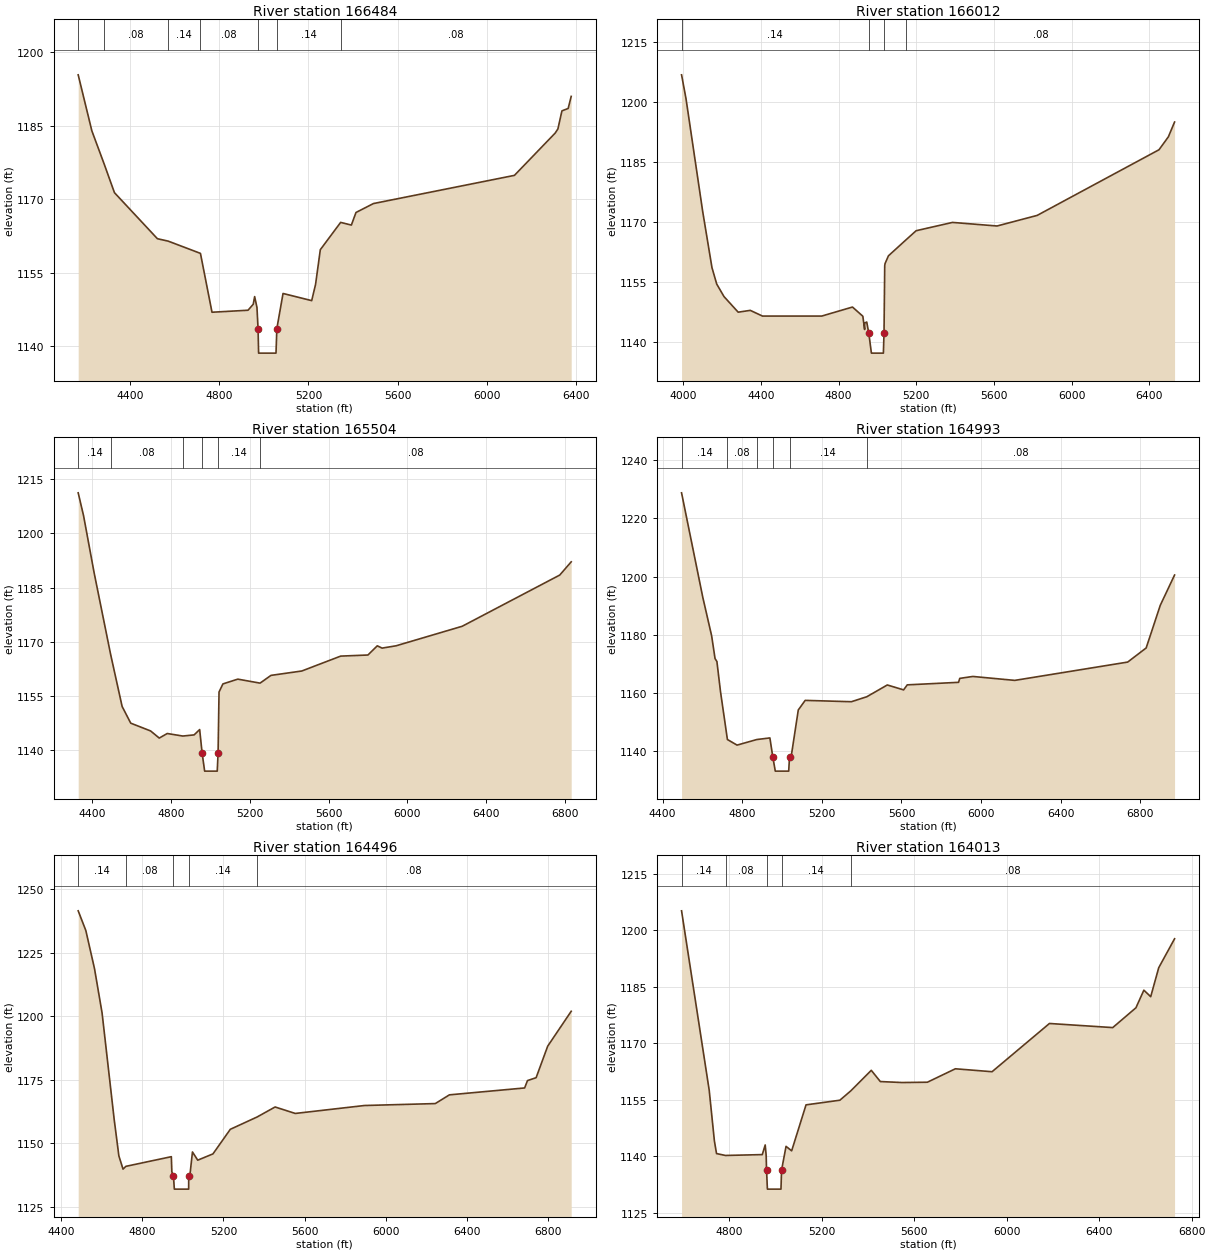
Type RM Length L Ch R = 1,166484,472,472,472
BEGIN DESCRIPTION:
Fisher River 333.0
END DESCRIPTION:
XS GIS Cut Line= 4
      1468848.13       985665.39      1468470.16       985058.87
      1467951.51       984843.49      1467015.34       984896.24
#Sta/Elev= 30
  4166.1 1195.41  4227.5 1183.98  4281.6 1177.36  4329.0 1171.37  4521.8 1161.98
  4570.0 1161.49  4715.1 1158.99  4767.0 1146.98  4928.8 1147.39  4952.2 1148.61
  4958.5 1150.17  4968.9 1147.96  4973.8 1143.64  4976.3 1138.64  5054.4 1138.64
  5058.2 1143.64  5086.0 1150.81  5214.7 1149.35  5232.1 1152.67  5253.4 1159.74
  5344.7 1165.31  5392.8 1164.76  5413.6 1167.33  5491.9 1169.15  6125.1 1174.90
  6307.9 1183.52  6320.3 1184.37  6338.4 1188.06  6366.4 1188.55  6380.0 1191.01
#Mann=7,-1,0
  4166.1    0.14       0  4281.6    0.08       0  4570.0    0.14       0
  4715.1    0.08       0  4973.8    0.04       0  5058.2    0.14       0
  5344.7    0.08       0
Bank Sta=4973.8,5058.2
XS Rating Curve= 0
Exp/Cntr=0.3,0.1

Type RM Length L Ch R = 1,166012,508,508,508
BEGIN DESCRIPTION:
Fisher River 332.0
END DESCRIPTION:
XS GIS Cut Line= 4
      1469393.21       984672.07      1468667.95       984720.42
      1468215.23       984443.52      1467024.07       983977.60
#Sta/Elev= 30
  3992.4 1206.73  4015.2 1200.81  4101.1 1172.67  4148.9 1158.65  4173.3 1154.57
  4210.8 1151.44  4283.7 1147.55  4345.9 1148.00  4409.0 1146.58  4713.6 1146.58
  4871.8 1148.83  4925.1 1146.54  4934.3 1143.23  4934.5 1144.82  4945.1 1145.10
  4955.7 1142.34  4969.2 1137.34  5030.8 1137.34  5034.1 1142.34  5037.7 1159.13
  5039.6 1159.68  5056.8 1161.60  5148.4 1165.64  5199.3 1167.86  5386.3 1169.93
  5615.7 1169.04  5822.1 1171.68  6449.0 1188.05  6497.2 1191.28  6529.0 1194.96
#Mann=4,-1,0
  3992.4    0.14       0  4955.7    0.04       0  5034.1    0.14       0
  5148.4    0.08       0
Bank Sta=4955.7,5034.1
XS Rating Curve= 0
Exp/Cntr=0.3,0.1

Type RM Length L Ch R = 1,165504,511,511,511
BEGIN DESCRIPTION:
Fisher River 331.0
END DESCRIPTION:
XS GIS Cut Line= 4
      1469401.96       984628.12      1469032.76       984522.63
      1468773.44       984223.75      1467068.08       983960.04
#Sta/Elev= 30
  4327.6 1211.20  4354.9 1204.88  4408.8 1189.04  4492.4 1166.54  4550.8 1152.15
  4594.6 1147.52  4695.5 1145.37  4739.6 1143.40  4780.2 1144.66  4859.3 1143.96
  4916.7 1144.28  4944.9 1145.75  4957.4 1139.26  4970.2 1134.26  5034.2 1134.26
  5038.5 1139.26  5043.3 1156.12  5063.0 1158.37  5138.6 1159.69  5251.8 1158.59
  5307.4 1160.73  5463.9 1161.94  5661.6 1166.06  5799.9 1166.36  5847.4 1168.90
  5872.1 1168.27  5943.2 1168.91  6279.1 1174.31  6774.8 1188.47  6832.9 1192.12
#Mann=6,-1,0
  4327.6    0.14       0  4492.4    0.08       0  4859.3    0.14       0
  4957.4    0.04       0  5038.5    0.14       0  5251.8    0.08       0
Bank Sta=4957.4,5038.5
XS Rating Curve= 0
Exp/Cntr=0.3,0.1

Type RM Length L Ch R = 1,164993,497,497,497
BEGIN DESCRIPTION:
Fisher River 330.0
END DESCRIPTION:
XS GIS Cut Line= 4
      1469700.88       984166.62      1469278.90       984021.56
      1469151.44       983894.10      1467824.07       982606.29
#Sta/Elev= 30
  4495.7 1228.82  4602.5 1192.82  4646.8 1179.62  4663.9 1171.78  4673.2 1170.79
  4691.4 1160.36  4726.0 1143.95  4774.4 1142.02  4873.6 1143.94  4939.3 1144.49
  4953.7 1138.07  4966.4 1133.07  5033.8 1133.07  5038.0 1138.07  5048.5 1139.09
  5081.9 1154.11  5116.6 1157.41  5348.7 1156.95  5425.9 1158.66  5529.0 1162.71
  5610.9 1161.02  5629.1 1162.75  5886.8 1163.62  5892.9 1164.98  5958.5 1165.64
  6169.2 1164.29  6736.2 1170.59  6829.0 1175.45  6899.8 1190.12  6971.6 1200.54
#Mann=6,-1,0
  4495.7    0.14       0  4726.0    0.08       0  4873.6    0.14       0
  4953.7    0.04       0  5038.0    0.14       0  5425.9    0.08       0
Bank Sta=4953.7,5038
XS Rating Curve= 0
Exp/Cntr=0.3,0.1

Type RM Length L Ch R = 1,164496,483,483,483
BEGIN DESCRIPTION:
Fisher River 329.0
END DESCRIPTION:
XS GIS Cut Line= 4
      1469964.61       983678.74      1469555.81       983577.63
      1469278.90       983538.08      1467837.26       982588.70
#Sta/Elev= 30
  4485.2 1241.40  4522.8 1233.67  4565.6 1218.65  4602.7 1201.32  4662.5 1159.36
  4685.5 1145.08  4706.0 1139.88  4719.8 1140.98  4943.8 1144.78  4946.2 1138.87
  4954.3 1137.03  4958.5 1132.03  5029.1 1132.03  5029.2 1137.03  5034.6 1137.06
  5047.7 1146.63  5073.7 1143.41  5148.7 1145.88  5234.1 1155.54  5366.0 1160.38
  5454.6 1164.31  5553.8 1161.77  5894.4 1164.89  6243.1 1165.65  6312.7 1169.08
  6682.9 1171.79  6697.1 1174.69  6739.5 1175.82  6796.5 1188.21  6912.2 1201.92
#Mann=5,-1,0
  4485.2    0.14       0  4719.8    0.08       0  4954.3    0.04       0
  5029.2    0.14       0  5366.0    0.08       0
Bank Sta=4954.3,5029.2
XS Rating Curve= 0
Exp/Cntr=0.3,0.1

Type RM Length L Ch R = 1,164013,527,527,527
BEGIN DESCRIPTION:
Fisher River 328.0
END DESCRIPTION:
XS GIS Cut Line= 4
      1470034.88       983476.53      1469810.74       983226.01
      1469586.57       983120.52      1468158.10       982522.76
#Sta/Elev= 30
  4593.7 1205.13  4713.3 1157.48  4735.7 1144.04  4745.0 1140.66  4783.8 1140.16
  4942.9 1140.39  4955.5 1142.95  4959.7 1140.11  4961.3 1136.22  4965.0 1131.22
  5023.7 1131.22  5026.2 1136.22  5045.6 1142.58  5069.9 1141.39  5132.1 1153.60
  5278.4 1154.83  5326.1 1157.34  5414.3 1162.77  5453.4 1159.79  5546.6 1159.53
  5656.9 1159.61  5778.0 1163.18  5936.7 1162.40  6184.9 1175.21  6458.7 1174.12
  6559.0 1179.38  6593.3 1184.06  6622.9 1182.33  6657.6 1190.02  6726.1 1197.71
#Mann=5,-1,0
  4593.7    0.14       0  4783.8    0.08       0  4961.3    0.04       0
  5026.2    0.14       0  5326.1    0.08       0
Bank Sta=4961.3,5026.2
XS Rating Curve= 0
Exp/Cntr=0.3,0.1

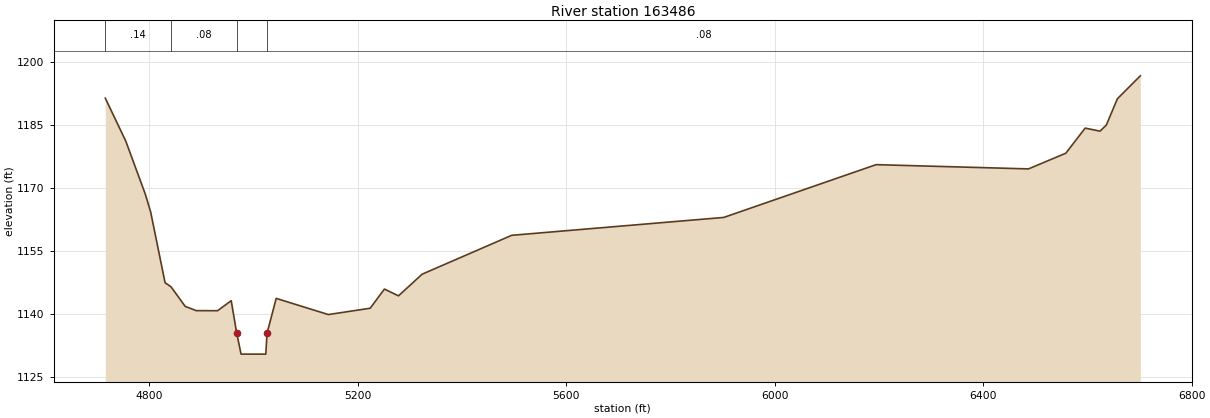
Type RM Length L Ch R = 1,163486,494,494,494
BEGIN DESCRIPTION:
Fisher River 327.0
END DESCRIPTION:
XS GIS Cut Line= 4
      1470122.79       982830.41      1469964.57       982699.88
      1468593.23       982676.59      1468232.79       982483.19
#Sta/Elev= 30
  4715.8 1191.32  4755.1 1181.11  4792.7 1168.46  4802.9 1164.23  4830.5 1147.44
  4841.9 1146.47  4869.1 1141.81  4890.4 1140.80  4931.2 1140.78  4957.4 1143.17
  4967.9 1135.46  4976.3 1130.46  5023.7 1130.46  5026.2 1135.46  5043.7 1143.71
  5143.7 1139.87  5224.0 1141.37  5251.3 1145.93  5278.3 1144.32  5323.7 1149.47
  5495.5 1158.71  5902.3 1162.96  6194.6 1175.51  6486.9 1174.50  6558.6 1178.23
  6595.7 1184.20  6624.2 1183.47  6636.3 1184.93  6657.5 1191.17  6701.5 1196.63
#Mann=4,-1,0
  4715.8    0.14       0  4841.9    0.08       0  4967.9    0.04       0
  5026.2    0.08       0
Bank Sta=4967.9,5026.2
XS Rating Curve= 0
Exp/Cntr=0.3,0.1