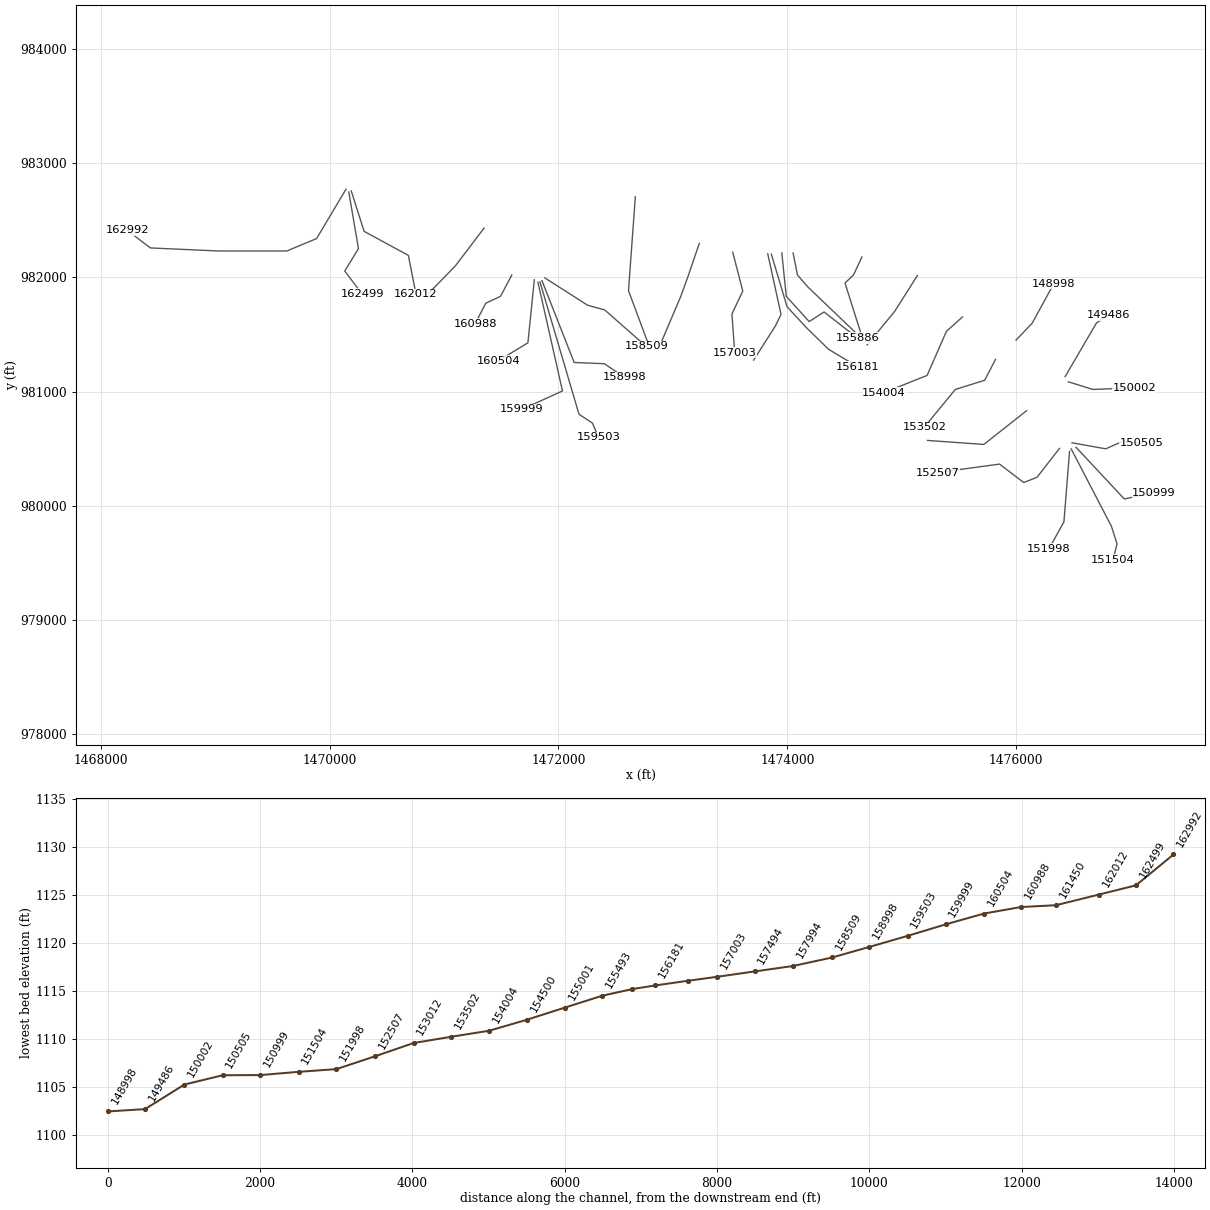
HEC-RAS study Fisher River.prj: Fisher River Limited Detail Study

--- Fisher River.g01 (geometry) --- (continued)

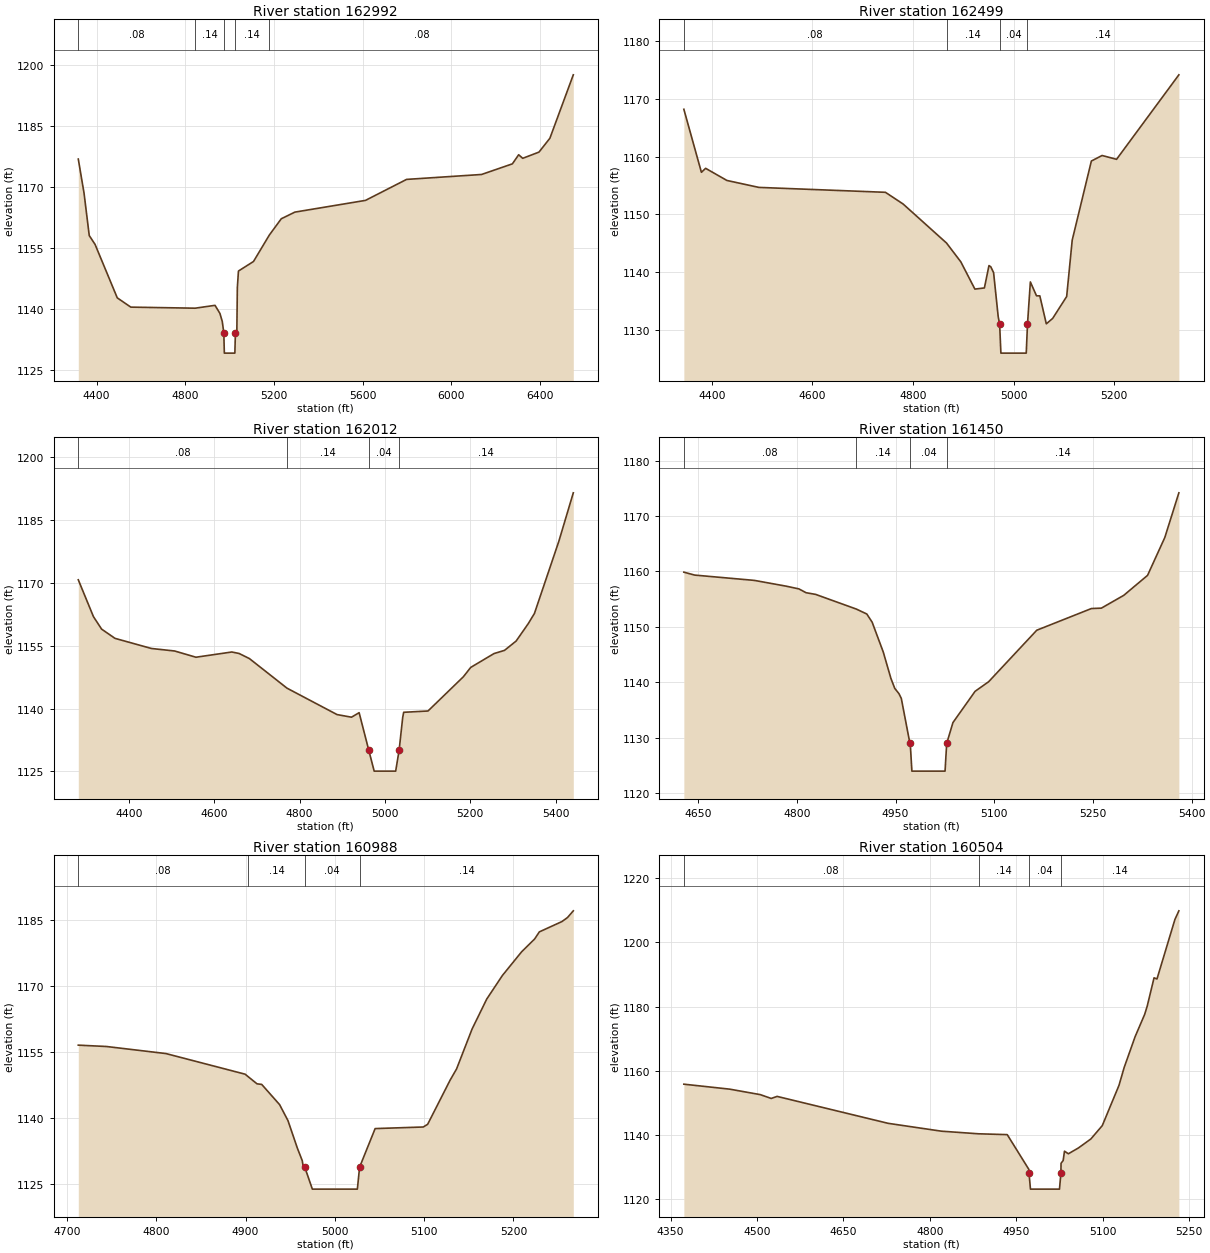
Type RM Length L Ch R = 1,162992,493,493,493
BEGIN DESCRIPTION:
Fisher River 326.0
END DESCRIPTION:
XS GIS Cut Line= 6
      1470143.92       982773.75      1469887.22       982341.22
      1469627.01       982232.22      1469029.24       982232.22
      1468434.99       982259.03      1468232.78       982412.89
#Sta/Elev= 30
  4317.8 1176.87  4343.8 1168.48  4367.2 1158.09  4393.5 1155.91  4493.5 1142.80
  4554.5 1140.52  4844.7 1140.26  4934.3 1140.96  4956.3 1138.98  4967.0 1137.00
  4973.8 1134.23  4976.3 1129.23  5023.7 1129.23  5026.2 1134.23  5032.6 1134.30
  5034.9 1145.27  5039.9 1149.38  5107.7 1151.72  5179.1 1158.21  5233.0 1162.21
  5294.2 1163.84  5612.7 1166.72  5797.9 1171.87  6135.9 1173.08  6275.0 1175.69
  6303.2 1177.92  6321.6 1177.05  6394.8 1178.57  6444.0 1181.97  6549.6 1197.54
#Mann=5,-1,0
  4317.8    0.08       0  4844.7    0.14       0  4973.8    0.04       0
  5026.2    0.14       0  5179.1    0.08       0
Bank Sta=4973.8,5026.2
XS Rating Curve= 0
Exp/Cntr=0.3,0.1

Type RM Length L Ch R = 1,162499,487,487,487
BEGIN DESCRIPTION:
Fisher River 325.0
END DESCRIPTION:
XS GIS Cut Line= 4
      1470168.52       982749.10      1470252.91       982253.32
      1470133.36       982056.41      1470284.53       981856.01
#Sta/Elev= 30
  4344.4 1168.21  4379.3 1157.30  4387.7 1157.99  4430.0 1155.89  4493.5 1154.69
  4745.2 1153.84  4780.3 1151.82  4866.7 1145.06  4895.1 1141.81  4923.1 1137.09
  4942.0 1137.29  4951.1 1141.16  4954.7 1140.95  4960.3 1139.94  4969.4 1132.35
  4972.3 1131.01  4974.8 1126.01  5025.2 1126.01  5027.7 1131.01  5033.4 1138.33
  5045.6 1135.93  5052.2 1135.92  5065.1 1131.08  5077.7 1132.01  5105.6 1135.81
  5116.6 1145.56  5154.7 1159.25  5176.0 1160.21  5204.8 1159.55  5328.7 1174.17
#Mann=4,-1,0
  4344.4    0.08       0  4866.7    0.14       0  4972.3    0.04       0
  5027.7    0.14       0
Bank Sta=4972.3,5027.7
XS Rating Curve= 0
Exp/Cntr=0.3,0.1

Type RM Length L Ch R = 1,162012,562,562,562
BEGIN DESCRIPTION:
Fisher River 324.0
END DESCRIPTION:
XS GIS Cut Line= 4
      1470189.61       982759.67      1470302.14       982404.52
      1470688.93       982193.54      1470755.74       981852.47
#Sta/Elev= 30
  4281.0 1170.74  4316.6 1161.93  4335.7 1158.96  4367.0 1156.76  4452.4 1154.34
  4506.9 1153.74  4556.8 1152.25  4641.1 1153.50  4658.1 1153.14  4682.2 1151.93
  4770.4 1144.86  4887.8 1138.55  4921.6 1137.93  4939.5 1139.01  4962.1 1130.05
  4974.8 1125.05  5025.2 1125.05  5033.3 1130.05  5041.7 1137.88  5044.0 1139.10
  5101.0 1139.41  5183.9 1147.58  5201.2 1149.82  5255.7 1153.12  5280.4 1153.89
  5307.6 1156.11  5335.9 1160.24  5350.5 1162.69  5407.7 1179.91  5441.7 1191.51
#Mann=4,-1,0
  4281.0    0.08       0  4770.4    0.14       0  4962.1    0.04       0
  5033.3    0.14       0
Bank Sta=4962.1,5033.3
XS Rating Curve= 0
Exp/Cntr=0.3,0.1

Type RM Length L Ch R = 1,161450,462,462,462
BEGIN DESCRIPTION:
Fisher River 323.0
END DESCRIPTION:
XS GIS Cut Line= 3
      1471349.97       982432.63      1471100.33       982102.12
      1470864.73       981859.48
#Sta/Elev= 30
  4628.2 1159.88  4644.7 1159.35  4735.5 1158.39  4784.6 1157.33  4803.2 1156.85
  4813.9 1156.17  4828.6 1155.86  4890.4 1153.21  4906.3 1152.32  4914.4 1150.84
  4931.3 1145.45  4942.9 1140.69  4948.8 1138.88  4955.2 1137.92  4958.7 1137.08
  4971.8 1128.95  4972.3 1128.94  4974.8 1123.94  5025.2 1123.94  5027.7 1128.94
  5037.2 1132.71  5070.9 1138.36  5091.4 1140.08  5164.6 1149.39  5247.7 1153.31
  5262.8 1153.38  5296.8 1155.69  5333.0 1159.30  5359.2 1166.13  5380.6 1174.21
#Mann=4,-1,0
  4628.2    0.08       0  4890.4    0.14       0  4972.3    0.04       0
  5027.7    0.14       0
Bank Sta=4972.3,5027.7
XS Rating Curve= 0
Exp/Cntr=0.3,0.1

Type RM Length L Ch R = 1,160988,484,484,484
BEGIN DESCRIPTION:
Fisher River 322.0
END DESCRIPTION:
XS GIS Cut Line= 4
      1471592.63       982021.27      1471494.15       981834.88
      1471365.52       981774.48      1471272.64       981595.80
#Sta/Elev= 30
  4712.7 1156.52  4744.3 1156.21  4810.9 1154.60  4899.5 1149.91  4903.0 1149.33
  4912.8 1147.72  4918.1 1147.58  4938.1 1142.99  4947.5 1139.34  4958.1 1133.03
  4963.5 1130.23  4964.7 1128.75  4966.3 1128.75  4974.8 1123.75  5025.2 1123.75
  5027.7 1128.75  5045.1 1137.53  5099.0 1137.89  5103.9 1138.50  5129.0 1148.53
  5136.3 1151.11  5153.7 1160.21  5170.1 1167.02  5187.6 1172.37  5209.1 1177.76
  5223.7 1180.68  5229.0 1182.30  5254.3 1184.65  5260.5 1185.56  5267.0 1187.09
#Mann=4,-1,0
  4712.7    0.08       0  4903.0    0.14       0  4966.3    0.04       0
  5027.7    0.14       0
Bank Sta=4966.3,5027.7
XS Rating Curve= 0
Exp/Cntr=0.3,0.1

Type RM Length L Ch R = 1,160504,505,505,505
BEGIN DESCRIPTION:
Fisher River 321.0
END DESCRIPTION:
XS GIS Cut Line= 3
      1471789.52       981979.05      1471733.26       981426.99
      1471473.02       981268.74
#Sta/Elev= 30
  4373.0 1155.79  4452.6 1154.24  4505.8 1152.53  4524.7 1151.34  4534.9 1151.98
  4727.8 1143.58  4820.1 1141.14  4884.7 1140.32  4934.5 1140.06  4971.9 1129.26
  4972.3 1128.07  4974.8 1123.07  5025.2 1123.07  5027.7 1128.07  5027.9 1131.11
  5031.6 1131.99  5033.9 1134.90  5040.6 1134.09  5058.2 1135.92  5079.7 1138.71
  5099.5 1142.87  5128.5 1155.41  5137.4 1160.93  5156.4 1170.55  5173.1 1177.55
  5177.5 1180.10  5189.4 1188.95  5194.5 1188.60  5225.6 1207.13  5232.5 1209.84
#Mann=4,-1,0
  4373.0    0.08       0  4884.7    0.14       0  4972.3    0.04       0
  5027.7    0.14       0
Bank Sta=4972.3,5027.7
XS Rating Curve= 0
Exp/Cntr=0.3,0.1

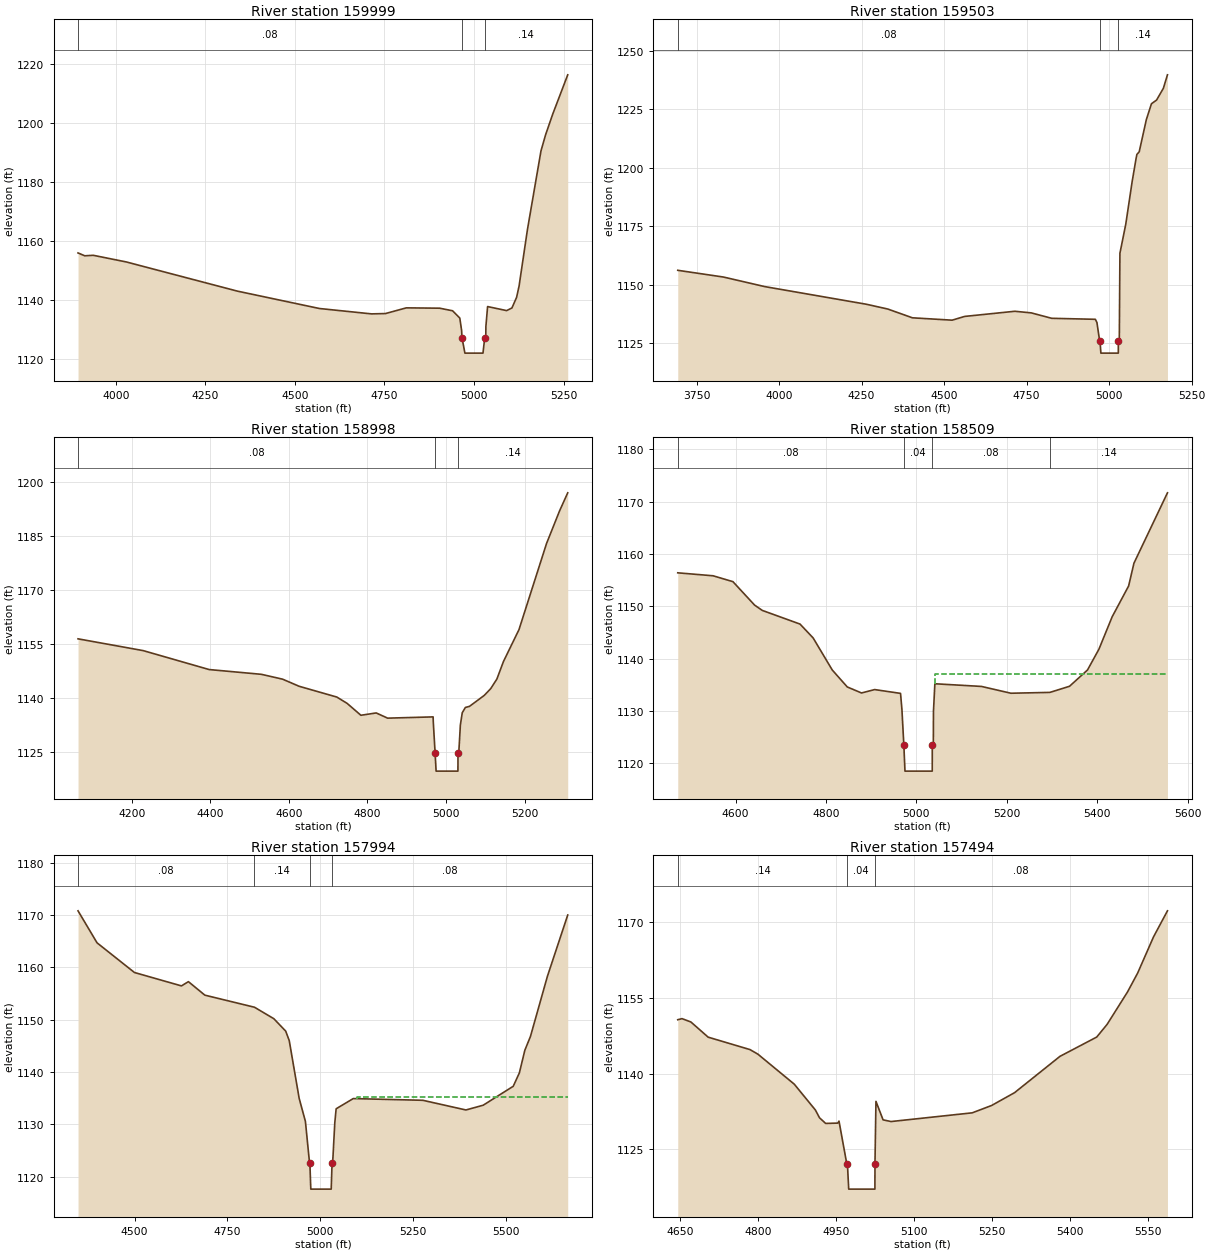
Type RM Length L Ch R = 1,159999,496,496,496
BEGIN DESCRIPTION:
Fisher River 320.0
END DESCRIPTION:
XS GIS Cut Line= 3
      1471821.16       981957.98      1472035.66       981005.04
      1471680.54       980843.30
#Sta/Elev= 30
  3894.8 1155.87  3913.6 1154.90  3937.3 1155.07  4029.2 1152.83  4339.5 1142.94
  4568.7 1137.05  4714.2 1135.23  4753.0 1135.34  4811.2 1137.27  4904.2 1137.16
  4940.4 1136.28  4960.5 1133.81  4965.6 1129.60  4966.7 1126.95  4967.0 1126.94
  4974.8 1121.94  5025.2 1121.94  5029.9 1126.94  5033.1 1127.00  5033.3 1130.89
  5038.1 1137.71  5091.2 1136.34  5106.1 1137.24  5119.1 1140.84  5126.0 1144.67
  5149.4 1163.83  5187.1 1190.40  5199.9 1195.84  5219.9 1202.88  5261.8 1216.19
#Mann=3,-1,0
  3894.8    0.08       0  4967.0    0.04       0  5029.9    0.14       0
Bank Sta=4967,5029.9
XS Rating Curve= 0
Exp/Cntr=0.3,0.1

Type RM Length L Ch R = 1,159503,505,505,505
BEGIN DESCRIPTION:
Fisher River 319.0
END DESCRIPTION:
XS GIS Cut Line= 4
      1471838.75       981961.47      1472179.83       980801.10
      1472297.86       980722.82      1472348.62       980600.64
#Sta/Elev= 30
  3693.1 1156.19  3831.8 1153.30  3956.4 1149.22  4264.6 1141.66  4329.2 1139.62
  4404.0 1135.86  4524.2 1134.85  4562.0 1136.45  4714.1 1138.66  4763.9 1137.97
  4825.8 1135.65  4958.1 1135.22  4962.9 1133.82  4971.3 1125.75  4972.3 1125.75
  4974.8 1120.75  5027.6 1120.75  5027.7 1125.75  5030.6 1125.83  5032.5 1163.49
  5050.2 1175.90  5069.3 1193.94  5081.6 1204.16  5083.9 1205.76  5090.9 1206.89
  5112.5 1220.65  5128.0 1227.45  5143.6 1229.04  5164.1 1234.07  5176.5 1239.83
#Mann=3,-1,0
  3693.1    0.08       0  4972.3    0.04       0  5027.7    0.14       0
#XS Ineff=2,0
    0.00 4714.10 1138.66               0
Permanent Ineff=
       F       F
Bank Sta=4972.3,5027.7
XS Rating Curve= 0
Exp/Cntr=0.3,0.1

Type RM Length L Ch R = 1,158998,489,489,489
BEGIN DESCRIPTION:
Fisher River 318.0
END DESCRIPTION:
XS GIS Cut Line= 4
      1471856.32       981972.04      1472137.63       981254.70
      1472401.35       981244.15      1472577.18       981124.58
#Sta/Elev= 30
  4062.9 1156.42  4228.9 1153.14  4396.8 1147.87  4529.9 1146.54  4583.9 1145.19
  4626.0 1143.21  4722.0 1140.21  4748.1 1138.46  4783.3 1135.14  4822.3 1135.79
  4851.3 1134.34  4967.2 1134.69  4967.6 1133.31  4972.3 1124.59  4974.8 1119.59
  5030.4 1119.59  5030.5 1124.59  5032.5 1124.60  5036.6 1132.43  5041.4 1135.84
  5049.3 1137.31  5059.8 1137.62  5097.4 1140.67  5113.9 1142.56  5129.6 1145.23
  5146.3 1150.10  5185.8 1158.97  5256.0 1182.95  5289.2 1192.04  5310.0 1197.07
#Mann=3,-1,0
  4062.9    0.08       0  4972.3    0.04       0  5030.5    0.14       0
Bank Sta=4972.3,5030.5
XS Rating Curve= 0
Exp/Cntr=0.3,0.1

Type RM Length L Ch R = 1,158509,515,515,515
BEGIN DESCRIPTION:
Fisher River 317.0
END DESCRIPTION:
XS GIS Cut Line= 4
      1471880.97       981996.61      1472253.67       981757.52
      1472404.87       981715.33      1472767.01       981395.38
#Sta/Elev= 30
  4472.3 1156.40  4550.5 1155.83  4594.3 1154.71  4642.2 1150.23  4659.3 1149.21
  4742.7 1146.60  4771.7 1143.95  4814.0 1137.82  4847.2 1134.58  4878.7 1133.43
  4907.8 1134.08  4965.0 1133.35  4968.1 1130.21  4972.3 1123.49  4974.8 1118.49
  5035.1 1118.49  5035.2 1123.49  5037.5 1123.52  5037.8 1129.90  5040.9 1135.19
  5144.0 1134.68  5209.1 1133.38  5295.3 1133.54  5338.7 1134.71  5378.5 1137.83
  5403.7 1141.79  5433.1 1148.01  5469.4 1153.88  5481.2 1158.24  5555.3 1171.69
#Mann=4,-1,0
  4472.3    0.08       0  4972.3    0.04       0  5035.2    0.08       0
  5295.3    0.14       0
#XS Ineff=2,0
       0                 5040.90    0.00 1137.00
Permanent Ineff=
       F       F
Bank Sta=4972.3,5035.2
XS Rating Curve= 0
Exp/Cntr=0.3,0.1

Type RM Length L Ch R = 1,157994,500,500,500
BEGIN DESCRIPTION:
Fisher River 316.0
END DESCRIPTION:
XS GIS Cut Line= 3
      1472672.11       982706.92      1472612.33       981884.11
      1472784.63       981419.94
#Sta/Elev= 30
  4347.3 1170.80  4398.6 1164.68  4499.4 1159.01  4626.1 1156.45  4644.9 1157.26
  4689.2 1154.68  4823.0 1152.37  4875.1 1150.18  4907.1 1147.81  4916.7 1145.99
  4943.5 1134.93  4960.3 1130.54  4971.4 1122.60  4972.3 1122.60  4974.8 1117.60
  5029.8 1117.60  5032.1 1122.60  5033.7 1122.60  5039.5 1130.30  5043.1 1132.96
  5089.3 1134.91  5276.9 1134.58  5393.0 1132.73  5439.5 1133.64  5520.5 1137.26
  5537.0 1139.81  5551.8 1144.15  5566.9 1146.78  5612.8 1158.32  5667.4 1170.00
#Mann=4,-1,0
  4347.3    0.08       0  4823.0    0.14       0  4972.3    0.04       0
  5032.1    0.08       0
#XS Ineff=2,0
       0                 5100.20    0.00 1135.23
Permanent Ineff=
       F       F
Bank Sta=4972.3,5032.1
XS Rating Curve= 0
Exp/Cntr=0.3,0.1

Type RM Length L Ch R = 1,157494,491,491,491
BEGIN DESCRIPTION:
Fisher River 315.0
END DESCRIPTION:
XS GIS Cut Line= 4
      1473231.18       982298.99      1473132.74       982010.69
      1473069.44       981834.88      1472893.64       981419.99
#Sta/Elev= 30
  4645.9 1150.68  4654.0 1150.90  4671.1 1150.24  4704.4 1147.22  4784.9 1144.75
  4800.1 1143.84  4870.0 1137.89  4910.7 1132.75  4918.6 1131.21  4930.4 1130.09
  4953.7 1130.15  4956.1 1130.55  4971.1 1122.06  4972.3 1122.04  4974.8 1117.04
  5025.2 1117.04  5025.3 1122.04  5027.2 1134.47  5040.9 1130.80  5056.1 1130.46
  5212.4 1132.19  5249.7 1133.65  5293.9 1136.20  5381.2 1143.41  5451.9 1147.24
  5471.9 1149.76  5511.1 1156.19  5530.8 1159.98  5561.1 1167.12  5588.0 1172.31
#Mann=3,-1,0
  4645.9    0.14       0  4972.3    0.04       0  5025.3    0.08       0
Bank Sta=4972.3,5025.3
XS Rating Curve= 0
Exp/Cntr=0.3,0.1

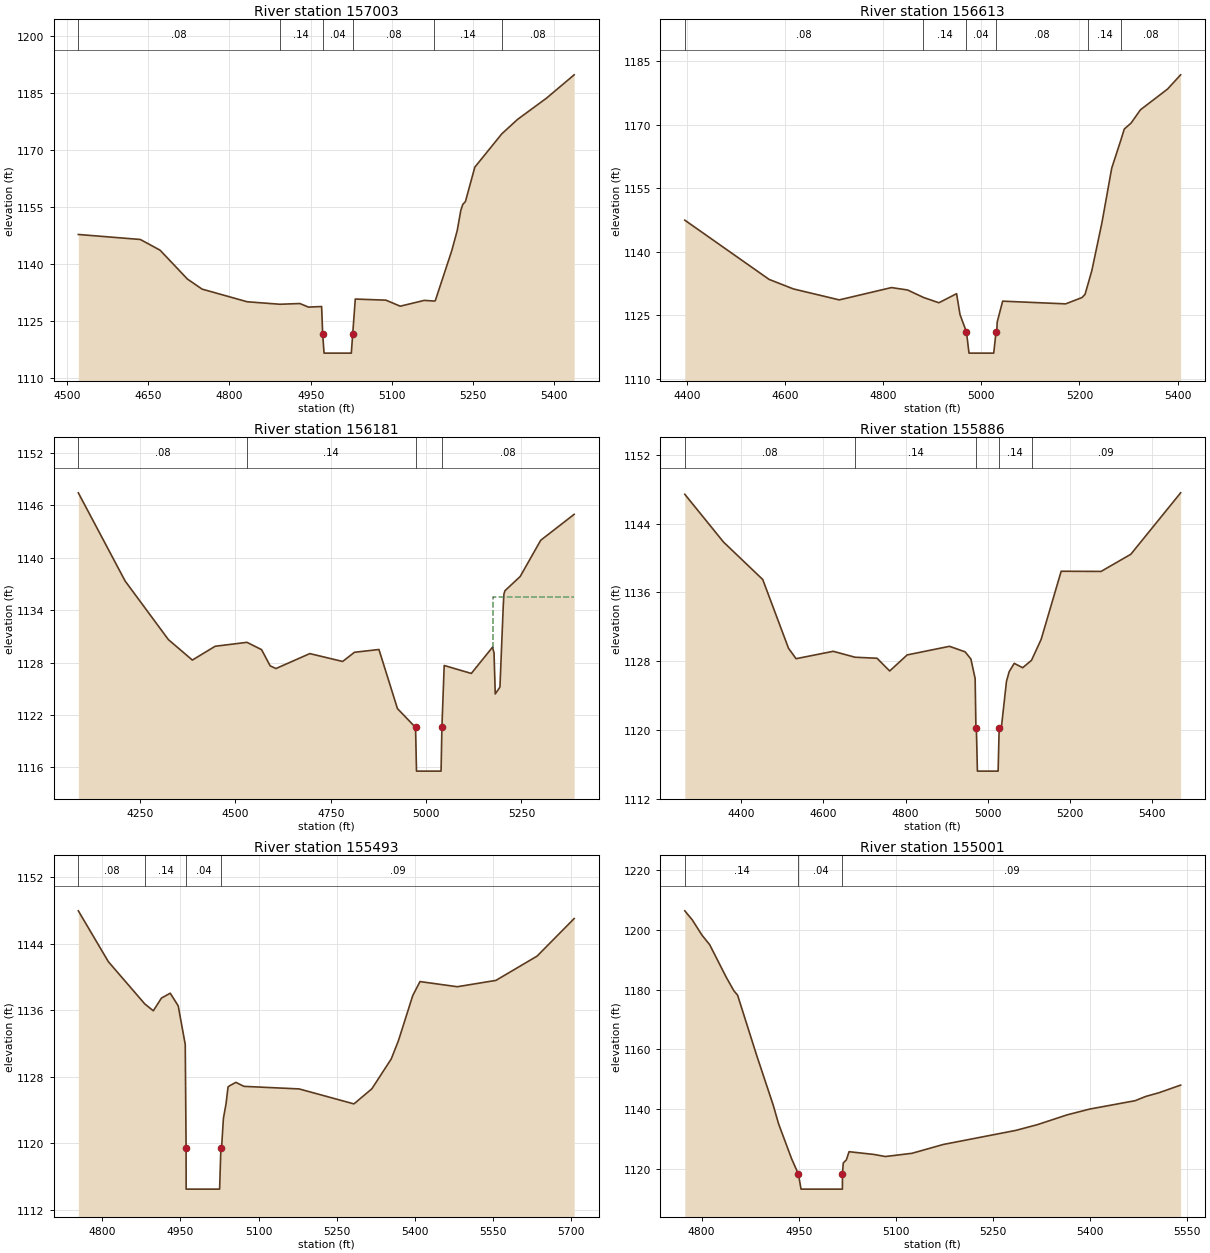
Type RM Length L Ch R = 1,157003,390,390,390
BEGIN DESCRIPTION:
Fisher River 314.0
END DESCRIPTION:
XS GIS Cut Line= 4
      1473523.06       982221.63      1473610.95       981880.59
      1473516.01       981680.17      1473540.62       981339.11
#Sta/Elev= 30
  4520.9 1147.75  4635.4 1146.43  4671.9 1143.61  4722.5 1135.99  4749.5 1133.35
  4832.7 1130.02  4893.1 1129.36  4930.1 1129.55  4946.0 1128.61  4970.3 1128.76
  4972.3 1121.48  4974.8 1116.48  5025.2 1116.48  5027.7 1121.48  5032.5 1130.73
  5089.1 1130.44  5115.5 1128.85  5160.0 1130.38  5178.5 1130.20  5180.2 1130.27
  5210.6 1143.42  5220.8 1148.78  5227.3 1154.01  5230.9 1155.62  5236.0 1156.44
  5253.3 1165.49  5303.2 1174.28  5332.2 1178.07  5385.7 1183.67  5436.8 1189.82
#Mann=6,-1,0
  4520.9    0.08       0  4893.1    0.14       0  4972.3    0.04       0
  5027.7    0.08       0  5178.5    0.14       0  5303.2    0.08       0
Bank Sta=4972.3,5027.7
XS Rating Curve= 0
Exp/Cntr=0.3,0.1

Type RM Length L Ch R = 1,156613,432,432,432
BEGIN DESCRIPTION:
Fisher River 313.0
END DESCRIPTION:
XS GIS Cut Line= 4
      1473828.96       982207.59      1473945.00       981676.65
      1473895.77       981574.68      1473705.89       981275.80
#Sta/Elev= 30
  4395.4 1147.48  4567.3 1133.48  4616.8 1131.23  4710.3 1128.64  4816.7 1131.55
  4849.6 1130.98  4881.9 1129.22  4913.4 1127.96  4949.5 1130.11  4956.4 1125.19
  4969.6 1121.06  4974.8 1116.06  5025.2 1116.06  5029.9 1121.06  5031.4 1121.06
  5032.2 1123.37  5043.4 1128.34  5171.8 1127.70  5204.9 1129.18  5211.3 1129.93
  5217.0 1132.22  5225.2 1135.57  5245.8 1146.89  5265.7 1159.75  5284.6 1166.49
  5291.3 1169.00  5305.2 1170.42  5324.3 1173.56  5379.5 1178.45  5406.2 1181.82
#Mann=6,-1,0
  4395.4    0.08       0  4881.9    0.14       0  4969.6    0.04       0
  5029.9    0.08       0  5217.0    0.14       0  5284.6    0.08       0
Bank Sta=4969.6,5029.9
XS Rating Curve= 0
Exp/Cntr=0.3,0.1

Type RM Length L Ch R = 1,156181,295,295,295
BEGIN DESCRIPTION:
Fisher River 312.5
END DESCRIPTION:
XS GIS Cut Line= 5
      1473860.60       982204.11      1473997.74       981743.46
      1474166.52       981560.61      1474359.92       981370.73
      1474616.60       981216.02
#Sta/Elev= 30
  4088.0 1147.42  4210.7 1137.33  4324.2 1130.62  4387.0 1128.28  4446.8 1129.86
  4530.2 1130.31  4568.6 1129.47  4591.0 1127.62  4606.2 1127.31  4695.0 1129.02
  4781.1 1128.12  4812.0 1129.17  4876.3 1129.49  4924.8 1122.73  4972.3 1120.57
  4974.8 1115.57  5039.2 1115.57  5041.4 1120.57  5047.4 1127.66  5118.5 1126.75
  5174.1 1129.75  5178.1 1129.10  5181.3 1124.40  5193.6 1125.19  5202.5 1134.73
  5204.1 1135.85  5206.8 1136.22  5246.6 1137.84  5300.5 1141.99  5388.2 1144.96
#Mann=4,-1,0
  4088.0    0.08       0  4530.2    0.14       0  4972.3    0.04       0
  5041.4    0.08       0
#XS Ineff=2,0
       0                 5174.30    0.00 1135.48
Permanent Ineff=
       F       F
Bank Sta=4972.3,5041.4
XS Rating Curve= 0
Exp/Cntr=0.3,0.1

Type RM Length L Ch R = 1,155886,393,393,393
BEGIN DESCRIPTION:
Fisher River 312.0
END DESCRIPTION:
XS GIS Cut Line= 5
      1473952.03       982214.67      1473990.71       981834.88
      1474191.14       981613.36      1474321.24       981697.75
      1474613.12       981469.16
#Sta/Elev= 30
  4262.9 1147.43  4357.1 1141.87  4452.5 1137.51  4515.3 1129.50  4533.6 1128.29
  4624.0 1129.15  4677.1 1128.46  4730.6 1128.34  4761.4 1126.86  4803.9 1128.73
  4906.9 1129.73  4944.8 1129.09  4959.0 1128.25  4969.3 1125.97  4971.2 1120.20
  4972.3 1120.20  4974.8 1115.20  5025.2 1115.20  5027.7 1120.20  5033.0 1120.24
  5045.5 1125.65  5052.1 1126.78  5064.4 1127.75  5084.9 1127.24  5106.4 1128.10
  5129.8 1130.53  5178.6 1138.47  5275.7 1138.45  5348.1 1140.45  5469.2 1147.60
#Mann=5,-1,0
  4262.9    0.08       0  4677.1    0.14       0  4972.3    0.04       0
  5027.7    0.14       0  5106.4    0.09       0
Bank Sta=4972.3,5027.7
XS Rating Curve= 0
Exp/Cntr=0.3,0.1

Type RM Length L Ch R = 1,155493,492,492,492
BEGIN DESCRIPTION:
Fisher River 311.0
END DESCRIPTION:
XS GIS Cut Line= 4
      1474050.48       982214.64      1474089.16       982021.24
      1474180.59       981915.76      1474623.65       981490.27
#Sta/Elev= 30
  4754.2 1147.95  4811.8 1141.84  4881.6 1136.77  4898.0 1135.94  4913.7 1137.47
  4930.5 1138.05  4945.8 1136.53  4959.3 1131.89  4960.9 1119.51  4961.0 1114.51
  5025.2 1114.51  5027.7 1119.51  5029.0 1119.51  5032.5 1123.01  5037.5 1124.76
  5041.4 1126.79  5044.7 1126.94  5056.4 1127.34  5071.8 1126.86  5177.8 1126.55
  5282.9 1124.75  5317.3 1126.57  5354.4 1130.15  5368.3 1132.36  5395.7 1137.77
  5409.6 1139.45  5481.1 1138.83  5555.2 1139.59  5634.2 1142.51  5705.3 1147.02
#Mann=4,-1,0
  4754.2    0.08       0  4881.6    0.14       0  4960.9    0.04       0
  5027.7    0.09       0
Bank Sta=4960.9,5027.7
XS Rating Curve= 0
Exp/Cntr=0.3,0.1

Type RM Length L Ch R = 1,155001,501,501,501
BEGIN DESCRIPTION:
Fisher River 310.0
END DESCRIPTION:
XS GIS Cut Line= 4
      1474651.78       982179.49      1474577.93       982021.24
      1474504.08       981950.92      1474651.76       981483.29
#Sta/Elev= 30
  4773.9 1206.30  4785.5 1203.26  4800.6 1198.14  4812.4 1194.98  4837.7 1184.23
  4849.8 1179.58  4855.6 1178.09  4885.3 1157.83  4910.7 1141.34  4919.0 1135.09
  4939.2 1123.38  4949.7 1118.27  4953.7 1113.27  5017.7 1113.27  5017.8 1118.27
  5019.0 1121.98  5023.9 1123.08  5028.0 1125.78  5066.6 1124.86  5084.1 1124.17
  5125.2 1125.24  5174.0 1128.21  5285.7 1132.89  5319.3 1134.82  5365.1 1138.08
  5400.2 1140.03  5470.5 1142.83  5486.9 1144.25  5507.8 1145.52  5540.9 1148.04
#Mann=3,-1,0
  4773.9    0.14       0  4949.7    0.04       0  5017.8    0.09       0
Bank Sta=4949.7,5017.8
XS Rating Curve= 0
Exp/Cntr=0.3,0.1

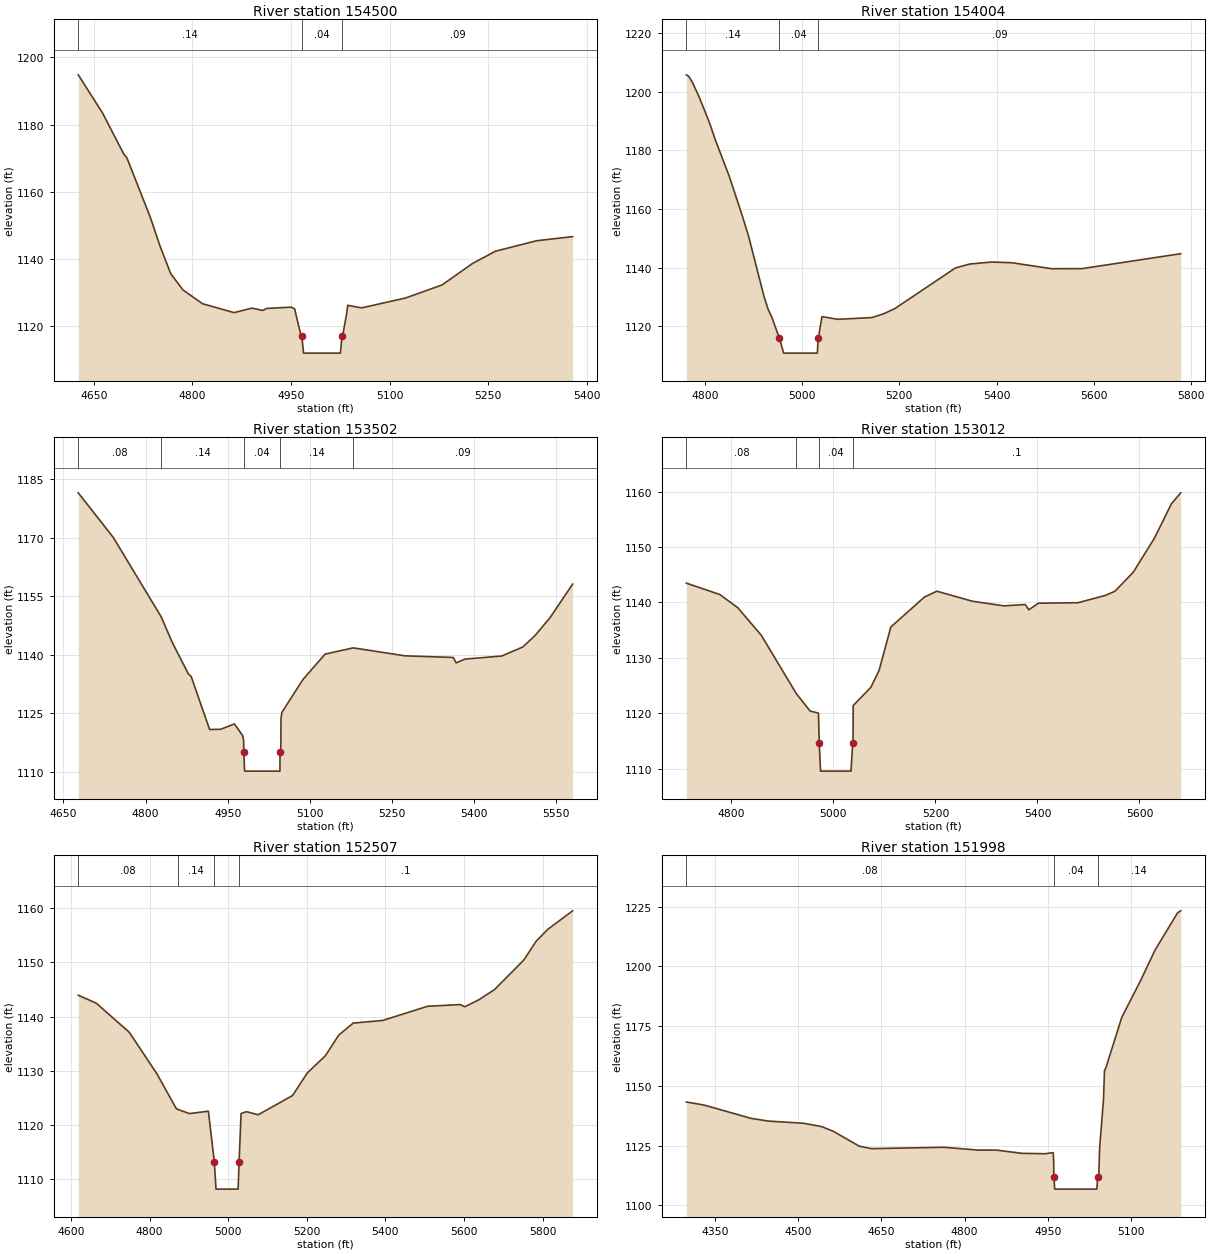
Type RM Length L Ch R = 1,154500,496,496,496
BEGIN DESCRIPTION:
Fisher River 309.0
END DESCRIPTION:
XS GIS Cut Line= 3
      1475137.04       982017.77      1474937.62       981701.96
      1474697.47       981409.40
#Sta/Elev= 30
  4626.5 1194.82  4663.5 1183.45  4695.6 1171.29  4700.5 1170.10  4735.9 1152.54
  4750.9 1143.86  4767.1 1135.67  4785.8 1130.80  4815.5 1126.71  4863.4 1124.05
  4890.9 1125.40  4907.0 1124.70  4913.2 1125.31  4950.2 1125.67  4955.6 1125.22
  4965.5 1117.07  4966.6 1117.00  4969.2 1112.00  5025.2 1112.00  5027.7 1117.00
  5028.5 1117.00  5034.9 1123.92  5036.4 1126.23  5057.5 1125.46  5124.2 1128.40
  5179.7 1132.27  5225.8 1138.62  5261.1 1142.33  5323.9 1145.45  5378.5 1146.67
#Mann=3,-1,0
  4626.5    0.14       0  4966.6    0.04       0  5027.7    0.09       0
Bank Sta=4966.6,5027.7
XS Rating Curve= 0
Exp/Cntr=0.3,0.1

Type RM Length L Ch R = 1,154004,502,502,502
BEGIN DESCRIPTION:
Fisher River 308.0
END DESCRIPTION:
XS GIS Cut Line= 4
      1475530.83       981654.49      1475390.19       981527.91
      1475221.40       981141.12      1474845.18       980990.98
#Sta/Elev= 30
  4762.1 1205.69  4766.6 1205.27  4774.3 1203.23  4788.0 1198.33  4809.0 1189.67
  4821.9 1183.44  4850.4 1171.09  4876.0 1158.26  4890.4 1150.49  4921.9 1130.12
  4930.1 1125.86  4938.3 1122.89  4953.6 1115.85  4962.2 1110.85  5031.4 1110.85
  5033.2 1115.85  5034.1 1115.93  5035.6 1118.12  5041.0 1123.30  5073.2 1122.38
  5143.6 1122.97  5167.4 1124.23  5191.2 1126.07  5315.2 1139.87  5344.9 1141.22
  5389.6 1141.89  5430.9 1141.66  5513.1 1139.62  5575.7 1139.65  5778.4 1144.73
#Mann=3,-1,0
  4762.1    0.14       0  4953.6    0.04       0  5033.2    0.09       0
Bank Sta=4953.6,5033.2
XS Rating Curve= 0
Exp/Cntr=0.3,0.1

Type RM Length L Ch R = 1,153502,490,490,490
BEGIN DESCRIPTION:
Fisher River 307.0
END DESCRIPTION:
XS GIS Cut Line= 4
      1475819.19       981281.81      1475724.23       981098.92
      1475467.54       981018.05      1475196.76       980687.49
#Sta/Elev= 30
  4677.1 1181.57  4741.0 1170.14  4828.2 1149.85  4849.3 1143.04  4878.4 1135.08
  4883.2 1134.51  4916.9 1120.89  4937.3 1120.95  4962.2 1122.33  4977.2 1119.33
  4979.0 1118.08  4979.3 1115.22  4980.8 1110.22  5045.3 1110.22  5045.4 1115.22
  5046.9 1115.23  5047.2 1123.75  5049.0 1125.32  5087.4 1133.72  5127.7 1140.22
  5179.1 1141.82  5273.7 1139.78  5361.7 1139.36  5367.1 1137.96  5382.6 1138.93
  5450.1 1139.73  5488.6 1142.05  5510.8 1144.95  5538.5 1149.59  5579.6 1158.17
#Mann=5,-1,0
  4677.1    0.08       0  4828.2    0.14       0  4979.3    0.04       0
  5045.4    0.14       0  5179.1    0.09       0
Bank Sta=4979.3,5045.4
XS Rating Curve= 0
Exp/Cntr=0.3,0.1

Type RM Length L Ch R = 1,153012,505,505,505
BEGIN DESCRIPTION:
Fisher River 306.0
END DESCRIPTION:
XS GIS Cut Line= 3
      1476089.89       980831.66      1475717.20       980536.32
      1475224.88       980571.49
#Sta/Elev= 30
  4711.7 1143.49  4777.4 1141.43  4812.6 1139.05  4858.7 1134.07  4927.3 1123.56
  4954.3 1120.42  4970.7 1120.03  4972.3 1114.57  4974.8 1109.57  5034.5 1109.57
  5037.8 1114.57  5038.5 1114.58  5038.8 1121.40  5073.5 1124.70  5089.5 1127.73
  5112.6 1135.57  5178.5 1140.98  5202.9 1142.03  5272.6 1140.22  5333.9 1139.39
  5376.1 1139.63  5383.2 1138.68  5401.8 1139.87  5479.3 1139.95  5532.4 1141.25
  5551.8 1142.02  5587.8 1145.45  5629.4 1151.61  5662.6 1157.80  5680.8 1159.78
#Mann=4,-1,0
  4711.7    0.08       0  4927.3    0.14       0  4972.3    0.04       0
  5037.8     0.1       0
Bank Sta=4972.3,5037.8
XS Rating Curve= 0
Exp/Cntr=0.3,0.1

Type RM Length L Ch R = 1,152507,509,509,509
BEGIN DESCRIPTION:
Fisher River 305.0
END DESCRIPTION:
XS GIS Cut Line= 5
      1476378.23       980501.13      1476181.35       980247.99
      1476065.31       980202.27      1475854.33       980364.02
      1475312.80       980290.18
#Sta/Elev= 30
  4618.5 1143.94  4664.4 1142.47  4748.2 1137.12  4818.7 1129.45  4867.5 1123.08
  4872.6 1122.87  4901.6 1122.12  4949.6 1122.56  4964.7 1113.19  4969.0 1108.19
  5025.2 1108.19  5027.7 1113.19  5032.7 1122.12  5046.4 1122.47  5076.2 1121.90
  5163.8 1125.45  5201.6 1129.64  5247.1 1132.77  5281.2 1136.58  5318.0 1138.80
  5393.2 1139.29  5507.3 1141.90  5590.4 1142.22  5602.0 1141.81  5638.1 1143.12
  5677.6 1144.98  5752.4 1150.45  5783.4 1153.89  5812.8 1156.07  5876.3 1159.50
#Mann=4,-1,0
  4618.5    0.08       0  4872.6    0.14       0  4964.7    0.04       0
  5027.7     0.1       0
Bank Sta=4964.7,5027.7
XS Rating Curve= 0
Exp/Cntr=0.3,0.1

Type RM Length L Ch R = 1,151998,494,494,494
BEGIN DESCRIPTION:
Fisher River 304.0
END DESCRIPTION:
XS GIS Cut Line= 3
      1476466.17       980476.55      1476416.94       979857.68
      1476286.81       979622.05
#Sta/Elev= 30
  4298.9 1143.30  4330.4 1142.06  4415.5 1136.46  4446.0 1135.33  4509.5 1134.42
  4542.4 1133.03  4563.6 1131.04  4610.2 1124.83  4632.0 1123.79  4763.1 1124.36
  4823.8 1123.19  4857.2 1123.18  4903.2 1121.82  4944.7 1121.66  4959.4 1122.12
  4960.2 1118.57  4960.6 1111.85  4962.1 1106.85  5037.9 1106.85  5039.4 1111.85
  5041.4 1111.86  5042.9 1123.86  5049.9 1144.24  5051.7 1156.39  5054.3 1157.67
  5082.9 1178.75  5118.0 1194.71  5142.5 1206.79  5183.1 1222.40  5188.9 1223.29
#Mann=3,-1,0
  4298.9    0.08       0  4960.6    0.04       0  5039.4    0.14       0
Bank Sta=4960.6,5039.4
XS Rating Curve= 0
Exp/Cntr=0.3,0.1

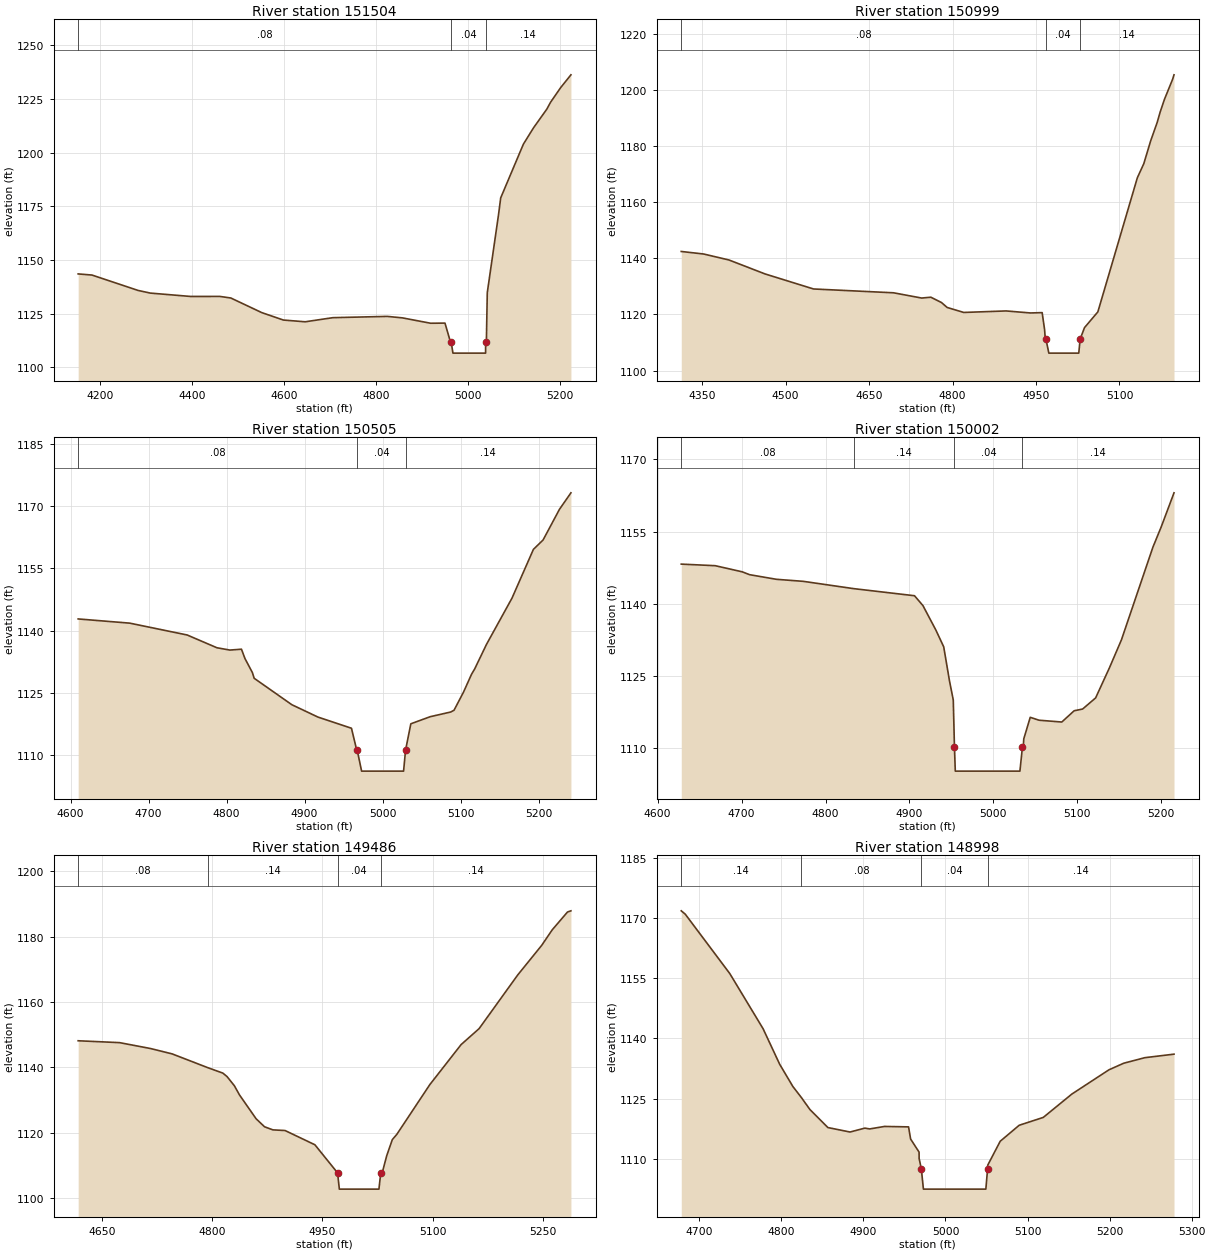
Type RM Length L Ch R = 1,151504,505,505,505
BEGIN DESCRIPTION:
Fisher River 303.0
END DESCRIPTION:
XS GIS Cut Line= 4
      1476480.24       980497.63      1476831.86       979819.00
      1476881.09       979664.28      1476845.94       979523.68
#Sta/Elev= 30
  4152.6 1143.47  4182.7 1142.94  4282.8 1135.78  4309.4 1134.54  4397.2 1132.97
  4461.0 1132.98  4484.6 1132.25  4551.8 1125.45  4598.9 1121.98  4646.3 1121.17
  4706.6 1123.09  4825.0 1123.68  4857.5 1123.00  4919.1 1120.49  4950.3 1120.56
  4962.5 1111.57  4963.9 1111.57  4967.6 1106.57  5038.6 1106.57  5038.7 1111.57
  5040.3 1111.57  5042.3 1134.75  5066.7 1171.00  5071.5 1178.90  5120.8 1203.92
  5142.9 1211.55  5171.7 1220.22  5180.2 1223.54  5201.9 1230.27  5224.2 1236.22
#Mann=3,-1,0
  4152.6    0.08       0  4963.9    0.04       0  5038.7    0.14       0
Bank Sta=4963.9,5038.7
XS Rating Curve= 0
Exp/Cntr=0.3,0.1

Type RM Length L Ch R = 1,150999,494,494,494
BEGIN DESCRIPTION:
Fisher River 302.0
END DESCRIPTION:
XS GIS Cut Line= 3
      1476522.44       980511.70      1476944.38       980058.11
      1477204.57       980114.36
#Sta/Elev= 30
  4312.4 1142.42  4352.6 1141.52  4398.2 1139.39  4463.2 1134.41  4550.2 1129.07
  4693.9 1127.71  4744.5 1125.84  4761.0 1126.14  4780.1 1124.25  4790.3 1122.49
  4820.2 1120.71  4896.2 1121.25  4940.1 1120.53  4961.1 1120.65  4965.5 1114.57
  4966.7 1111.23  4967.9 1111.23  4973.1 1106.23  5026.9 1106.23  5029.4 1111.23
  5037.2 1115.30  5061.2 1120.91  5132.2 1168.66  5143.7 1173.63  5156.1 1181.78
  5167.7 1188.27  5173.3 1192.11  5181.0 1196.63  5195.6 1203.73  5198.1 1205.31
#Mann=3,-1,0
  4312.4    0.08       0  4967.9    0.04       0  5029.4    0.14       0
Bank Sta=4967.9,5029.4
XS Rating Curve= 0
Exp/Cntr=0.3,0.1

Type RM Length L Ch R = 1,150505,503,503,503
BEGIN DESCRIPTION:
Fisher River 301.0
END DESCRIPTION:
XS GIS Cut Line= 4
      1476487.22       980550.74      1476782.63       980497.99
      1476933.83       980564.80      1477099.12       980547.22
#Sta/Elev= 30
  4609.8 1142.83  4675.9 1141.82  4749.5 1138.97  4787.6 1135.90  4804.2 1135.34
  4819.1 1135.55  4823.6 1133.30  4833.1 1129.93  4835.4 1128.55  4883.7 1122.19
  4917.1 1119.22  4960.1 1116.53  4966.9 1111.21  4967.5 1111.21  4973.1 1106.21
  5026.9 1106.21  5029.4 1111.21  5036.2 1117.60  5060.9 1119.30  5087.4 1120.44
  5091.6 1120.87  5103.8 1125.26  5113.9 1129.48  5118.1 1130.83  5133.2 1136.72
  5165.9 1147.85  5193.3 1159.57  5205.7 1161.83  5226.7 1169.21  5241.4 1173.18
#Mann=3,-1,0
  4609.8    0.08       0  4967.5    0.04       0  5029.4    0.14       0
Bank Sta=4967.5,5029.4
XS Rating Curve= 0
Exp/Cntr=0.3,0.1

Type RM Length L Ch R = 1,150002,516,516,516
BEGIN DESCRIPTION:
Fisher River 300.0
END DESCRIPTION:
XS GIS Cut Line= 3
      1476455.62       981085.21      1476670.11       981018.40
      1477032.28       981032.47
#Sta/Elev= 30
  4628.1 1148.25  4668.6 1147.92  4700.7 1146.65  4709.6 1146.05  4741.6 1145.09
  4773.5 1144.67  4833.7 1143.15  4906.0 1141.68  4916.1 1139.62  4931.4 1134.57
  4940.8 1131.07  4947.7 1123.98  4952.2 1120.01  4953.6 1110.24  4954.6 1105.24
  5031.6 1105.24  5034.6 1110.24  5035.6 1110.24  5036.2 1111.94  5043.9 1116.42
  5054.3 1115.82  5081.5 1115.44  5096.2 1117.78  5106.3 1118.14  5121.8 1120.45
  5138.3 1126.72  5152.5 1132.49  5190.1 1151.79  5199.9 1155.96  5215.2 1163.06
#Mann=4,-1,0
  4628.1    0.08       0  4833.7    0.14       0  4953.6    0.04       0
  5034.6    0.14       0
Bank Sta=4953.6,5034.6
XS Rating Curve= 0
Exp/Cntr=0.3,0.1

Type RM Length L Ch R = 1,149486,488,488,488
BEGIN DESCRIPTION:
Fisher River 299.0
END DESCRIPTION:
XS GIS Cut Line= 3
      1476427.48       981130.92      1476701.76       981602.10
      1476807.27       981668.93
#Sta/Elev= 30
  4617.9 1148.12  4674.1 1147.55  4716.2 1145.75  4745.7 1144.10  4794.3 1139.87
  4814.6 1138.22  4820.4 1137.14  4830.3 1134.35  4837.2 1131.56  4859.9 1124.22
  4871.4 1121.77  4882.7 1120.83  4899.2 1120.63  4939.8 1116.27  4970.6 1107.68
  4973.1 1102.68  5026.9 1102.68  5029.4 1107.68  5031.8 1108.06  5037.5 1112.92
  5045.1 1117.84  5051.3 1119.48  5096.2 1134.72  5138.7 1146.96  5163.1 1151.83
  5215.7 1168.29  5248.2 1177.33  5262.6 1182.11  5283.3 1187.55  5288.0 1187.92
#Mann=4,-1,0
  4617.9    0.08       0  4794.3    0.14       0  4970.6    0.04       0
  5029.4    0.14       0
Bank Sta=4970.6,5029.4
XS Rating Curve= 0
Exp/Cntr=0.3,0.1

Type RM Length L Ch R = 1,148998,501,501,501
BEGIN DESCRIPTION:
Fisher River 298.0
END DESCRIPTION:
XS GIS Cut Line= 3
      1475998.47       981450.87      1476139.15       981598.59
      1476329.02       981946.68
#Sta/Elev= 30
  4678.0 1171.74  4682.9 1170.90  4737.2 1156.10  4777.7 1142.39  4798.0 1133.51
  4814.1 1127.97  4824.3 1125.27  4834.8 1122.26  4856.7 1117.77  4883.7 1116.66
  4901.7 1117.63  4907.7 1117.43  4925.7 1118.05  4955.0 1117.94  4957.5 1114.92
  4967.8 1111.66  4967.9 1110.05  4970.6 1107.44  4973.1 1102.44  5049.2 1102.44
  5051.3 1107.44  5051.5 1108.41  5066.7 1114.36  5089.8 1118.34  5119.2 1120.30
  5154.0 1126.11  5199.2 1132.15  5217.2 1133.79  5242.9 1135.17  5278.5 1136.05
#Mann=4,-1,0
  4678.0    0.14       0  4824.3    0.08       0  4970.6    0.04       0
  5051.3    0.14       0
Bank Sta=4970.6,5051.3
XS Rating Curve= 0
Exp/Cntr=0.3,0.1