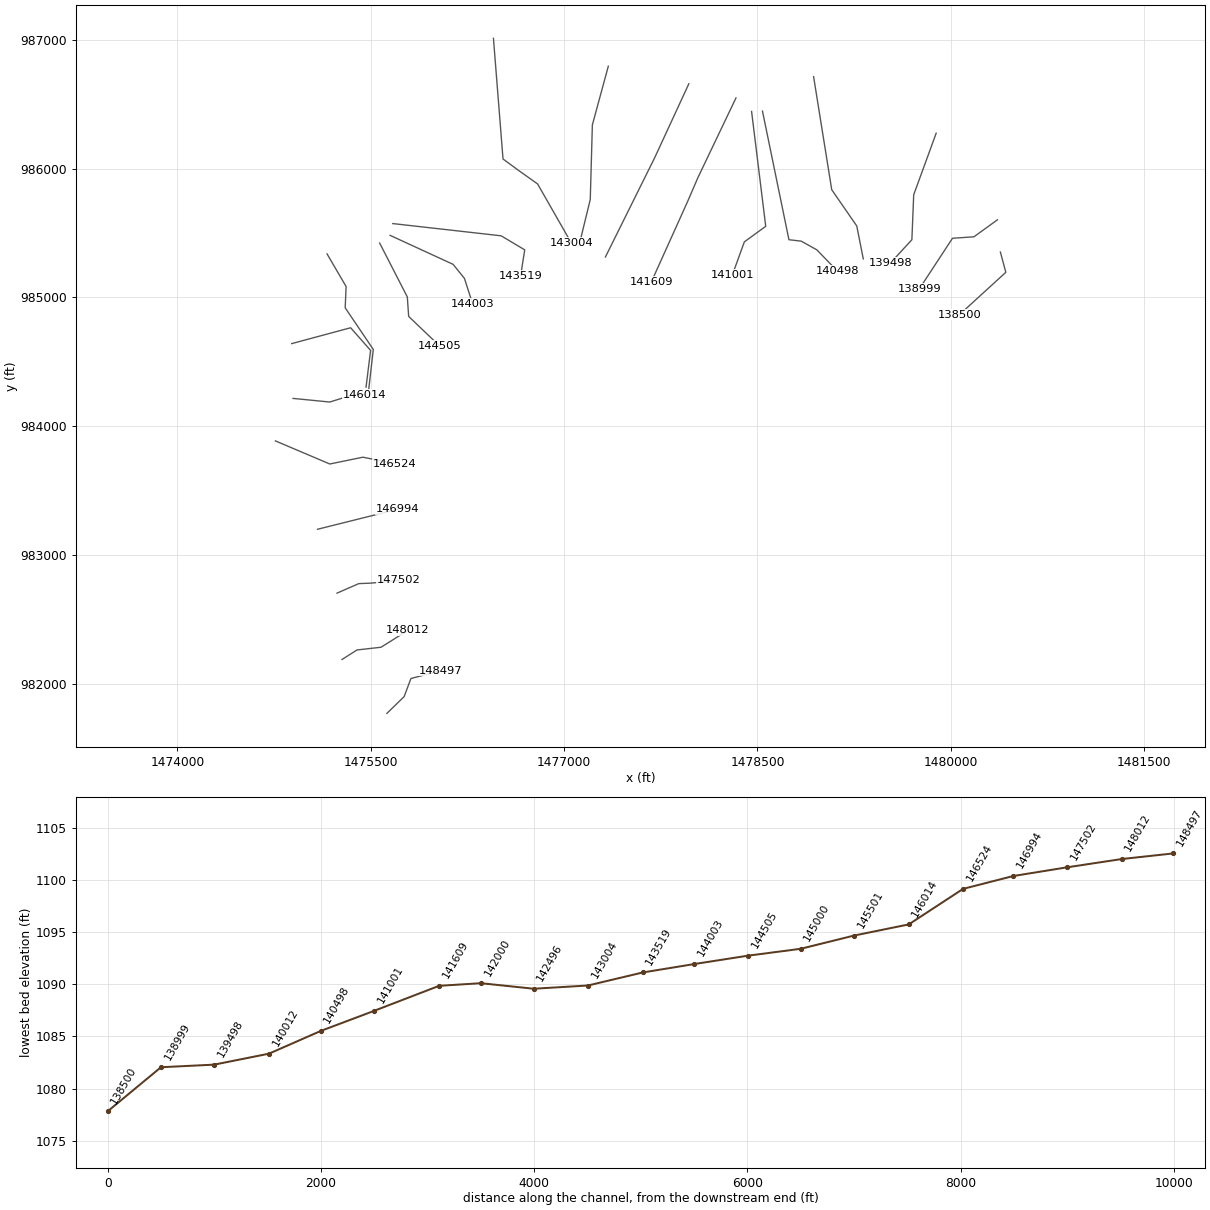
HEC-RAS study Fisher River.prj: Fisher River Limited Detail Study

--- Fisher River.g01 (geometry) --- (continued)

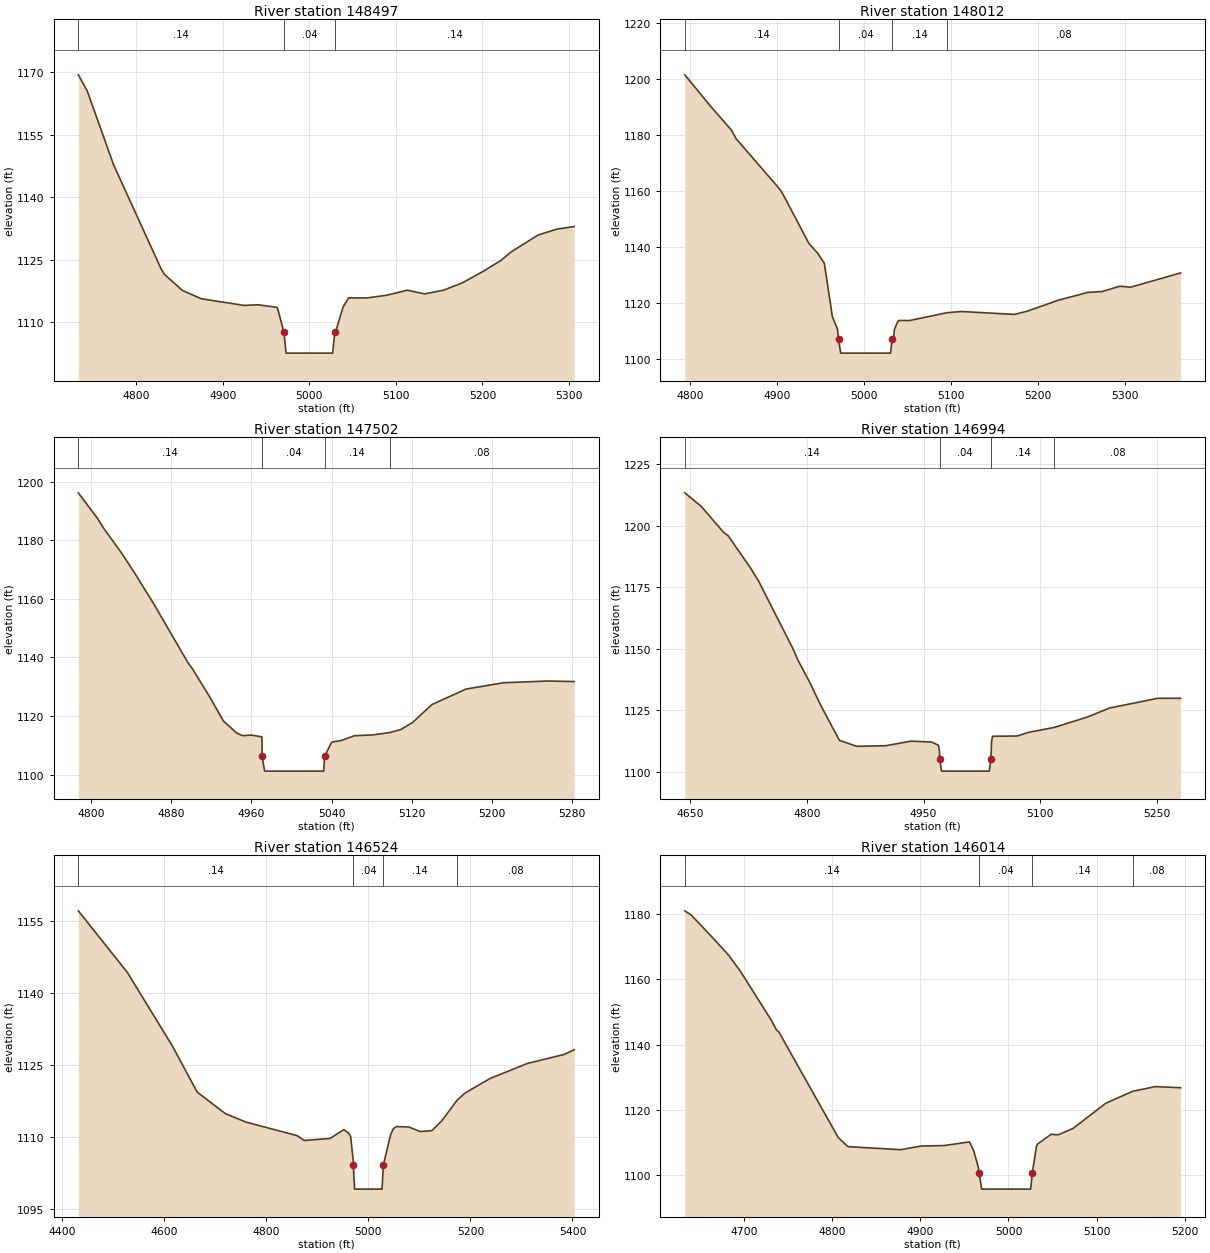
Type RM Length L Ch R = 1,148497,485,485,485
BEGIN DESCRIPTION:
Fisher River 297.0
END DESCRIPTION:
XS GIS Cut Line= 4
      1475625.77       981770.88      1475759.39       981900.99
      1475812.14       982041.64      1476040.73       982101.42
#Sta/Elev= 30
  4733.0 1169.39  4743.1 1165.61  4773.9 1147.71  4828.6 1122.82  4832.5 1121.47
  4853.3 1117.60  4875.1 1115.61  4924.6 1114.01  4940.3 1114.16  4962.4 1113.56
  4963.5 1113.14  4970.6 1107.55  4973.1 1102.55  5026.9 1102.55  5029.4 1107.55
  5030.1 1107.55  5039.1 1113.67  5045.3 1115.82  5066.7 1115.81  5089.1 1116.44
  5113.0 1117.66  5133.2 1116.78  5155.0 1117.66  5177.1 1119.46  5200.3 1122.13
  5221.1 1124.77  5233.6 1126.92  5264.2 1130.90  5285.8 1132.32  5306.0 1132.95
#Mann=3,-1,0
  4733.0    0.14       0  4970.6    0.04       0  5029.4    0.14       0
Bank Sta=4970.6,5029.4
XS Rating Curve= 0
Exp/Cntr=0.3,0.1

Type RM Length L Ch R = 1,148012,510,510,510
BEGIN DESCRIPTION:
Fisher River 296.0
END DESCRIPTION:
XS GIS Cut Line= 4
      1475277.67       982189.32      1475393.70       982263.16
      1475580.06       982284.26      1475787.55       982414.38
#Sta/Elev= 30
  4793.9 1201.39  4823.3 1190.26  4847.7 1181.58  4852.8 1178.63  4903.1 1160.55
  4907.0 1158.62  4936.6 1141.17  4946.5 1137.76  4954.3 1134.11  4963.6 1114.94
  4969.4 1110.67  4970.6 1107.01  4973.1 1102.01  5030.4 1102.01  5032.3 1107.01
  5033.9 1107.01  5034.9 1110.53  5038.9 1113.40  5040.5 1113.68  5051.9 1113.62
  5095.4 1116.45  5112.0 1116.87  5172.7 1115.84  5187.6 1116.97  5223.2 1120.90
  5257.3 1123.70  5273.6 1124.00  5294.0 1125.90  5306.4 1125.55  5363.9 1130.65
#Mann=4,-1,0
  4793.9    0.14       0  4970.6    0.04       0  5032.3    0.14       0
  5095.4    0.08       0
Bank Sta=4970.6,5032.3
XS Rating Curve= 0
Exp/Cntr=0.3,0.1

Type RM Length L Ch R = 1,147502,508,508,508
BEGIN DESCRIPTION:
Fisher River 295.0
END DESCRIPTION:
XS GIS Cut Line= 4
      1475238.97       982704.45      1475407.77       982778.30
      1475499.19       982781.81      1475717.23       982802.91
#Sta/Elev= 30
  4787.2 1196.17  4806.5 1187.38  4812.1 1184.27  4829.9 1175.84  4843.2 1168.91
  4862.3 1158.39  4896.5 1138.27  4901.6 1135.86  4919.0 1126.14  4932.0 1118.31
  4945.3 1114.21  4951.2 1113.32  4959.7 1113.52  4970.4 1112.91  4970.6 1106.22
  4973.1 1101.22  5032.1 1101.22  5032.9 1106.22  5040.0 1111.09  5049.7 1111.69
  5062.7 1113.29  5081.3 1113.58  5098.2 1114.38  5109.0 1115.41  5120.8 1117.83
  5140.1 1123.94  5174.1 1129.22  5211.7 1131.38  5256.0 1131.97  5282.0 1131.77
#Mann=4,-1,0
  4787.2    0.14       0  4970.6    0.04       0  5032.9    0.14       0
  5098.2    0.08       0
Bank Sta=4970.6,5032.9
XS Rating Curve= 0
Exp/Cntr=0.3,0.1

Type RM Length L Ch R = 1,146994,470,470,470
BEGIN DESCRIPTION:
Fisher River 294.0
END DESCRIPTION:
XS GIS Cut Line= 3
      1475087.81       983200.26      1475326.89       983260.03
      1475706.67       983354.97
#Sta/Elev= 30
  4642.8 1213.38  4664.2 1207.79  4692.5 1197.40  4698.5 1195.98  4726.8 1183.11
  4737.6 1177.62  4781.5 1150.37  4788.9 1145.11  4803.2 1136.64  4817.7 1127.09
  4841.7 1112.87  4864.1 1110.45  4901.3 1110.70  4934.3 1112.57  4960.4 1112.17
  4969.1 1110.90  4970.5 1108.22  4970.6 1105.38  4973.1 1100.38  5034.5 1100.38
  5036.7 1105.38  5037.4 1112.19  5038.7 1114.52  5070.7 1114.65  5084.7 1116.11
  5118.2 1118.13  5161.0 1122.37  5189.2 1126.00  5251.2 1129.95  5280.7 1129.97
#Mann=4,-1,0
  4642.8    0.14       0  4970.6    0.04       0  5036.7    0.14       0
  5118.2    0.08       0
Bank Sta=4970.6,5036.7
XS Rating Curve= 0
Exp/Cntr=0.3,0.1

Type RM Length L Ch R = 1,146524,510,510,510
BEGIN DESCRIPTION:
Fisher River 293.0
END DESCRIPTION:
XS GIS Cut Line= 4
      1474760.81       983886.26      1475182.73       983706.95
      1475439.41       983759.69      1475685.55       983710.46
#Sta/Elev= 30
  4431.8 1157.03  4527.8 1144.23  4616.0 1128.93  4664.6 1119.34  4720.1 1114.84
  4760.4 1113.09  4860.8 1110.26  4874.5 1109.27  4925.0 1109.69  4951.9 1111.51
  4960.9 1110.86  4965.4 1110.04  4970.4 1105.07  4970.6 1104.15  4973.1 1099.15
  5026.9 1099.15  5029.4 1104.15  5043.9 1110.54  5049.1 1111.72  5055.1 1112.16
  5079.4 1112.06  5102.1 1111.12  5124.5 1111.32  5143.8 1113.34  5174.0 1117.64
  5189.3 1119.12  5238.3 1122.15  5311.7 1125.29  5383.7 1127.16  5403.3 1128.14
#Mann=4,-1,0
  4431.8    0.14       0  4970.6    0.04       0  5029.4    0.14       0
  5174.0    0.08       0
Bank Sta=4970.6,5029.4
XS Rating Curve= 0
Exp/Cntr=0.3,0.1

Type RM Length L Ch R = 1,146014,513,513,513
BEGIN DESCRIPTION:
Fisher River 292.0
END DESCRIPTION:
XS GIS Cut Line= 4
      1474897.93       984216.10      1475182.73       984187.97
      1475362.06       984244.23      1475449.93       984244.23
#Sta/Elev= 30
  4633.1 1180.93  4640.4 1179.62  4662.4 1173.36  4682.5 1167.44  4695.9 1162.53
  4731.2 1147.43  4737.1 1144.44  4739.6 1143.90  4807.0 1111.54  4818.0 1108.75
  4878.0 1107.81  4900.8 1108.93  4927.2 1109.08  4955.8 1110.20  4960.6 1107.47
  4966.0 1102.24  4966.1 1100.74  4966.7 1100.74  4969.6 1095.74  5025.1 1095.74
  5027.0 1100.74  5031.7 1108.85  5032.7 1109.48  5048.4 1112.53  5056.2 1112.36
  5073.2 1114.33  5110.4 1122.05  5140.9 1125.69  5166.6 1127.13  5195.1 1126.77
#Mann=4,-1,0
  4633.1    0.14       0  4966.7    0.04       0  5027.0    0.14       0
  5140.9    0.08       0
Bank Sta=4966.7,5027
XS Rating Curve= 0
Exp/Cntr=0.3,0.1

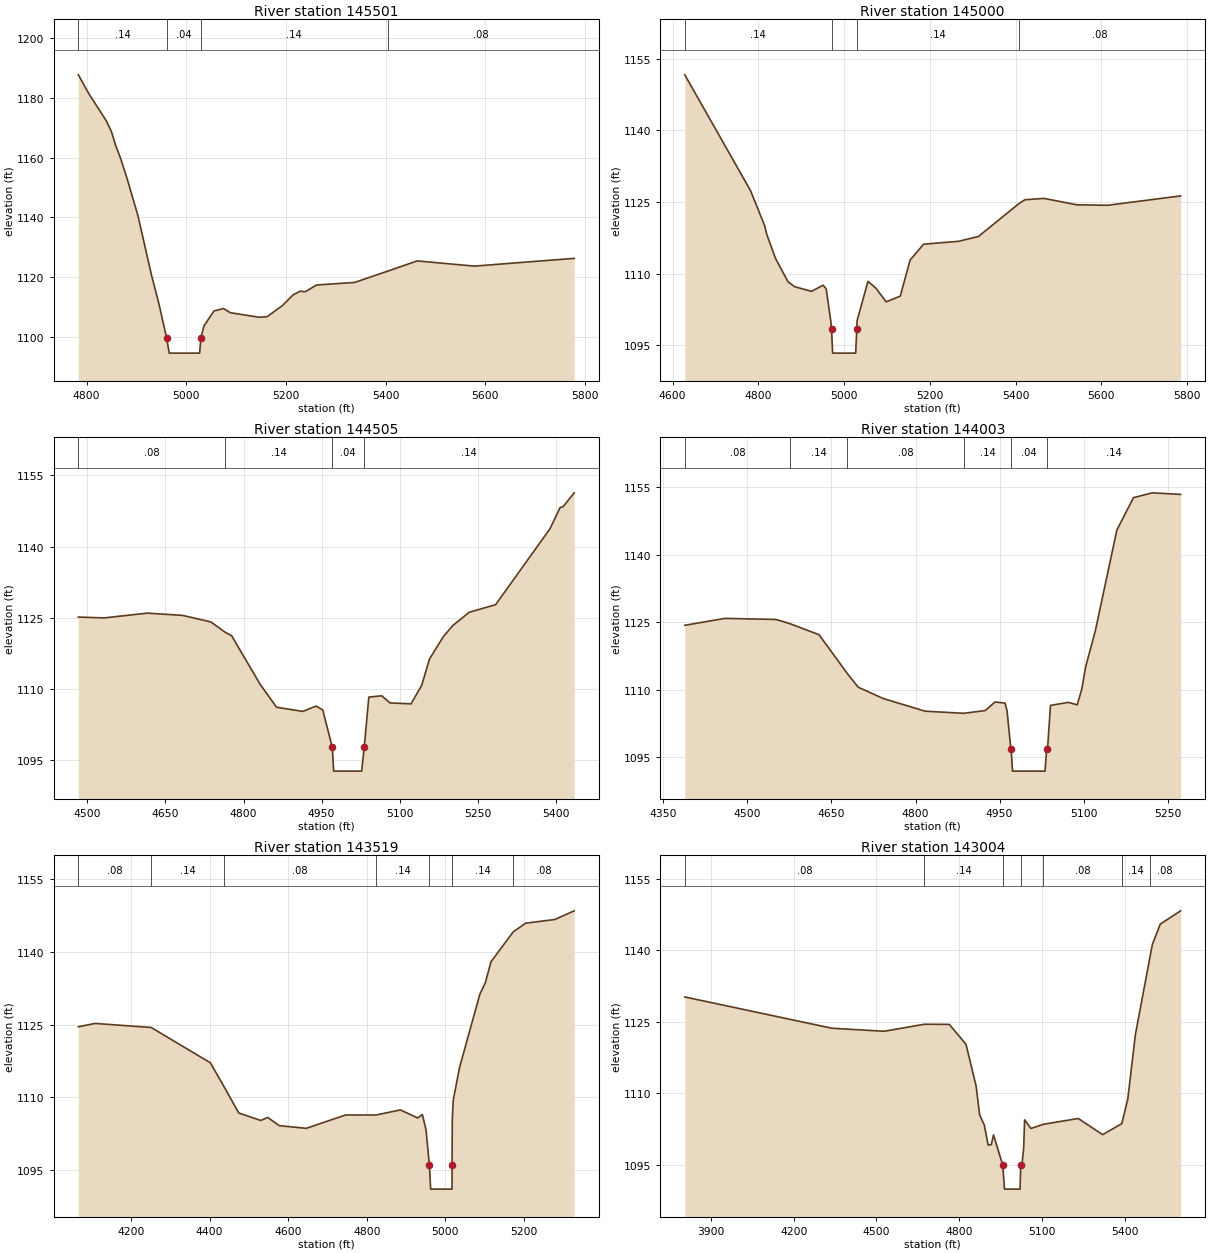
Type RM Length L Ch R = 1,145501,501,501,501
BEGIN DESCRIPTION:
Fisher River 291.0
END DESCRIPTION:
XS GIS Cut Line= 4
      1474887.31       984641.56      1475344.47       984764.64
      1475499.19       984588.83      1475464.03       984304.03
#Sta/Elev= 30
  4783.6 1187.64  4804.9 1181.28  4839.7 1172.28  4849.9 1168.71  4858.6 1164.01
  4867.6 1160.10  4881.2 1153.10  4903.1 1140.63  4930.7 1120.50  4945.2 1111.20
  4960.8 1099.67  4965.9 1094.67  5026.9 1094.67  5029.4 1099.67  5035.6 1103.76
  5055.7 1108.76  5074.9 1109.56  5088.6 1108.17  5145.6 1106.67  5162.2 1106.83
  5193.0 1110.56  5214.6 1114.16  5228.5 1115.35  5238.9 1115.20  5261.6 1117.43
  5337.7 1118.28  5403.8 1122.04  5463.3 1125.47  5578.3 1123.74  5778.2 1126.33
#Mann=4,-1,0
  4783.6    0.14       0  4960.8    0.04       0  5029.4    0.14       0
  5403.8    0.08       0
Bank Sta=4960.8,5029.4
XS Rating Curve= 0
Exp/Cntr=0.3,0.1

Type RM Length L Ch R = 1,145000,495,495,495
BEGIN DESCRIPTION:
Fisher River 290.0
END DESCRIPTION:
XS GIS Cut Line= 5
      1475161.63       985337.79      1475309.31       985084.62
      1475302.28       984919.36      1475520.29       984595.86
      1475485.13       984289.98
#Sta/Elev= 30
  4628.3 1151.64  4781.5 1127.42  4814.1 1120.18  4819.5 1118.25  4839.6 1113.28
  4868.8 1108.36  4884.2 1107.31  4923.8 1106.33  4951.0 1107.62  4958.0 1106.87
  4968.7 1100.19  4970.6 1098.40  4973.1 1093.40  5026.9 1093.40  5029.4 1098.40
  5030.1 1100.18  5055.6 1108.43  5074.3 1106.97  5098.0 1104.13  5130.9 1105.33
  5153.7 1112.85  5185.3 1116.20  5266.9 1116.80  5313.2 1117.81  5407.1 1124.65
  5421.6 1125.50  5466.3 1125.78  5542.7 1124.44  5614.6 1124.34  5784.8 1126.30
#Mann=4,-1,0
  4628.3    0.14       0  4970.6    0.04       0  5029.4    0.14       0
  5407.1    0.08       0
Bank Sta=4970.6,5029.4
XS Rating Curve= 0
Exp/Cntr=0.3,0.1

Type RM Length L Ch R = 1,144505,502,502,502
BEGIN DESCRIPTION:
Fisher River 289.0
END DESCRIPTION:
XS GIS Cut Line= 4
      1475569.51       985422.19      1475784.01       985003.75
      1475794.56       984852.55      1476033.69       984623.96
#Sta/Elev= 30
  4482.6 1125.18  4532.2 1125.01  4615.2 1126.01  4682.8 1125.54  4737.4 1124.15
  4764.3 1122.02  4777.0 1121.27  4831.7 1111.06  4863.5 1106.19  4913.9 1105.32
  4939.4 1106.44  4952.2 1105.62  4970.6 1097.74  4973.1 1092.74  5026.9 1092.74
  5031.9 1097.74  5040.7 1108.33  5065.4 1108.61  5081.5 1107.10  5121.8 1106.91
  5142.2 1110.79  5157.4 1116.38  5184.3 1121.13  5202.5 1123.44  5233.7 1126.20
  5284.3 1127.79  5388.8 1143.79  5408.2 1148.25  5413.8 1148.41  5435.2 1151.35
#Mann=4,-1,0
  4482.6    0.08       0  4764.3    0.14       0  4970.6    0.04       0
  5031.9    0.14       0
Bank Sta=4970.6,5031.9
XS Rating Curve= 0
Exp/Cntr=0.3,0.1

Type RM Length L Ch R = 1,144003,484,484,484
BEGIN DESCRIPTION:
Fisher River 288.0
END DESCRIPTION:
XS GIS Cut Line= 4
      1475650.43       985481.94      1476139.15       985256.92
      1476227.06       985147.91      1476290.35       984951.01
#Sta/Elev= 30
  4388.2 1124.34  4459.8 1125.88  4551.1 1125.64  4576.0 1124.70  4627.8 1122.25
  4678.5 1113.58  4697.8 1110.58  4742.4 1108.07  4817.0 1105.26  4886.4 1104.79
  4924.4 1105.40  4941.8 1107.30  4959.8 1107.06  4963.3 1105.39  4970.0 1096.97
  4970.6 1096.94  4973.1 1091.94  5031.1 1091.94  5034.1 1096.94  5035.6 1096.94
  5040.9 1106.55  5072.5 1107.21  5088.6 1106.68  5096.7 1110.16  5103.4 1115.01
  5120.9 1123.13  5159.3 1145.51  5189.0 1152.71  5222.7 1153.78  5273.1 1153.43
#Mann=6,-1,0
  4388.2    0.08       0  4576.0    0.14       0  4678.5    0.08       0
  4886.4    0.14       0  4970.6    0.04       0  5034.1    0.14       0
Bank Sta=4970.6,5034.1
XS Rating Curve= 0
Exp/Cntr=0.3,0.1

Type RM Length L Ch R = 1,143519,515,515,515
BEGIN DESCRIPTION:
Fisher River 287.0
END DESCRIPTION:
XS GIS Cut Line= 5
      1475671.46       985573.39      1476511.88       985478.44
      1476694.72       985369.44      1476668.58       985203.86
      1476663.07       985168.96
#Sta/Elev= 30
  4066.1 1124.54  4108.9 1125.23  4251.6 1124.39  4402.1 1117.13  4437.0 1112.19
  4474.3 1106.80  4530.2 1105.26  4548.0 1105.88  4577.5 1104.19  4646.1 1103.64
  4746.2 1106.39  4823.6 1106.38  4885.4 1107.43  4929.6 1105.78  4941.5 1106.48
  4950.8 1103.33  4959.3 1096.13  4962.6 1091.13  5016.9 1091.13  5017.0 1096.13
  5017.6 1105.41  5020.1 1109.44  5035.9 1116.11  5087.7 1131.23  5101.9 1133.64
  5116.0 1137.92  5172.4 1144.04  5203.9 1145.85  5278.8 1146.62  5327.7 1148.40
#Mann=7,-1,0
  4066.1    0.08       0  4251.6    0.14       0  4437.0    0.08       0
  4823.6    0.14       0  4959.3    0.04       0  5017.0    0.14       0
  5172.4    0.08       0
#XS Ineff=2,0
    0.00 4885.40 1107.43               0
Permanent Ineff=
       F       F
Bank Sta=4959.3,5017
XS Rating Curve= 0
Exp/Cntr=0.3,0.1

Type RM Length L Ch R = 1,143004,508,508,508
BEGIN DESCRIPTION:
Fisher River 286.0
END DESCRIPTION:
XS GIS Cut Line= 5
      1476452.10       987011.53      1476526.32       986074.77
      1476648.31       985985.14      1476794.59       985881.06
      1477056.19       985422.54
#Sta/Elev= 30
  3804.8 1130.20  4337.9 1123.64  4527.7 1123.00  4673.4 1124.47  4764.3 1124.44
  4824.8 1120.26  4861.6 1111.48  4874.3 1105.43  4891.2 1103.33  4905.2 1099.11
  4916.6 1099.22  4924.6 1101.25  4958.2 1094.88  4964.4 1089.88  5020.9 1089.88
  5023.4 1094.88  5027.7 1094.89  5034.0 1098.48  5037.4 1104.42  5060.3 1102.60
  5105.2 1103.48  5232.0 1104.70  5320.7 1101.31  5390.0 1103.63  5411.6 1108.78
  5439.4 1122.35  5491.1 1138.25  5500.6 1141.18  5529.5 1145.49  5603.3 1148.27
#Mann=7,-1,0
  3804.8    0.08       0  4673.4    0.14       0  4958.2    0.04       0
  5023.4    0.14       0  5105.2    0.08       0  5390.0    0.14       0
  5491.1    0.08       0
Bank Sta=4958.2,5023.4
XS Rating Curve= 0
Exp/Cntr=0.3,0.1

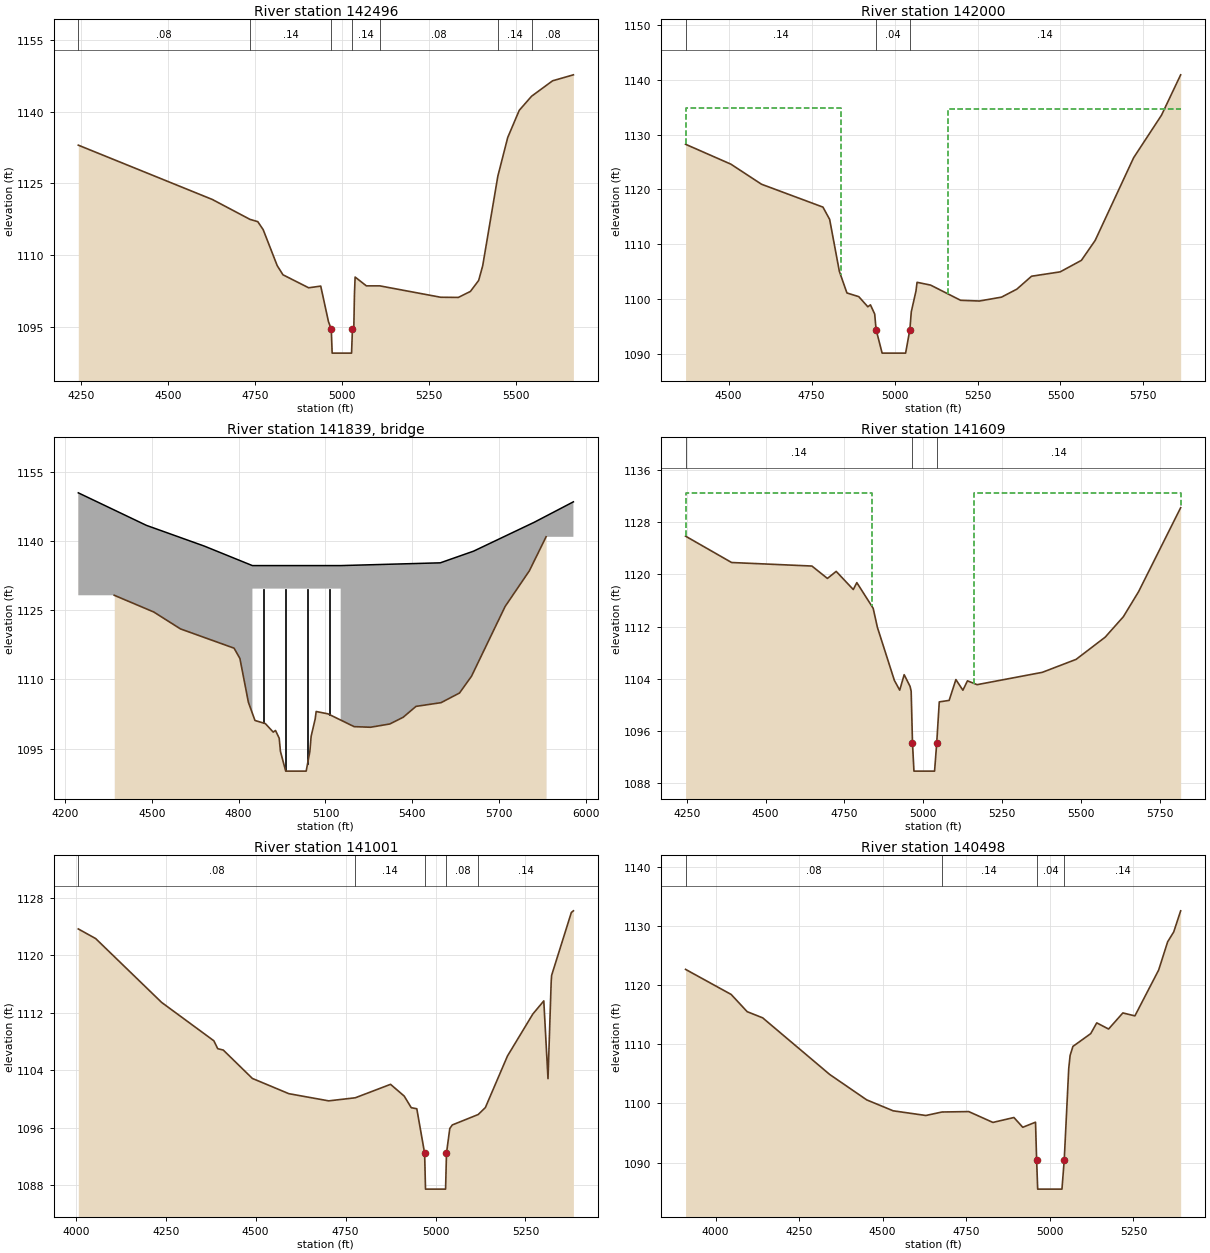
Type RM Length L Ch R = 1,142496,496,496,496
BEGIN DESCRIPTION:
Fisher River 285.0
END DESCRIPTION:
XS GIS Cut Line= 4
      1477343.13       986795.31      1477219.35       986339.58
      1477203.03       985760.24      1477115.26       985399.99
#Sta/Elev= 30
  4242.7 1132.98  4627.6 1121.65  4736.0 1117.49  4758.5 1117.01  4774.0 1115.33
  4814.2 1107.84  4830.8 1105.92  4904.6 1103.21  4939.3 1103.56  4961.6 1096.12
  4969.6 1094.57  4972.1 1089.57  5027.9 1089.57  5030.4 1094.57  5034.3 1094.59
  5036.2 1101.88  5038.1 1105.45  5070.4 1103.61  5109.0 1103.61  5284.1 1101.23
  5334.8 1101.20  5369.4 1102.45  5393.1 1104.74  5404.7 1107.81  5448.2 1126.51
  5476.6 1134.58  5509.7 1140.25  5545.1 1143.19  5605.4 1146.41  5665.3 1147.66
#Mann=7,-1,0
  4242.7    0.08       0  4736.0    0.14       0  4969.6    0.04       0
  5030.4    0.14       0  5109.0    0.08       0  5448.2    0.14       0
  5545.1    0.08       0
Bank Sta=4969.6,5030.4
XS Rating Curve= 0
Exp/Cntr=0.5,0.3

Type RM Length L Ch R = 1,142000,391,391,391
BEGIN DESCRIPTION:
Interstate 77 - US
END DESCRIPTION:
XS GIS Cut Line= 3
      1477967.62       986658.60      1477703.61       986086.59
      1477320.64       985314.00
#Sta/Elev= 30
  4370.0 1128.26  4506.6 1124.63  4598.9 1120.96  4784.1 1116.78  4804.3 1114.54
  4833.6 1105.04  4856.4 1101.09  4892.1 1100.42  4919.4 1098.57  4927.3 1098.92
  4940.1 1097.24  4944.3 1094.40  4962.5 1090.10  5033.3 1090.10  5046.1 1094.40
  5050.4 1097.65  5064.5 1101.45  5067.8 1103.04  5108.6 1102.53  5199.1 1099.75
  5255.5 1099.62  5322.3 1100.33  5368.6 1101.79  5412.8 1104.15  5499.2 1104.95
  5563.1 1107.05  5604.6 1110.69  5720.6 1125.81  5804.4 1133.56  5862.3 1140.95
#Mann=3,-1,0
  4370.0    0.14       0  4944.3    0.04       0  5046.1    0.14       0
#XS Ineff=2,0
    0.00 4837.50 1134.80 5162.50    0.00 1134.70
Permanent Ineff=
       F       F
Bank Sta=4944.3,5046.1
XS Rating Curve= 0
Exp/Cntr=0.5,0.3

Type RM Length L Ch R =3,141839,,,
BEGIN DESCRIPTION:
Interstate 77 - TOR
Structure ID: LDS_FR_11
Approximate Survey Structure
END DESCRIPTION:
Bridge Culvert--1,0,-1,-1,0
Deck Dist Width WeirC Skew NumUp NumDn MinLoCord MaxHiCord MaxSubmerge Is_Ogee
93.5,135,3,,11,11,,,0.95,0,1,1,,,
  4245.9  4481.3  4681.0  4847.5  4847.5  5152.5  5152.5  5496.6  5611.5  5821.5
  5956.6
 1150.49 1143.43 1138.94 1134.70 1134.70 1134.70 1134.70 1135.30 1137.83 1144.11
 1148.54
 1070.10 1070.10 1070.10 1070.10 1129.70 1129.70 1070.10 1070.10 1070.10 1070.10
 1070.10
  4245.9  4481.3  4681.0  4847.5  4847.5  5152.5  5152.5  5496.6  5611.5  5821.5
  5956.6
 1150.49 1143.43 1138.94 1134.70 1134.70 1134.70 1134.70 1135.30 1137.83 1144.11
 1148.54
 1070.10 1070.10 1070.10 1070.10 1129.70 1129.70 1070.10 1070.10 1070.10 1070.10
 1070.10
Pier Skew, UpSta & Num, DnSta & Num=,4885.6,2,4885.6,2,0,0,0,0,0
       3       3
 1100.64 1129.70
       3       3
 1106.87 1129.70
Pier Skew, UpSta & Num, DnSta & Num=,4961.9,2,4961.9,2,0,0,0,0,0
       3       3
 1108.71 1129.70
       3       3
 1102.42 1129.70
Pier Skew, UpSta & Num, DnSta & Num=,5038.1,2,5038.1,2,0,0,0,0,0
       3       3
 1108.17 1129.70
       3       3
 1095.16 1129.70
Pier Skew, UpSta & Num, DnSta & Num=,5114.4,2,5114.4,2,0,0,0,0,0
       3       3
 1102.29 1129.70
       3       3
 1103.33 1129.70
Abutment Skew #Up #Dn=,2,2
  4847.5  4892.5
 1129.70 1100.38
  4847.5  4882.3
 1129.70 1105.73
Abutment Skew #Up #Dn=,2,2
  5107.5  5152.5
 1102.52 1129.70
  5119.5  5152.5
 1102.89 1129.70
BR Coef=1,1,0,1.25,0,,,0.8,0,2,0,
WSPro=,,,, 1 ,,,, 0 ,,,, 0 ,,,,-1 ,-1 ,-1 , 0 , 0 , 0 , 0 , 0
BC Design=,,0,,0,,,,,,

Type RM Length L Ch R = 1,141609,608,608,608
BEGIN DESCRIPTION:
Interstate 77 - DS
END DESCRIPTION:
XS GIS Cut Line= 4
      1478333.30       986548.86      1478037.94       985930.00
      1477959.18       985747.16      1477677.89       985122.70
#Sta/Elev= 30
  4246.5 1125.86  4392.6 1121.82  4647.1 1121.28  4696.3 1119.38  4724.1 1120.46
  4778.3 1117.68  4789.5 1118.74  4841.3 1114.81  4854.7 1111.89  4908.6 1103.75
  4925.5 1102.26  4939.6 1104.63  4958.3 1102.84  4961.8 1102.09  4966.0 1094.15
  4970.6 1089.85  5036.0 1089.85  5042.8 1094.15  5050.9 1100.46  5082.2 1100.69
  5103.6 1103.88  5125.8 1102.25  5140.3 1103.69  5170.8 1103.10  5377.6 1104.99
  5484.8 1106.98  5576.9 1110.38  5634.5 1113.51  5682.9 1117.36  5816.2 1130.22
#Mann=3,-1,0
  4246.5    0.14       0  4966.0    0.04       0  5042.8    0.14       0
#XS Ineff=2,0
    0.00 4837.50 1132.50 5162.50    0.00 1132.50
Permanent Ineff=
       F       F
Bank Sta=4966,5042.8
XS Rating Curve= 0
Exp/Cntr=0.5,0.3

Type RM Length L Ch R = 1,141001,503,503,503
BEGIN DESCRIPTION:
Fisher River 282.0
END DESCRIPTION:
XS GIS Cut Line= 4
      1478454.26       986443.96      1478563.97       985552.22
      1478398.01       985431.26      1478305.35       985175.03
#Sta/Elev= 30
  4006.9 1123.66  4055.2 1122.32  4238.5 1113.44  4383.7 1108.10  4394.5 1107.00
  4409.9 1106.81  4490.8 1102.86  4592.2 1100.74  4703.0 1099.74  4777.0 1100.17
  4874.9 1102.04  4912.8 1100.41  4932.5 1098.79  4947.9 1098.64  4969.6 1092.46
  4972.1 1087.46  5027.9 1087.46  5030.4 1092.46  5039.6 1095.90  5046.6 1096.39
  5118.6 1097.84  5138.5 1098.81  5199.9 1105.98  5270.4 1111.82  5300.9 1113.65
  5312.6 1102.83  5321.4 1116.24  5322.6 1117.19  5377.5 1125.95  5383.2 1126.18
#Mann=5,-1,0
  4006.9    0.08       0  4777.0    0.14       0  4969.6    0.04       0
  5030.4    0.08       0  5118.6    0.14       0
Bank Sta=4969.6,5030.4
XS Rating Curve= 0
Exp/Cntr=0.3,0.1

Type RM Length L Ch R = 1,140498,486,486,486
BEGIN DESCRIPTION:
Fisher River 281.0
END DESCRIPTION:
XS GIS Cut Line= 5
      1478538.66       986446.76      1478744.01       985448.13
      1478839.65       985436.88      1478960.61       985369.37
      1479118.11       985206.25
#Sta/Elev= 30
  3910.3 1122.65  4046.8 1118.41  4094.7 1115.50  4141.0 1114.46  4341.6 1104.89
  4452.2 1100.60  4531.5 1098.75  4629.3 1097.96  4677.3 1098.55  4757.4 1098.62
  4829.8 1096.79  4892.6 1097.62  4919.1 1095.97  4957.2 1096.83  4960.5 1090.52
  4963.7 1085.52  5036.3 1085.52  5043.2 1090.52  5056.6 1105.91  5060.7 1108.11
  5069.1 1109.63  5122.3 1111.79  5140.4 1113.61  5175.8 1112.57  5218.5 1115.29
  5254.5 1114.79  5325.6 1122.54  5352.5 1127.31  5370.6 1128.97  5391.4 1132.54
#Mann=4,-1,0
  3910.3    0.08       0  4677.3    0.14       0  4960.5    0.04       0
  5043.2    0.14       0
Bank Sta=4960.5,5043.2
XS Rating Curve= 0
Exp/Cntr=0.3,0.1

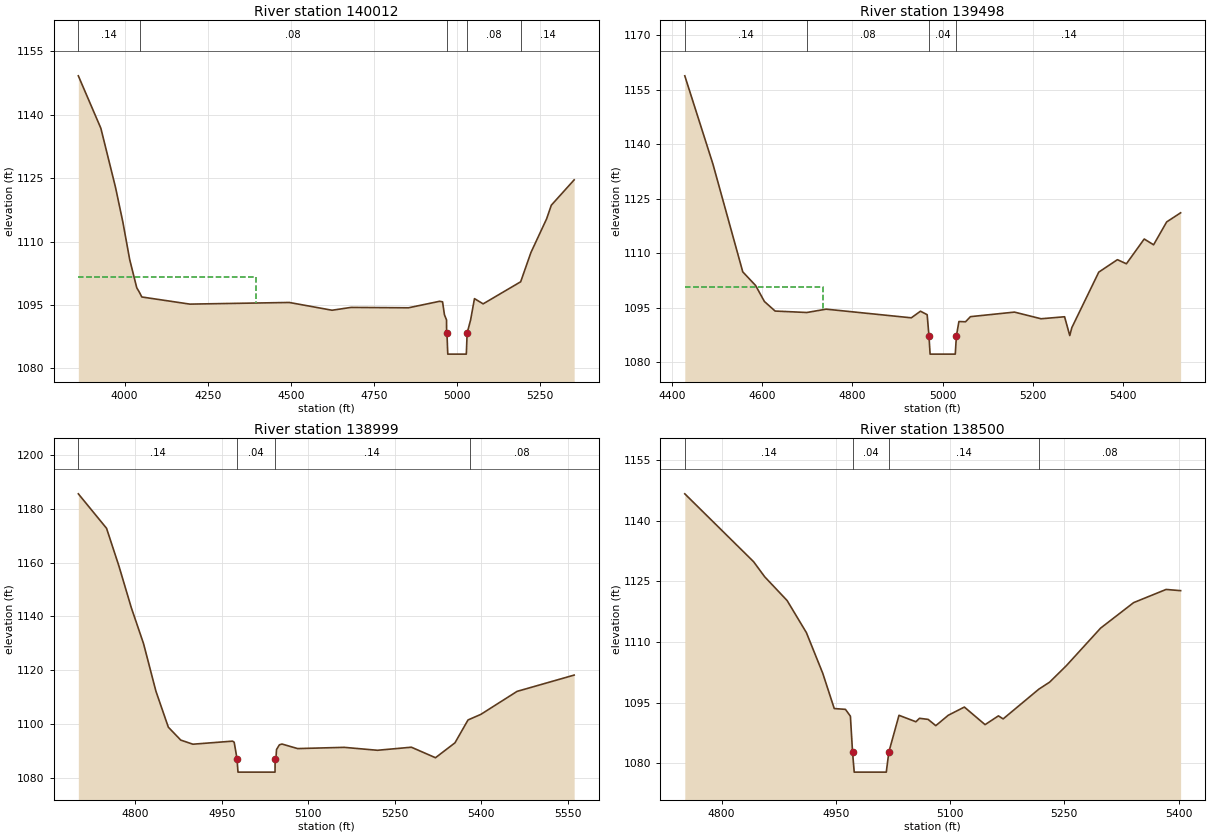
Type RM Length L Ch R = 1,140012,514,514,514
BEGIN DESCRIPTION:
Fisher River 280.0
END DESCRIPTION:
XS GIS Cut Line= 4
      1478935.29       986714.00      1479075.94       985836.33
      1479270.04       985555.03      1479320.68       985299.03
#Sta/Elev= 30
  3860.7 1149.23  3928.5 1136.81  3972.6 1122.81  3994.6 1114.63  4015.3 1105.70
  4036.4 1099.07  4045.2 1097.87  4051.7 1096.87  4196.1 1095.18  4495.3 1095.57
  4624.0 1093.73  4680.9 1094.40  4854.0 1094.31  4947.6 1095.85  4956.4 1095.72
  4962.1 1092.66  4968.4 1091.42  4968.6 1088.38  4969.6 1088.34  4972.1 1083.34
  5027.9 1083.34  5030.4 1088.34  5040.7 1091.40  5052.4 1096.48  5078.5 1095.24
  5191.4 1100.47  5222.2 1107.39  5269.5 1115.38  5283.6 1118.60  5352.3 1124.60
#Mann=5,-1,0
  3860.7    0.14       0  4045.2    0.08       0  4969.6    0.04       0
  5030.4    0.08       0  5191.4    0.14       0
#XS Ineff=2,0
    0.00 4394.10 1101.70               0
Permanent Ineff=
       F       F
Bank Sta=4969.6,5030.4
XS Rating Curve= 0
Exp/Cntr=0.3,0.1

Type RM Length L Ch R = 1,139498,499,499,499
BEGIN DESCRIPTION:
Fisher River 279.0
END DESCRIPTION:
XS GIS Cut Line= 4
      1479886.10       986275.19      1479711.69       985796.95
      1479697.62       985448.13      1479534.49       985270.94
#Sta/Elev= 30
  4428.4 1158.78  4490.8 1134.51  4556.9 1104.90  4585.3 1101.16  4604.9 1096.75
  4628.6 1094.13  4699.0 1093.73  4741.7 1094.65  4930.5 1092.27  4950.8 1094.09
  4965.6 1093.13  4969.6 1087.29  4972.1 1082.29  5027.9 1082.29  5030.4 1087.29
  5036.0 1091.25  5050.6 1091.18  5061.6 1092.59  5159.1 1093.84  5218.0 1092.01
  5270.2 1092.56  5281.7 1087.39  5286.2 1089.56  5346.0 1104.83  5387.3 1108.25
  5407.2 1107.12  5446.7 1113.93  5467.5 1112.34  5496.5 1118.63  5527.4 1121.13
#Mann=4,-1,0
  4428.4    0.14       0  4699.0    0.08       0  4969.6    0.04       0
  5030.4    0.14       0
#XS Ineff=2,0
    0.00 4734.60 1100.87               0
Permanent Ineff=
       F       F
Bank Sta=4969.6,5030.4
XS Rating Curve= 0
Exp/Cntr=0.3,0.1

Type RM Length L Ch R = 1,138999,499,499,499
BEGIN DESCRIPTION:
Fisher River 278.0
END DESCRIPTION:
XS GIS Cut Line= 4
      1480361.47       985602.84      1480178.65       985470.64
      1480012.68       985459.39      1479756.70       985068.39
#Sta/Elev= 30
  4701.6 1185.60  4750.5 1172.78  4771.9 1158.77  4793.3 1143.31  4814.6 1129.87
  4836.1 1112.14  4857.6 1098.76  4879.1 1093.96  4900.2 1092.43  4968.8 1093.57
  4971.7 1093.18  4976.6 1087.04  4978.3 1082.04  5042.5 1082.04  5042.6 1087.04
  5044.0 1087.05  5045.1 1090.45  5050.0 1092.20  5054.6 1092.49  5081.7 1090.80
  5162.3 1091.26  5220.0 1090.17  5278.8 1091.31  5320.6 1087.40  5354.3 1092.94
  5377.0 1101.46  5379.7 1101.71  5399.0 1103.51  5462.0 1112.09  5560.9 1118.15
#Mann=4,-1,0
  4701.6    0.14       0  4976.6    0.04       0  5042.6    0.14       0
  5379.7    0.08       0
Bank Sta=4976.6,5042.6
XS Rating Curve= 0
Exp/Cntr=0.3,0.1

Type RM Length L Ch R = 1,138500,246,246,246
BEGIN DESCRIPTION:
Fisher River 277.0
END DESCRIPTION:
XS GIS Cut Line= 3
      1480384.01       985352.46      1480426.19       985194.96
      1480066.10       984865.82
#Sta/Elev= 30
  4751.8 1146.68  4842.1 1129.89  4856.7 1126.15  4886.1 1120.28  4911.4 1112.35
  4932.9 1102.28  4948.0 1093.55  4962.7 1093.35  4969.2 1091.66  4972.0 1082.82
  4974.2 1077.82  5016.3 1077.82  5019.7 1082.82  5033.0 1091.88  5055.2 1090.28
  5059.9 1091.14  5071.2 1090.87  5081.3 1089.32  5097.6 1091.88  5118.8 1093.92
  5146.0 1089.57  5163.5 1091.74  5169.7 1090.99  5216.6 1098.35  5230.7 1100.08
  5252.6 1104.14  5297.6 1113.44  5341.0 1119.76  5383.6 1123.02  5402.7 1122.72
#Mann=4,-1,0
  4751.8    0.14       0  4972.0    0.04       0  5019.7    0.14       0
  5216.6    0.08       0
Bank Sta=4972,5019.7
XS Rating Curve= 0
Exp/Cntr=0.5,0.3