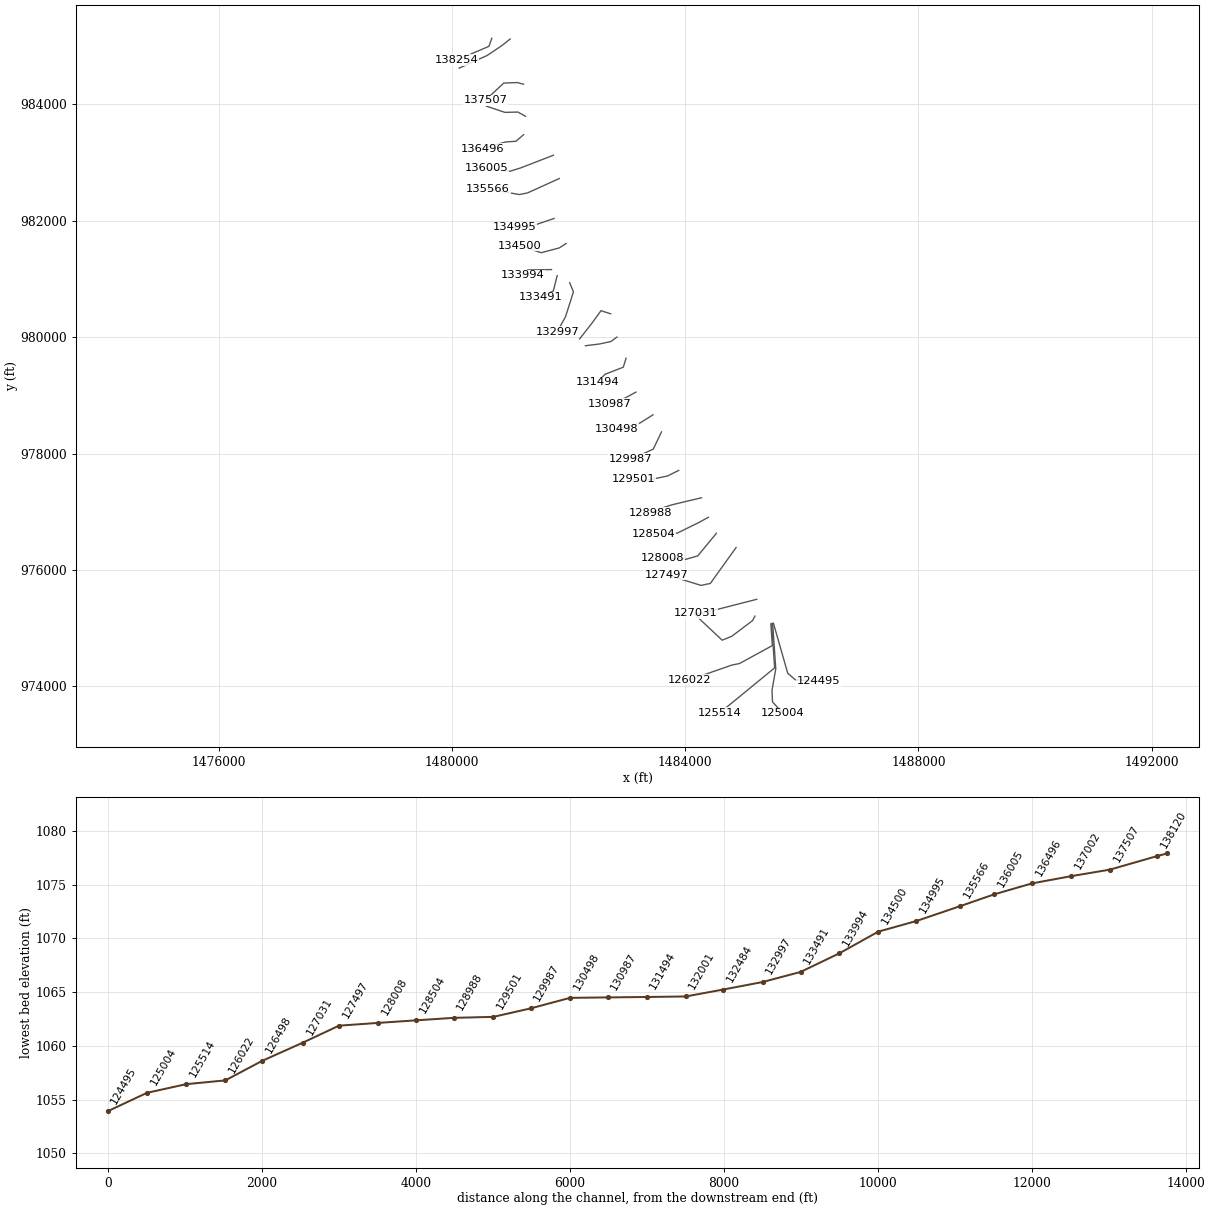
HEC-RAS study Fisher River.prj: Fisher River Limited Detail Study

--- Fisher River.g01 (geometry) --- (continued)

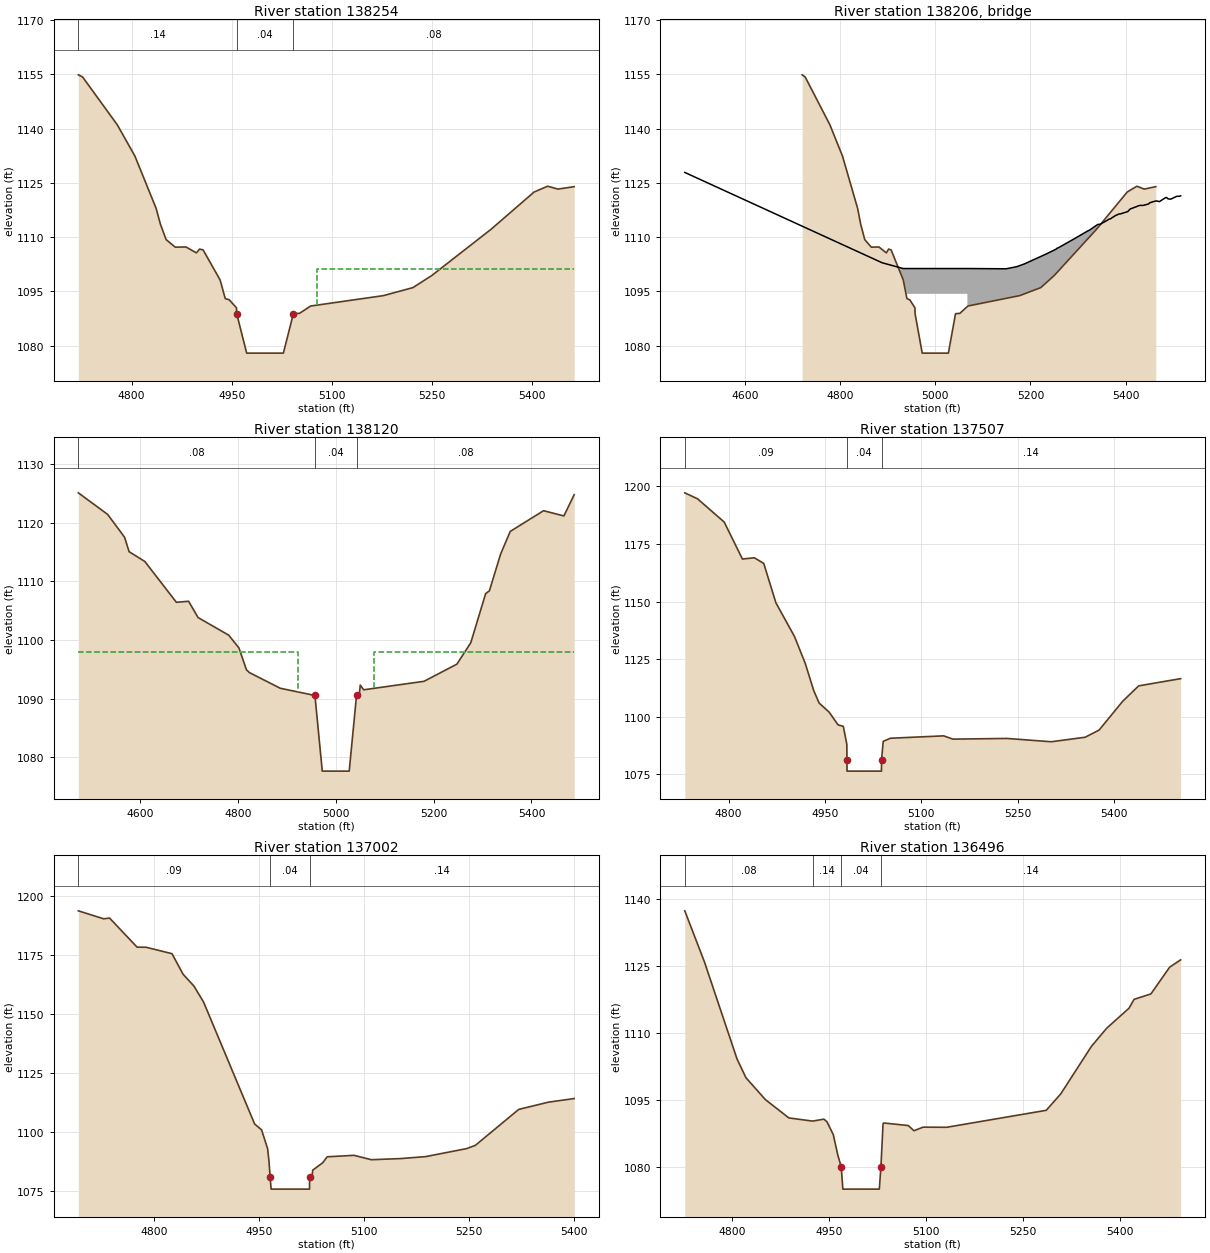
Type RM Length L Ch R = 1,138254,134,134,134
BEGIN DESCRIPTION:
White Dirt Rd - US
END DESCRIPTION:
XS GIS Cut Line= 4
      1480679.37       985130.29      1480630.63       984993.33
      1480497.38       984935.99      1480080.23       984758.96
#Sta/Elev= 30
  4720.0 1154.88  4726.4 1154.29  4778.5 1141.03  4804.9 1132.39  4836.7 1117.93
  4843.1 1113.57  4851.7 1109.30  4865.4 1107.21  4881.4 1107.27  4897.1 1105.63
  4901.8 1106.68  4907.1 1106.46  4932.7 1098.11  4940.3 1092.99  4946.3 1092.65
  4957.2 1090.44  4957.5 1088.80  4972.5 1077.90  5027.5 1077.90  5042.5 1088.80
  5051.6 1088.90  5068.5 1090.93  5177.4 1093.80  5221.8 1096.02  5250.2 1099.38
  5339.0 1112.16  5403.5 1122.46  5423.8 1124.07  5439.4 1123.27  5463.6 1123.95
#Mann=3,-1,0
  4720.0    0.14       0  4957.5    0.04       0  5042.5    0.08       0
#XS Ineff=2,0
    0.00 4922.50 1101.30 5077.50    0.00 1101.30
Permanent Ineff=
       F       F
Bank Sta=4957.5,5042.5
XS Rating Curve= 0
Exp/Cntr=0.5,0.3

Type RM Length L Ch R =3,138206,,,
BEGIN DESCRIPTION:
White Dirt Rd - TOR
Structure ID: LDS_FR_10
Approximate Survey Structure
END DESCRIPTION:
Bridge Culvert--1,0,-1,-1,0
Deck Dist Width WeirC Skew NumUp NumDn MinLoCord MaxHiCord MaxSubmerge Is_Ogee
49,32,3,,51,51,,,0.95,0,1,1,,,
  4473.3  4888.1  4932.5  4932.5  5067.5  5067.5  5148.8  5171.4  5187.2  5232.0
  5236.9  5253.8  5255.3  5260.3  5293.8  5300.2  5320.0  5323.6  5325.5  5341.3
  5344.8  5346.5  5362.5  5364.2  5368.1  5379.2  5383.6  5385.5  5389.5  5404.5
  5404.7  5409.6  5424.8  5426.1  5430.1  5436.9  5448.4  5451.0  5461.4  5466.0
  5468.7  5471.3  5483.8  5486.2  5489.1  5491.5  5495.2  5506.7  5508.9  5512.3
  5515.8
 1127.88 1102.90 1101.30 1101.30 1101.30 1101.30 1101.23 1101.82 1102.57 1105.25
 1105.56 1106.65 1106.86 1107.16 1109.65 1110.14 1111.66 1111.89 1112.03 1113.48
 1113.54 1113.54 1114.70 1114.92 1115.04 1115.99 1116.21 1116.37 1116.42 1117.05
 1117.07 1117.76 1118.51 1118.61 1118.76 1118.75 1119.16 1119.49 1119.92 1120.00
 1119.87 1119.82 1120.88 1120.96 1120.60 1120.53 1120.50 1121.22 1121.30 1121.27
 1121.40
 1057.90 1057.90 1057.90 1094.30 1094.30 1057.90 1057.90 1057.90 1057.90 1057.90
 1057.90 1057.90 1057.90 1057.90 1057.90 1057.90 1057.90 1057.90 1057.90 1057.90
 1057.90 1057.90 1057.90 1057.90 1057.90 1057.90 1057.90 1057.90 1057.90 1057.90
 1057.90 1057.90 1057.90 1057.90 1057.90 1057.90 1057.90 1057.90 1057.90 1057.90
 1057.90 1057.90 1057.90 1057.90 1057.90 1057.90 1057.90 1057.90 1057.90 1057.90
 1057.90
  4473.3  4888.1  4932.5  4932.5  5067.5  5067.5  5148.8  5171.4  5187.2  5232.0
  5236.9  5253.8  5255.3  5260.3  5293.8  5300.2  5320.0  5323.6  5325.5  5341.3
  5344.8  5346.5  5362.5  5364.2  5368.1  5379.2  5383.6  5385.5  5389.5  5404.5
  5404.7  5409.6  5424.8  5426.1  5430.1  5436.9  5448.4  5451.0  5461.4  5466.0
  5468.7  5471.3  5483.8  5486.2  5489.1  5491.5  5495.2  5506.7  5508.9  5512.3
  5515.8
 1127.88 1102.90 1101.30 1101.30 1101.30 1101.30 1101.23 1101.82 1102.57 1105.25
 1105.56 1106.65 1106.86 1107.16 1109.65 1110.14 1111.66 1111.89 1112.03 1113.48
 1113.54 1113.54 1114.70 1114.92 1115.04 1115.99 1116.21 1116.37 1116.42 1117.05
 1117.07 1117.76 1118.51 1118.61 1118.76 1118.75 1119.16 1119.49 1119.92 1120.00
 1119.87 1119.82 1120.88 1120.96 1120.60 1120.53 1120.50 1121.22 1121.30 1121.27
 1121.40
 1057.90 1057.90 1057.90 1094.30 1094.30 1057.90 1057.90 1057.90 1057.90 1057.90
 1057.90 1057.90 1057.90 1057.90 1057.90 1057.90 1057.90 1057.90 1057.90 1057.90
 1057.90 1057.90 1057.90 1057.90 1057.90 1057.90 1057.90 1057.90 1057.90 1057.90
 1057.90 1057.90 1057.90 1057.90 1057.90 1057.90 1057.90 1057.90 1057.90 1057.90
 1057.90 1057.90 1057.90 1057.90 1057.90 1057.90 1057.90 1057.90 1057.90 1057.90
 1057.90
Abutment Skew #Up #Dn=,2,2
  4932.5  4957.5
 1094.30 1089.80
  4932.5  4957.5
 1094.30 1090.55
Abutment Skew #Up #Dn=,2,2
  5042.5  5067.5
 1088.81 1094.30
  5042.5  5067.5
 1090.55 1094.30
BR Coef=1,1,0,1.25,0,,,0.8,0,2,0,
WSPro=,,,, 1 ,,,, 0 ,,,, 0 ,,,,-1 ,-1 ,-1 , 0 , 0 , 0 , 0 , 0
BC Design=,,0,,0,,,,,,

Type RM Length L Ch R = 1,138120,613,613,613
BEGIN DESCRIPTION:
White Dirt Rd - DS
END DESCRIPTION:
XS GIS Cut Line= 4
      1480994.40       985118.99      1480853.77       985006.49
      1480597.79       984834.90      1480119.62       984618.31
#Sta/Elev= 30
  4474.0 1125.11  4533.9 1121.43  4568.4 1117.55  4577.8 1115.07  4609.8 1113.41
  4674.4 1106.44  4699.3 1106.62  4718.7 1103.84  4781.4 1100.83  4802.2 1098.66
  4817.5 1094.94  4823.7 1094.45  4886.7 1091.78  4957.5 1090.55  4972.5 1077.65
  5027.5 1077.65  5042.5 1090.55  5048.5 1090.99  5050.1 1092.32  5057.1 1091.52
  5180.5 1092.97  5247.5 1095.89  5275.9 1099.53  5306.3 1107.91  5314.0 1108.40
  5336.9 1114.66  5356.6 1118.53  5424.7 1122.06  5466.2 1121.17  5487.2 1124.78
#Mann=3,-1,0
  4474.0    0.08       0  4957.5    0.04       0  5042.5    0.08       0
#XS Ineff=2,0
    0.00 4922.50 1098.00 5077.50    0.00 1098.00
Permanent Ineff=
       F       F
Bank Sta=4957.5,5042.5
XS Rating Curve= 0
Exp/Cntr=0.5,0.3

Type RM Length L Ch R = 1,137507,505,505,505
BEGIN DESCRIPTION:
Fisher River 275.0
END DESCRIPTION:
XS GIS Cut Line= 4
      1481225.13       984342.61      1481115.38       984370.75
      1480884.72       984362.31      1480572.47       984069.75
#Sta/Elev= 30
  4731.7 1197.18  4751.6 1194.57  4793.1 1184.48  4821.4 1168.45  4840.0 1168.99
  4854.6 1166.56  4873.5 1149.49  4902.7 1134.71  4919.3 1123.11  4932.4 1111.39
  4940.8 1105.95  4956.5 1101.98  4970.3 1096.47  4978.5 1095.82  4984.0 1088.03
  4984.2 1081.39  4984.3 1076.39  5037.9 1076.39  5038.0 1081.39  5040.7 1089.32
  5051.7 1090.66  5134.7 1091.70  5149.2 1090.28  5233.4 1090.57  5302.3 1089.14
  5354.9 1091.09  5376.7 1094.19  5413.5 1106.71  5438.4 1113.40  5503.7 1116.53
#Mann=3,-1,0
  4731.7    0.09       0  4984.2    0.04       0  5038.0    0.14       0
Bank Sta=4984.2,5038
XS Rating Curve= 0
Exp/Cntr=0.3,0.1

Type RM Length L Ch R = 1,137002,506,506,506
BEGIN DESCRIPTION:
Fisher River 274.0
END DESCRIPTION:
XS GIS Cut Line= 4
      1481258.84       983791.27      1481126.64       983864.40
      1480904.41       983858.78      1480586.49       983965.69
#Sta/Elev= 30
  4691.7 1193.86  4728.0 1190.47  4736.3 1190.80  4775.7 1178.45  4788.6 1178.40
  4825.6 1175.68  4841.5 1166.93  4856.8 1162.00  4870.7 1155.19  4943.7 1103.43
  4953.7 1100.90  4962.3 1092.92  4964.3 1087.44  4965.9 1080.78  4967.3 1075.78
  5022.2 1075.78  5022.3 1080.78  5025.6 1080.82  5026.8 1083.84  5041.0 1086.95
  5047.5 1089.50  5085.8 1090.12  5110.6 1088.26  5152.4 1088.74  5188.3 1089.58
  5246.6 1092.96  5259.2 1094.34  5321.3 1109.61  5363.9 1112.69  5400.5 1114.21
#Mann=3,-1,0
  4691.7    0.09       0  4965.9    0.04       0  5022.3    0.14       0
Bank Sta=4965.9,5022.3
XS Rating Curve= 0
Exp/Cntr=0.3,0.1

Type RM Length L Ch R = 1,136496,491,491,491
BEGIN DESCRIPTION:
Fisher River 273.0
END DESCRIPTION:
XS GIS Cut Line= 4
      1481225.03       983475.02      1481092.88       983362.28
      1480915.66       983351.03      1480516.26       983235.71
#Sta/Elev= 30
  4727.3 1137.26  4757.7 1125.85  4808.1 1104.18  4821.9 1099.99  4851.9 1095.11
  4888.3 1091.01  4925.0 1090.30  4942.5 1090.74  4947.2 1090.16  4957.0 1087.29
  4964.1 1082.65  4969.3 1080.11  4971.8 1075.11  5028.2 1075.11  5030.7 1080.11
  5034.0 1089.74  5035.1 1089.88  5073.0 1089.31  5081.8 1088.15  5095.9 1088.95
  5132.4 1088.92  5286.4 1092.71  5308.9 1096.38  5356.2 1106.97  5379.9 1111.04
  5414.6 1115.53  5422.3 1117.49  5448.4 1118.71  5477.3 1124.67  5494.3 1126.31
#Mann=4,-1,0
  4727.3    0.08       0  4925.0    0.14       0  4969.3    0.04       0
  5030.7    0.14       0
Bank Sta=4969.3,5030.7
XS Rating Curve= 0
Exp/Cntr=0.3,0.1

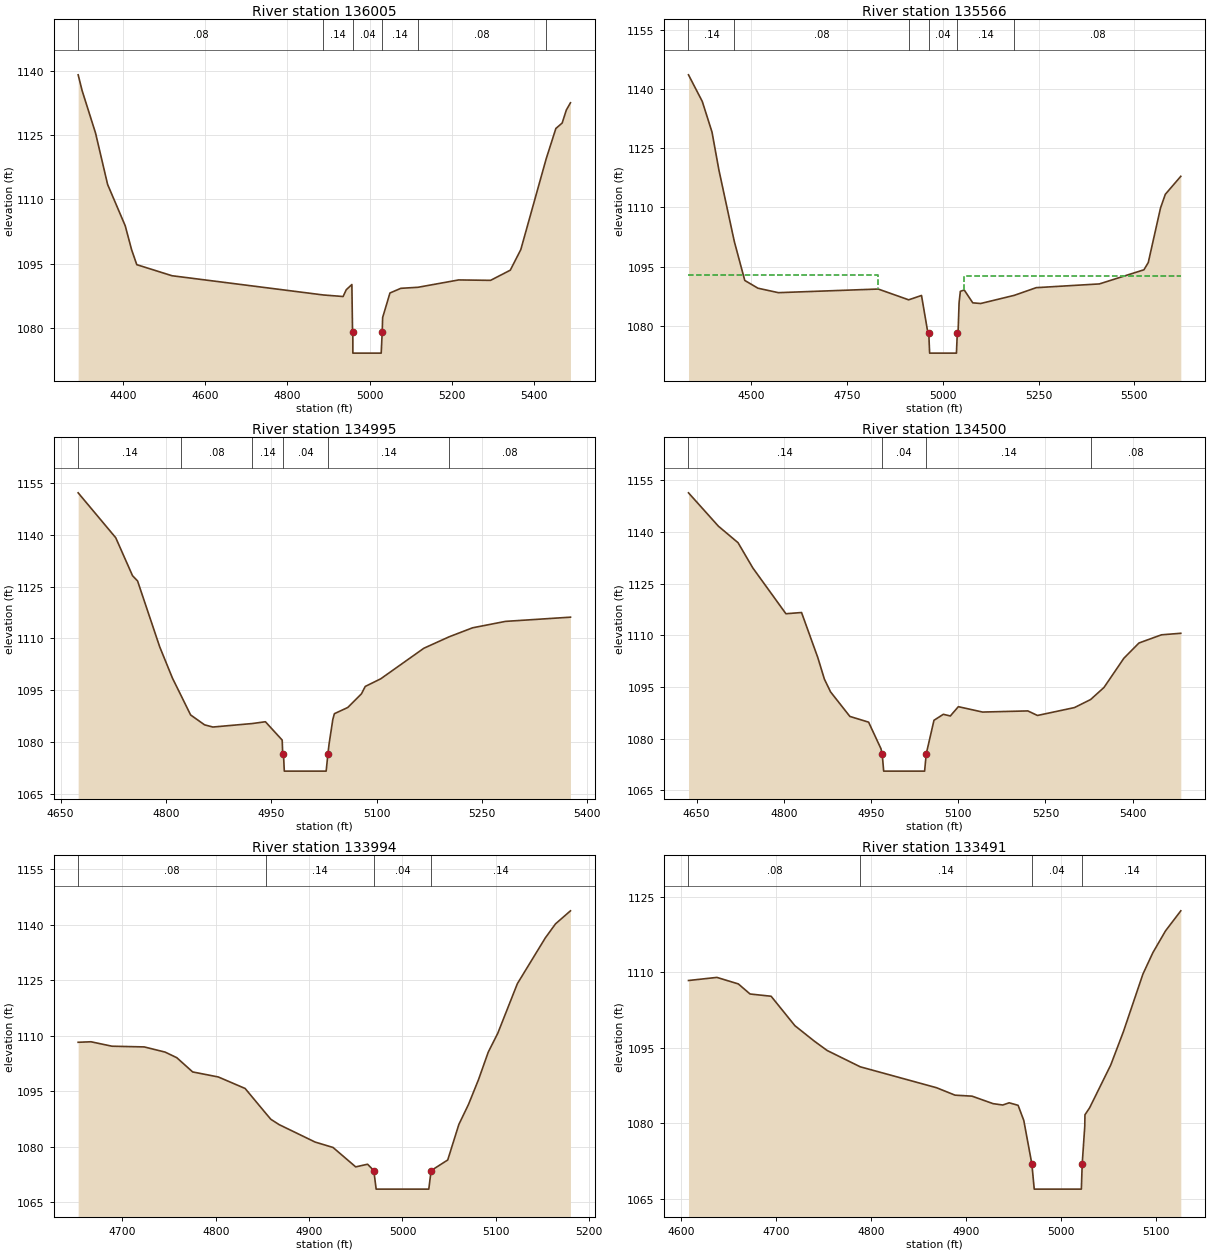
Type RM Length L Ch R = 1,136005,439,439,439
BEGIN DESCRIPTION:
Fisher River 272.0
END DESCRIPTION:
XS GIS Cut Line= 4
      1481737.02       983123.16      1481171.64       982903.76
      1480988.80       982847.50      1480592.13       982895.32
#Sta/Elev= 30
  4291.2 1139.03  4300.9 1135.33  4333.5 1125.44  4362.8 1113.46  4405.7 1103.80
  4421.2 1098.22  4433.8 1094.73  4519.4 1092.15  4887.5 1087.66  4935.6 1087.30
  4943.2 1088.88  4956.9 1090.10  4958.5 1079.09  4959.2 1079.09  4959.3 1074.09
  5028.2 1074.09  5030.7 1079.09  5031.7 1082.39  5049.5 1088.12  5075.9 1089.21
  5118.1 1089.46  5216.6 1091.17  5294.2 1091.07  5342.1 1093.44  5367.7 1098.24
  5429.5 1119.45  5453.0 1126.51  5468.3 1127.78  5478.5 1130.82  5488.5 1132.51
#Mann=6,-1,0
  4291.2    0.08       0  4887.5    0.14       0  4959.2    0.04       0
  5030.7    0.14       0  5118.1    0.08       0  5429.5    0.14       0
Bank Sta=4959.2,5030.7
XS Rating Curve= 0
Exp/Cntr=0.3,0.1

Type RM Length L Ch R = 1,135566,571,571,571
BEGIN DESCRIPTION:
Fisher River 271.0
END DESCRIPTION:
XS GIS Cut Line= 4
      1481838.32       982723.16      1481292.60       982475.62
      1481154.77       982447.49      1480617.44       982540.32
#Sta/Elev= 30
  4336.1 1143.70  4372.1 1136.94  4397.5 1129.15  4415.4 1119.57  4455.7 1101.37
  4483.0 1091.47  4517.5 1089.49  4570.8 1088.36  4831.5 1089.28  4910.9 1086.54
  4944.4 1087.65  4961.3 1078.00  4963.4 1078.00  4965.6 1073.00  5035.6 1073.00
  5037.8 1078.00  5039.8 1078.02  5042.5 1085.82  5045.8 1088.70  5056.0 1089.03
  5078.3 1085.77  5099.0 1085.61  5186.6 1087.68  5243.9 1089.63  5408.7 1090.58
  5525.1 1094.17  5536.4 1096.02  5568.4 1109.89  5580.9 1113.35  5621.3 1117.92
#Mann=6,-1,0
  4336.1    0.14       0  4455.7    0.08       0  4910.9    0.14       0
  4963.4    0.04       0  5037.8    0.14       0  5186.6    0.08       0
#XS Ineff=2,0
    0.00 4832.10 1092.77 5055.30    0.00 1092.51
Permanent Ineff=
       F       F
Bank Sta=4963.4,5037.8
XS Rating Curve= 0
Exp/Cntr=0.3,0.1

Type RM Length L Ch R = 1,134995,495,495,495
BEGIN DESCRIPTION:
Fisher River 270.0
END DESCRIPTION:
XS GIS Cut Line= 3
      1481748.33       982036.79      1481348.86       981901.76
      1481070.33       981882.07
#Sta/Elev= 30
  4675.1 1152.14  4728.6 1139.15  4752.5 1128.17  4759.7 1126.63  4791.2 1107.58
  4809.4 1098.50  4821.3 1093.61  4835.2 1087.87  4855.1 1085.00  4866.9 1084.37
  4923.0 1085.38  4941.7 1085.90  4965.6 1080.59  4966.3 1076.65  4967.4 1076.61
  4968.6 1071.61  5028.2 1071.61  5030.7 1076.61  5032.3 1079.41  5037.7 1086.60
  5039.9 1088.23  5058.9 1090.02  5078.5 1094.00  5083.8 1096.11  5106.0 1098.34
  5167.3 1107.17  5203.4 1110.49  5236.6 1113.08  5283.5 1114.94  5376.0 1116.16
#Mann=6,-1,0
  4675.1    0.14       0  4821.3    0.08       0  4923.0    0.14       0
  4967.4    0.04       0  5030.7    0.14       0  5203.4    0.08       0
Bank Sta=4967.4,5030.7
XS Rating Curve= 0
Exp/Cntr=0.3,0.1

Type RM Length L Ch R = 1,134500,506,506,506
BEGIN DESCRIPTION:
Fisher River 269.0
END DESCRIPTION:
XS GIS Cut Line= 4
      1481953.66       981606.39      1481837.39       981531.19
      1481526.08       981448.86      1481160.43       981572.62
#Sta/Elev= 30
  4636.2 1151.37  4687.7 1141.68  4721.4 1136.90  4746.8 1129.58  4803.7 1116.29
  4830.6 1116.64  4858.5 1103.59  4869.9 1097.31  4880.5 1093.61  4913.7 1086.49
  4945.9 1084.83  4967.1 1077.14  4969.3 1075.62  4971.8 1070.62  5042.2 1070.62
  5045.0 1075.62  5058.3 1085.37  5074.4 1087.11  5086.4 1086.62  5100.2 1089.32
  5141.9 1087.76  5219.7 1088.09  5236.2 1086.77  5299.9 1089.06  5327.6 1091.39
  5350.6 1094.89  5384.9 1103.39  5410.8 1107.80  5449.4 1110.17  5482.7 1110.62
#Mann=4,-1,0
  4636.2    0.14       0  4969.3    0.04       0  5045.0    0.14       0
  5327.6    0.08       0
#XS Ineff=2,0
       0                 5100.20    0.00 1089.32
Permanent Ineff=
       F       F
Bank Sta=4969.3,5045
XS Rating Curve= 0
Exp/Cntr=0.3,0.1

Type RM Length L Ch R = 1,133994,503,503,503
BEGIN DESCRIPTION:
Fisher River 268.0
END DESCRIPTION:
XS GIS Cut Line= 3
      1481703.31       981159.12      1481295.42       981153.50
      1481216.68       981063.51
#Sta/Elev= 30
  4652.5 1108.22  4666.2 1108.36  4688.8 1107.16  4723.3 1106.97  4745.7 1105.57
  4758.2 1104.06  4775.2 1100.22  4802.7 1098.86  4831.4 1095.76  4853.3 1089.13
  4859.0 1087.44  4867.9 1086.00  4906.4 1081.30  4925.6 1079.84  4949.9 1074.60
  4962.6 1075.32  4969.3 1073.60  4971.8 1068.60  5028.2 1068.60  5030.7 1073.60
  5048.5 1076.47  5060.4 1086.04  5070.8 1091.48  5081.5 1098.16  5091.9 1105.56
  5102.1 1110.64  5123.1 1124.03  5153.1 1136.40  5164.0 1140.18  5180.0 1143.69
#Mann=4,-1,0
  4652.5    0.08       0  4853.3    0.14       0  4969.3    0.04       0
  5030.7    0.14       0
Bank Sta=4969.3,5030.7
XS Rating Curve= 0
Exp/Cntr=0.3,0.1

Type RM Length L Ch R = 1,133491,494,494,494
BEGIN DESCRIPTION:
Fisher River 267.0
END DESCRIPTION:
XS GIS Cut Line= 3
      1481801.76       981055.02      1481734.25       980790.62
      1481512.00       980686.53
#Sta/Elev= 30
  4607.8 1108.36  4637.7 1108.98  4660.3 1107.68  4672.6 1105.68  4694.8 1105.23
  4719.8 1099.38  4740.5 1096.27  4753.8 1094.44  4788.6 1091.20  4868.9 1087.04
  4888.4 1085.56  4906.3 1085.36  4928.5 1083.87  4938.6 1083.60  4945.4 1084.04
  4954.8 1083.54  4960.8 1080.53  4969.3 1071.87  4971.8 1066.87  5021.4 1066.87
  5022.3 1071.87  5025.0 1079.39  5025.2 1081.66  5030.1 1083.04  5052.3 1091.54
  5065.7 1098.20  5086.2 1109.63  5096.7 1113.90  5110.0 1118.23  5126.1 1122.22
#Mann=4,-1,0
  4607.8    0.08       0  4788.6    0.14       0  4969.3    0.04       0
  5022.3    0.14       0
Bank Sta=4969.3,5022.3
XS Rating Curve= 0
Exp/Cntr=0.3,0.1

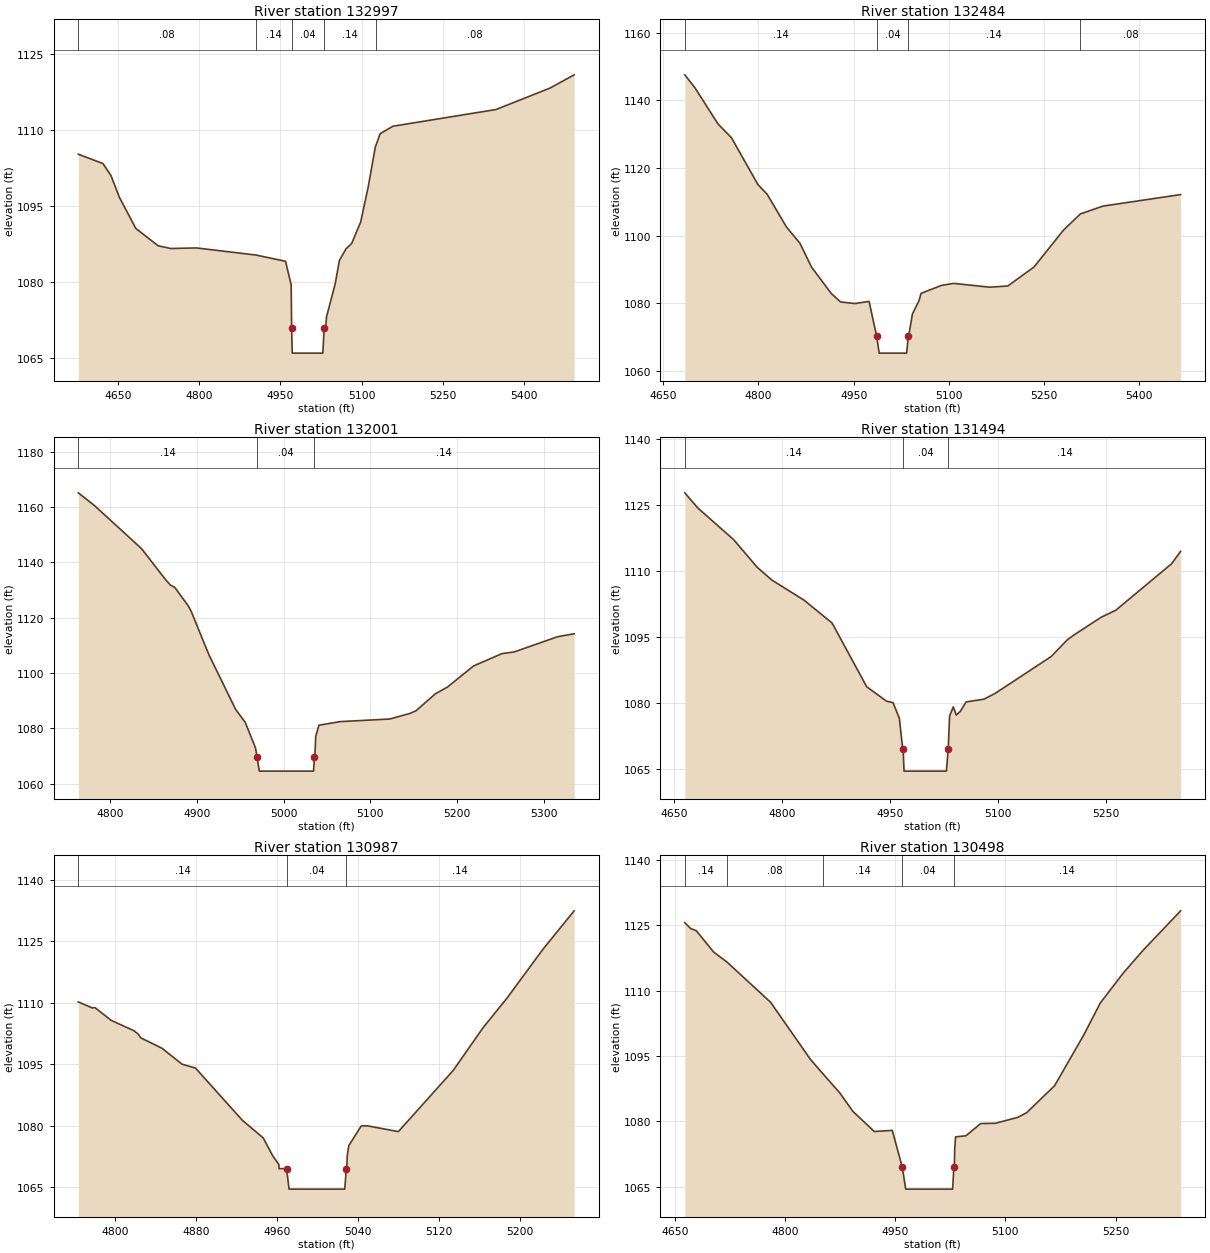
Type RM Length L Ch R = 1,132997,513,513,513
BEGIN DESCRIPTION:
Fisher River 266.0
END DESCRIPTION:
XS GIS Cut Line= 4
      1482015.55       980934.09      1482080.25       980776.55
      1481945.22       980351.79      1481801.75       980090.16
#Sta/Elev= 30
  4577.3 1105.17  4622.7 1103.33  4637.5 1100.96  4652.9 1096.69  4683.3 1090.53
  4724.4 1087.11  4747.6 1086.57  4795.3 1086.68  4905.3 1085.27  4959.4 1084.05
  4969.8 1079.43  4970.7 1070.93  4971.8 1065.93  5028.2 1065.93  5030.7 1070.93
  5033.6 1070.93  5035.0 1073.08  5050.9 1079.54  5058.7 1084.18  5070.9 1086.50
  5081.4 1087.56  5098.0 1091.79  5111.9 1098.71  5125.0 1106.60  5126.4 1106.99
  5133.9 1109.21  5157.5 1110.69  5347.7 1113.99  5447.5 1118.23  5491.7 1120.83
#Mann=5,-1,0
  4577.3    0.08       0  4905.3    0.14       0  4970.7    0.04       0
  5030.7    0.14       0  5126.4    0.08       0
Bank Sta=4970.7,5030.7
XS Rating Curve= 0
Exp/Cntr=0.3,0.1

Type RM Length L Ch R = 1,132484,483,483,483
BEGIN DESCRIPTION:
Fisher River 265.0
END DESCRIPTION:
XS GIS Cut Line= 4
      1482718.84       980399.60      1482552.84       980453.06
      1482406.56       980250.52      1482187.14       979969.21
#Sta/Elev= 30
  4684.0 1147.52  4699.7 1143.77  4736.3 1133.00  4757.5 1128.92  4799.2 1115.07
  4813.9 1112.15  4844.1 1102.54  4865.3 1097.73  4883.6 1090.67  4914.7 1082.87
  4929.3 1080.37  4951.6 1079.89  4974.3 1080.52  4986.2 1070.23  4990.2 1065.23
  5033.4 1065.23  5036.1 1070.23  5036.6 1070.23  5042.6 1076.84  5052.9 1080.73
  5056.2 1082.91  5088.7 1085.28  5107.4 1085.85  5164.3 1084.73  5192.8 1085.08
  5234.1 1090.71  5280.4 1101.58  5307.1 1106.39  5342.6 1108.70  5465.0 1112.11
#Mann=4,-1,0
  4684.0    0.14       0  4986.2    0.04       0  5036.1    0.14       0
  5307.1    0.08       0
Bank Sta=4986.2,5036.1
XS Rating Curve= 0
Exp/Cntr=0.3,0.1

Type RM Length L Ch R = 1,132001,507,507,507
BEGIN DESCRIPTION:
Fisher River 264.0
END DESCRIPTION:
XS GIS Cut Line= 4
      1482825.71       980000.17      1482724.43       979924.21
      1482530.33       979882.01      1482285.61       979851.07
#Sta/Elev= 30
  4763.1 1165.15  4781.8 1160.53  4836.0 1144.98  4863.6 1133.83  4869.2 1131.85
  4874.3 1130.99  4889.7 1124.39  4893.2 1122.37  4913.8 1106.59  4944.5 1086.91
  4955.6 1082.24  4967.5 1072.92  4969.3 1069.59  4971.8 1064.59  5034.4 1064.59
  5035.4 1069.59  5035.9 1069.59  5036.9 1077.11  5040.6 1081.18  5065.2 1082.48
  5122.3 1083.42  5145.6 1085.44  5152.7 1086.43  5174.8 1092.50  5188.9 1094.97
  5218.9 1102.58  5251.9 1107.07  5265.9 1107.66  5316.2 1113.19  5335.0 1114.22
#Mann=3,-1,0
  4763.1    0.14       0  4969.3    0.04       0  5035.4    0.14       0
Bank Sta=4969.3,5035.4
XS Rating Curve= 0
Exp/Cntr=0.3,0.1

Type RM Length L Ch R = 1,131494,507,507,507
BEGIN DESCRIPTION:
Fisher River 263.0
END DESCRIPTION:
XS GIS Cut Line= 4
      1482983.23       979637.29      1482935.41       979482.56
      1482623.16       979361.60      1482490.95       979223.76
#Sta/Elev= 30
  4665.3 1127.81  4683.4 1124.36  4733.1 1117.16  4765.8 1110.87  4786.4 1107.94
  4830.8 1103.40  4869.6 1098.21  4917.7 1083.71  4945.2 1080.44  4954.2 1080.10
  4962.9 1076.57  4967.6 1069.55  4968.2 1069.54  4969.4 1064.54  5028.2 1064.54
  5030.7 1069.54  5032.6 1077.04  5037.7 1079.15  5041.9 1077.28  5047.4 1078.11
  5055.6 1080.28  5080.1 1080.89  5095.3 1082.16  5173.5 1090.59  5195.9 1094.39
  5205.5 1095.54  5243.2 1099.55  5263.1 1101.11  5340.4 1111.66  5353.1 1114.51
#Mann=3,-1,0
  4665.3    0.14       0  4968.2    0.04       0  5030.7    0.14       0
Bank Sta=4968.2,5030.7
XS Rating Curve= 0
Exp/Cntr=0.3,0.1

Type RM Length L Ch R = 1,130987,489,489,489
BEGIN DESCRIPTION:
Fisher River 262.0
END DESCRIPTION:
XS GIS Cut Line= 4
      1483151.99       979054.97      1483008.55       978976.22
      1482896.03       978919.96      1482707.59       978852.46
#Sta/Elev= 30
  4763.7 1110.17  4777.4 1108.71  4780.2 1108.77  4796.1 1105.67  4818.6 1103.15
  4823.1 1102.25  4825.2 1101.43  4846.4 1098.85  4866.1 1094.98  4879.4 1094.03
  4925.5 1081.34  4946.3 1076.98  4955.7 1072.61  4961.7 1070.49  4961.9 1069.50
  4969.3 1069.50  4971.8 1064.50  5026.8 1064.50  5028.3 1069.50  5028.7 1069.50
  5029.3 1072.78  5030.8 1075.13  5043.1 1079.93  5049.6 1079.92  5079.7 1078.53
  5133.9 1093.46  5163.1 1103.79  5187.4 1111.23  5222.5 1123.02  5253.3 1132.39
#Mann=3,-1,0
  4763.7    0.14       0  4969.3    0.04       0  5028.3    0.14       0
Bank Sta=4969.3,5028.3
XS Rating Curve= 0
Exp/Cntr=0.3,0.1

Type RM Length L Ch R = 1,130498,511,511,511
BEGIN DESCRIPTION:
Fisher River 261.0
END DESCRIPTION:
XS GIS Cut Line= 4
      1483444.56       978663.97      1483211.08       978517.70
      1483084.50       978481.13      1482822.86       978424.86
#Sta/Elev= 30
  4663.6 1125.65  4671.6 1124.30  4679.3 1123.79  4702.8 1118.91  4720.6 1116.66
  4780.4 1107.37  4834.4 1094.30  4851.7 1090.93  4874.7 1086.53  4892.4 1082.31
  4921.6 1077.69  4946.0 1077.95  4959.7 1069.46  4964.3 1064.46  5028.2 1064.46
  5029.8 1069.46  5030.5 1069.46  5031.0 1073.68  5032.2 1076.46  5046.3 1076.71
  5066.3 1079.52  5086.4 1079.58  5116.7 1080.93  5128.9 1082.01  5166.9 1088.19
  5206.8 1099.89  5229.1 1107.18  5260.5 1114.09  5287.1 1119.24  5338.5 1128.36
#Mann=5,-1,0
  4663.6    0.14       0  4720.6    0.08       0  4851.7    0.14       0
  4959.7    0.04       0  5029.8    0.14       0
Bank Sta=4959.7,5029.8
XS Rating Curve= 0
Exp/Cntr=0.3,0.1

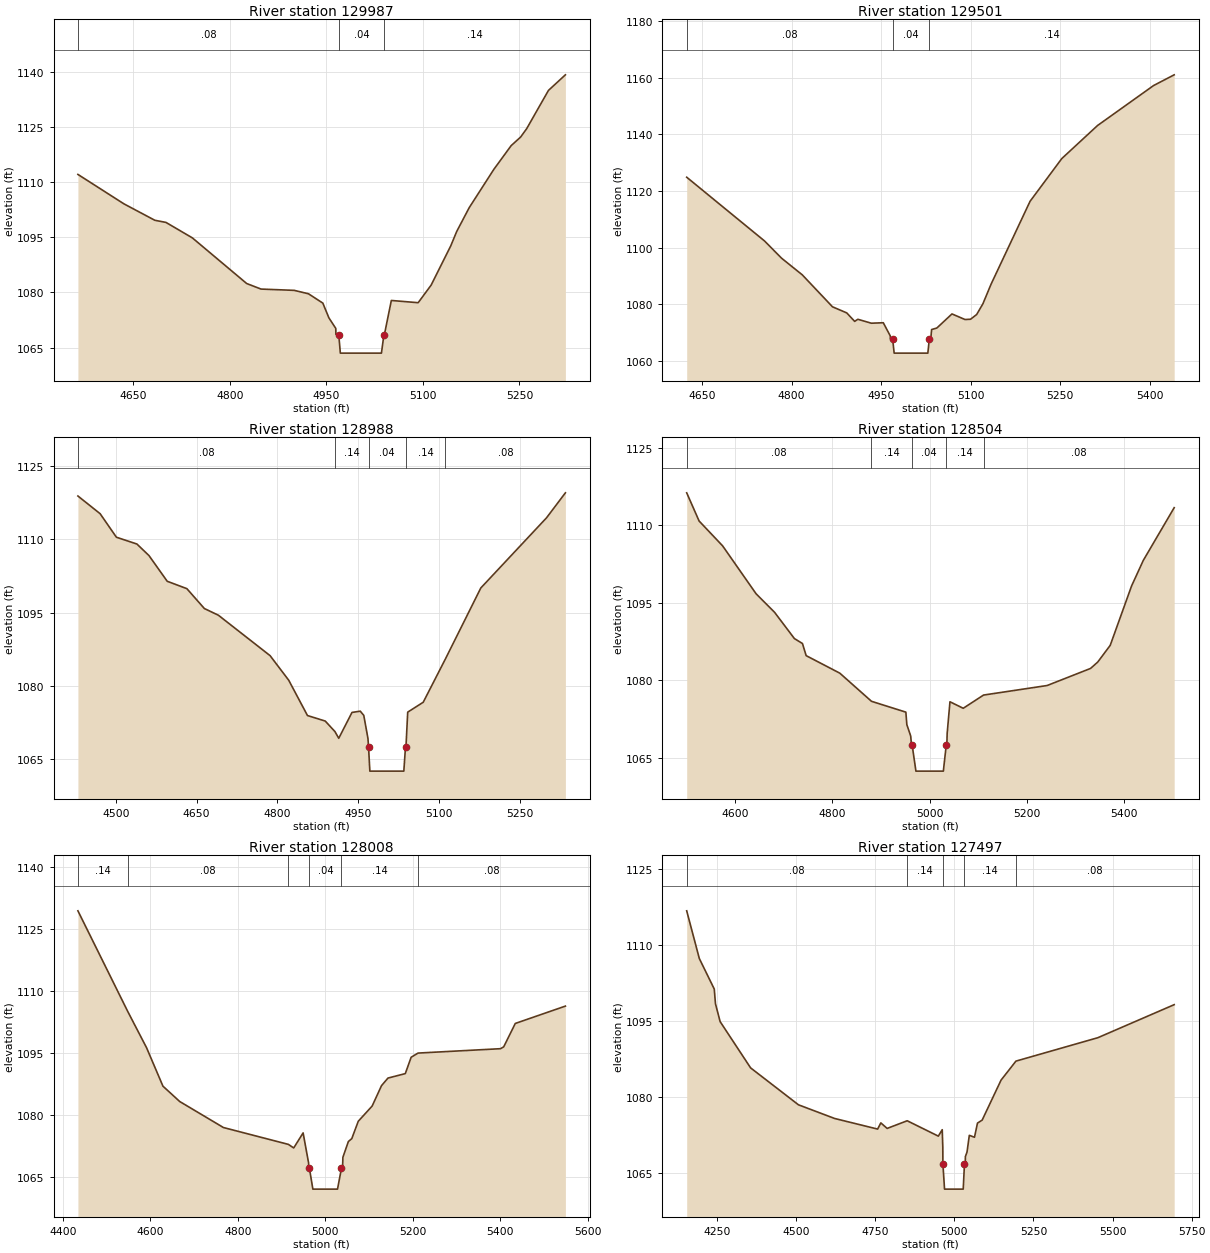
Type RM Length L Ch R = 1,129987,486,486,486
BEGIN DESCRIPTION:
Fisher River 260.0
END DESCRIPTION:
XS GIS Cut Line= 4
      1483590.83       978371.40      1483450.19       978076.05
      1483284.22       978000.10      1483053.51       977910.07
#Sta/Elev= 30
  4564.1 1112.11  4635.5 1104.11  4683.6 1099.63  4700.9 1099.05  4741.9 1094.84
  4826.3 1082.42  4848.6 1080.91  4900.1 1080.56  4922.3 1079.63  4944.6 1077.09
  4954.0 1073.08  4964.7 1070.21  4964.9 1068.59  4969.3 1068.48  4971.8 1063.48
  5035.6 1063.48  5039.5 1068.48  5040.3 1068.58  5051.0 1077.81  5092.7 1077.20
  5112.8 1081.98  5143.3 1092.66  5152.5 1096.56  5172.0 1103.07  5210.3 1113.50
  5237.1 1119.93  5251.9 1122.29  5261.3 1124.57  5295.1 1134.97  5321.4 1139.21
#Mann=3,-1,0
  4564.1    0.08       0  4969.3    0.04       0  5039.5    0.14       0
Bank Sta=4969.3,5039.5
XS Rating Curve= 0
Exp/Cntr=0.3,0.1

Type RM Length L Ch R = 1,129501,513,513,513
BEGIN DESCRIPTION:
Fisher River 259.0
END DESCRIPTION:
XS GIS Cut Line= 4
      1483886.20       977710.36      1483694.92       977614.72
      1483292.66       977530.33      1483104.16       977561.28
#Sta/Elev= 30
  4624.6 1124.85  4755.0 1102.30  4783.3 1096.25  4818.0 1090.36  4868.6 1079.06
  4892.5 1076.90  4905.7 1073.91  4911.1 1074.65  4933.6 1073.26  4953.6 1073.43
  4965.3 1068.78  4965.5 1067.69  4969.3 1067.69  4971.8 1062.69  5028.2 1062.69
  5030.7 1067.69  5033.1 1067.69  5034.5 1071.02  5043.3 1071.57  5068.6 1076.54
  5090.4 1074.57  5099.6 1074.66  5109.9 1076.33  5120.4 1080.15  5134.0 1087.04
  5199.3 1116.34  5252.4 1131.44  5312.3 1143.13  5406.0 1157.24  5440.5 1161.03
#Mann=3,-1,0
  4624.6    0.08       0  4969.3    0.04       0  5030.7    0.14       0
Bank Sta=4969.3,5030.7
XS Rating Curve= 0
Exp/Cntr=0.3,0.1

Type RM Length L Ch R = 1,128988,484,484,484
BEGIN DESCRIPTION:
Fisher River 258.0
END DESCRIPTION:
XS GIS Cut Line= 4
      1484277.22       977240.59      1483770.87       977119.63
      1483613.35       977068.99      1483410.78       976984.59
#Sta/Elev= 30
  4429.5 1118.81  4470.8 1115.19  4501.0 1110.39  4539.1 1109.00  4561.5 1106.64
  4595.4 1101.39  4631.9 1099.88  4664.4 1095.82  4690.5 1094.45  4786.5 1086.19
  4821.1 1081.17  4855.9 1073.96  4888.9 1072.83  4906.9 1070.69  4914.0 1069.31
  4938.6 1074.59  4954.0 1074.85  4960.5 1073.99  4968.3 1069.25  4969.3 1067.60
  4971.8 1062.60  5034.9 1062.60  5038.0 1067.60  5038.9 1067.60  5042.1 1074.65
  5070.9 1076.67  5112.0 1085.49  5177.9 1100.02  5300.0 1114.36  5335.0 1119.46
#Mann=5,-1,0
  4429.5    0.08       0  4906.9    0.14       0  4969.3    0.04       0
  5038.0    0.14       0  5112.0    0.08       0
Bank Sta=4969.3,5038
XS Rating Curve= 0
Exp/Cntr=0.3,0.1

Type RM Length L Ch R = 1,128504,496,496,496
BEGIN DESCRIPTION:
Fisher River 257.0
END DESCRIPTION:
XS GIS Cut Line= 4
      1484395.34       976905.83      1484226.58       976813.01
      1483860.89       976632.97      1483458.64       976618.91
#Sta/Elev= 30
  4500.3 1116.30  4525.8 1110.84  4574.2 1106.02  4643.0 1096.74  4681.2 1093.13
  4721.8 1088.06  4738.4 1087.10  4746.0 1084.75  4815.3 1081.35  4880.4 1075.90
  4951.1 1073.80  4953.1 1071.38  4961.0 1069.19  4962.8 1067.37  4964.1 1067.37
  4971.8 1062.37  5028.2 1062.37  5034.1 1067.37  5035.4 1067.39  5036.0 1069.62
  5041.8 1075.81  5069.1 1074.55  5110.9 1077.11  5241.7 1078.96  5331.0 1082.27
  5345.8 1083.51  5371.4 1086.74  5415.4 1098.26  5439.5 1103.21  5503.0 1113.42
#Mann=5,-1,0
  4500.3    0.08       0  4880.4    0.14       0  4964.1    0.04       0
  5034.1    0.14       0  5110.9    0.08       0
Bank Sta=4964.1,5034.1
XS Rating Curve= 0
Exp/Cntr=0.3,0.1

Type RM Length L Ch R = 1,128008,511,511,511
BEGIN DESCRIPTION:
Fisher River 256.0
END DESCRIPTION:
XS GIS Cut Line= 4
      1484533.20       976630.16      1484212.52       976241.97
      1484007.17       976182.89      1483610.57       976213.83
#Sta/Elev= 30
  4434.4 1129.49  4548.1 1105.19  4591.4 1096.36  4628.9 1087.05  4667.2 1083.34
  4767.2 1077.04  4915.8 1072.96  4928.0 1072.10  4949.5 1075.74  4962.0 1068.49
  4962.3 1067.13  4964.0 1067.13  4971.8 1062.13  5028.2 1062.13  5037.1 1067.13
  5039.7 1067.15  5040.5 1069.84  5053.0 1073.65  5060.8 1074.35  5075.7 1078.56
  5107.4 1082.24  5128.8 1087.17  5143.6 1089.01  5183.2 1090.09  5196.6 1094.05
  5212.4 1095.06  5401.0 1096.12  5408.3 1096.57  5434.8 1102.23  5549.4 1106.43
#Mann=6,-1,0
  4434.4    0.14       0  4548.1    0.08       0  4915.8    0.14       0
  4964.0    0.04       0  5037.1    0.14       0  5212.4    0.08       0
Bank Sta=4964,5037.1
XS Rating Curve= 0
Exp/Cntr=0.3,0.1

Type RM Length L Ch R = 1,127497,466,466,466
BEGIN DESCRIPTION:
Fisher River 255.0
END DESCRIPTION:
XS GIS Cut Line= 4
      1484870.79       976385.47      1484429.12       975769.38
      1484268.78       975735.62      1483678.04       975918.47
#Sta/Elev= 30
  4154.5 1116.70  4194.4 1107.30  4241.6 1101.29  4245.4 1098.39  4260.1 1094.88
  4356.4 1085.76  4507.7 1078.48  4621.9 1075.79  4757.8 1073.70  4767.9 1074.92
  4787.9 1073.83  4851.2 1075.34  4949.6 1072.31  4961.9 1073.58  4963.7 1070.12
  4964.0 1066.87  4969.2 1061.87  5028.2 1061.87  5032.2 1066.87  5034.9 1066.90
  5035.0 1068.27  5040.2 1069.17  5047.5 1072.47  5063.8 1072.09  5073.3 1074.88
  5088.1 1075.47  5147.8 1083.35  5194.8 1087.09  5453.5 1091.70  5694.8 1098.21
#Mann=5,-1,0
  4154.5    0.08       0  4851.2    0.14       0  4964.0    0.04       0
  5032.2    0.14       0  5194.8    0.08       0
Bank Sta=4964,5032.2
XS Rating Curve= 0
Exp/Cntr=0.3,0.1

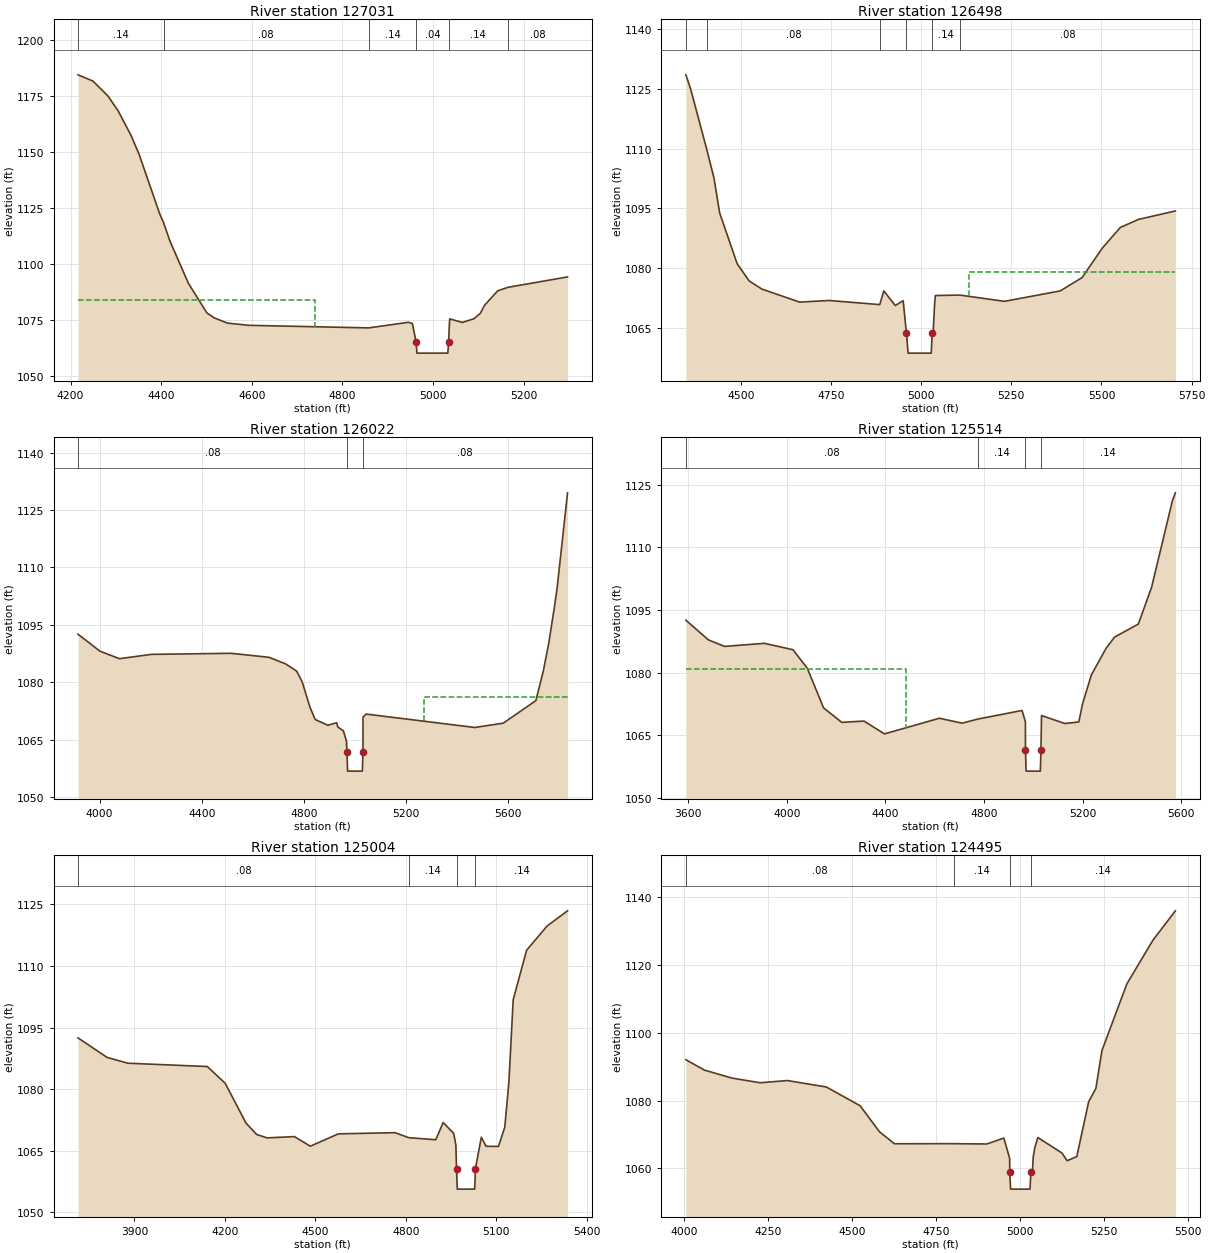
Type RM Length L Ch R = 1,127031,533,533,533
BEGIN DESCRIPTION:
Fisher River 254.0
END DESCRIPTION:
XS GIS Cut Line= 3
      1485225.17       975496.50      1484268.78       975251.78
      1484175.95       975257.41
#Sta/Elev= 30
  4216.4 1184.56  4249.2 1181.80  4282.4 1175.14  4305.0 1168.47  4333.7 1157.38
  4351.4 1148.96  4396.5 1122.57  4405.2 1118.53  4419.7 1110.11  4460.2 1091.41
  4500.6 1078.29  4516.9 1076.04  4546.2 1073.71  4592.6 1072.72  4857.7 1071.56
  4945.6 1074.07  4954.2 1073.52  4962.5 1065.30  4964.3 1060.30  5032.4 1060.30
  5034.2 1065.30  5035.9 1073.50  5036.8 1075.59  5064.5 1074.00  5090.2 1075.66
  5104.3 1078.10  5113.5 1081.67  5142.6 1088.13  5165.4 1089.70  5296.6 1094.32
#Mann=6,-1,0
  4216.4    0.14       0  4405.2    0.08       0  4857.7    0.14       0
  4962.5    0.04       0  5034.2    0.14       0  5165.4    0.08       0
#XS Ineff=2,0
    0.00 4739.90 1083.82               0
Permanent Ineff=
       F       F
Bank Sta=4962.5,5034.2
XS Rating Curve= 0
Exp/Cntr=0.3,0.1

Type RM Length L Ch R = 1,126498,476,476,476
BEGIN DESCRIPTION:
Fisher River 253.0
END DESCRIPTION:
XS GIS Cut Line= 5
      1485194.25       975208.16      1485152.32       975130.21
      1484797.63       974862.18      1484631.66       974794.67
      1484161.91       975236.28
#Sta/Elev= 30
  4347.9 1128.55  4361.0 1125.05  4407.1 1109.38  4425.9 1102.59  4441.6 1093.84
  4490.1 1081.08  4523.2 1076.75  4558.7 1074.69  4663.2 1071.42  4745.4 1071.82
  4885.4 1070.79  4896.7 1074.23  4928.3 1070.56  4950.3 1071.77  4959.4 1063.59
  4964.0 1058.59  5028.2 1058.59  5030.7 1063.59  5034.0 1063.64  5034.2 1065.23
  5037.6 1070.99  5039.5 1073.07  5107.3 1073.18  5231.3 1071.61  5385.7 1074.23
  5446.3 1077.58  5502.5 1085.01  5552.5 1090.19  5602.5 1092.20  5704.9 1094.33
#Mann=6,-1,0
  4347.9    0.14       0  4407.1    0.08       0  4885.4    0.14       0
  4959.4    0.04       0  5030.7    0.14       0  5107.3    0.08       0
#XS Ineff=2,0
       0                 5132.70    0.00 1079.08
Permanent Ineff=
       F       F
Bank Sta=4959.4,5030.7
XS Rating Curve= 0
Exp/Cntr=0.3,0.1

Type RM Length L Ch R = 1,126022,508,508,508
BEGIN DESCRIPTION:
Fisher River 252.0
END DESCRIPTION:
XS GIS Cut Line= 5
      1485467.12       975073.20      1485492.44       974701.84
      1484930.58       974394.19      1484797.63       974367.09
      1484071.90       974113.93
#Sta/Elev= 30
  3915.4 1092.55  4001.0 1088.13  4077.6 1086.15  4202.6 1087.28  4515.0 1087.56
  4662.8 1086.52  4728.5 1084.79  4771.3 1082.93  4793.1 1080.15  4823.9 1073.45
  4844.2 1070.27  4894.2 1068.75  4928.2 1069.43  4932.5 1068.34  4954.5 1067.31
  4966.8 1064.59  4968.6 1061.78  4971.1 1056.78  5028.9 1056.78  5031.4 1061.78
  5031.6 1070.87  5043.3 1071.69  5469.3 1068.18  5581.1 1069.32  5708.5 1075.20
  5737.7 1082.95  5759.1 1090.26  5781.1 1099.64  5792.2 1104.87  5832.5 1129.48
#Mann=3,-1,0
  3915.4    0.08       0  4968.6    0.04       0  5031.4    0.08       0
#XS Ineff=2,0
       0                 5270.50    0.00 1076.23
Permanent Ineff=
       F       F
Bank Sta=4968.6,5031.4
XS Rating Curve= 0
Exp/Cntr=0.3,0.1

Type RM Length L Ch R = 1,125514,510,510,510
BEGIN DESCRIPTION:
Fisher River 251.0
END DESCRIPTION:
XS GIS Cut Line= 4
      1485481.19       975078.76      1485531.82       974319.27
      1484882.02       973785.36      1484583.81       973543.42
#Sta/Elev= 30
  3590.6 1092.57  3682.2 1087.84  3747.7 1086.28  3908.9 1087.02  4025.1 1085.49
  4083.3 1081.06  4149.4 1071.57  4223.1 1068.10  4313.4 1068.41  4396.5 1065.34
  4619.4 1069.09  4711.8 1067.90  4776.5 1068.91  4954.8 1070.95  4968.3 1068.23
  4968.6 1061.43  4971.1 1056.43  5028.9 1056.43  5031.4 1061.43  5033.7 1069.74
  5128.1 1067.83  5184.9 1068.19  5200.5 1072.60  5236.1 1079.47  5295.9 1085.85
  5329.9 1088.50  5426.6 1091.63  5480.3 1100.43  5564.7 1121.14  5576.8 1123.04
#Mann=4,-1,0
  3590.6    0.08       0  4776.5    0.14       0  4968.6    0.04       0
  5031.4    0.14       0
#XS Ineff=2,0
    0.00 4482.20 1080.78               0
Permanent Ineff=
       F       F
Bank Sta=4968.6,5031.4
XS Rating Curve= 0
Exp/Cntr=0.3,0.1

Type RM Length L Ch R = 1,125004,509,509,509
BEGIN DESCRIPTION:
Fisher River 250.0
END DESCRIPTION:
XS GIS Cut Line= 5
      1485498.07       975084.43      1485551.52       974302.39
      1485486.82       973931.91      1485495.26       973735.00
      1485675.32       973537.78
#Sta/Elev= 30
  3712.8 1092.48  3808.9 1087.74  3877.7 1086.31  4141.8 1085.50  4201.2 1081.41
  4270.0 1071.73  4305.6 1068.93  4340.3 1068.11  4430.9 1068.42  4483.5 1066.08
  4576.5 1069.09  4764.7 1069.38  4810.5 1068.15  4899.9 1067.66  4924.2 1071.86
  4959.2 1069.21  4966.5 1066.32  4968.6 1060.62  4971.1 1055.62  5028.9 1055.62
  5031.4 1060.62  5050.9 1068.28  5066.4 1066.06  5107.7 1066.03  5128.7 1070.70
  5142.4 1081.71  5156.6 1101.77  5201.1 1113.84  5268.7 1119.72  5336.9 1123.45
#Mann=4,-1,0
  3712.8    0.08       0  4810.5    0.14       0  4968.6    0.04       0
  5031.4    0.14       0
Bank Sta=4968.6,5031.4
XS Rating Curve= 0
Exp/Cntr=0.3,0.1

Type RM Length L Ch R = 1,124495,499,499,499
BEGIN DESCRIPTION:
Fisher River 249.0
END DESCRIPTION:
XS GIS Cut Line= 4
      1485512.12       975084.45      1485756.87       974227.28
      1485886.26       974114.76      1486280.05       974089.44
#Sta/Elev= 30
  4004.2 1092.04  4059.4 1088.98  4141.2 1086.63  4225.2 1085.25  4306.6 1085.90
  4422.5 1084.00  4523.1 1078.47  4580.7 1070.81  4625.3 1067.28  4802.4 1067.30
  4900.3 1067.21  4950.9 1068.95  4968.2 1063.02  4968.6 1058.91  4971.1 1053.91
  5028.9 1053.91  5031.4 1058.91  5036.1 1059.05  5038.4 1063.36  5043.2 1066.14
  5052.2 1069.10  5123.9 1064.57  5139.5 1062.28  5168.2 1063.50  5203.6 1079.68
  5225.0 1083.57  5243.1 1094.74  5317.2 1114.36  5394.8 1127.23  5461.7 1135.90
#Mann=4,-1,0
  4004.2    0.08       0  4802.4    0.14       0  4968.6    0.04       0
  5031.4    0.14       0
Bank Sta=4968.6,5031.4
XS Rating Curve= 0
Exp/Cntr=0.3,0.1