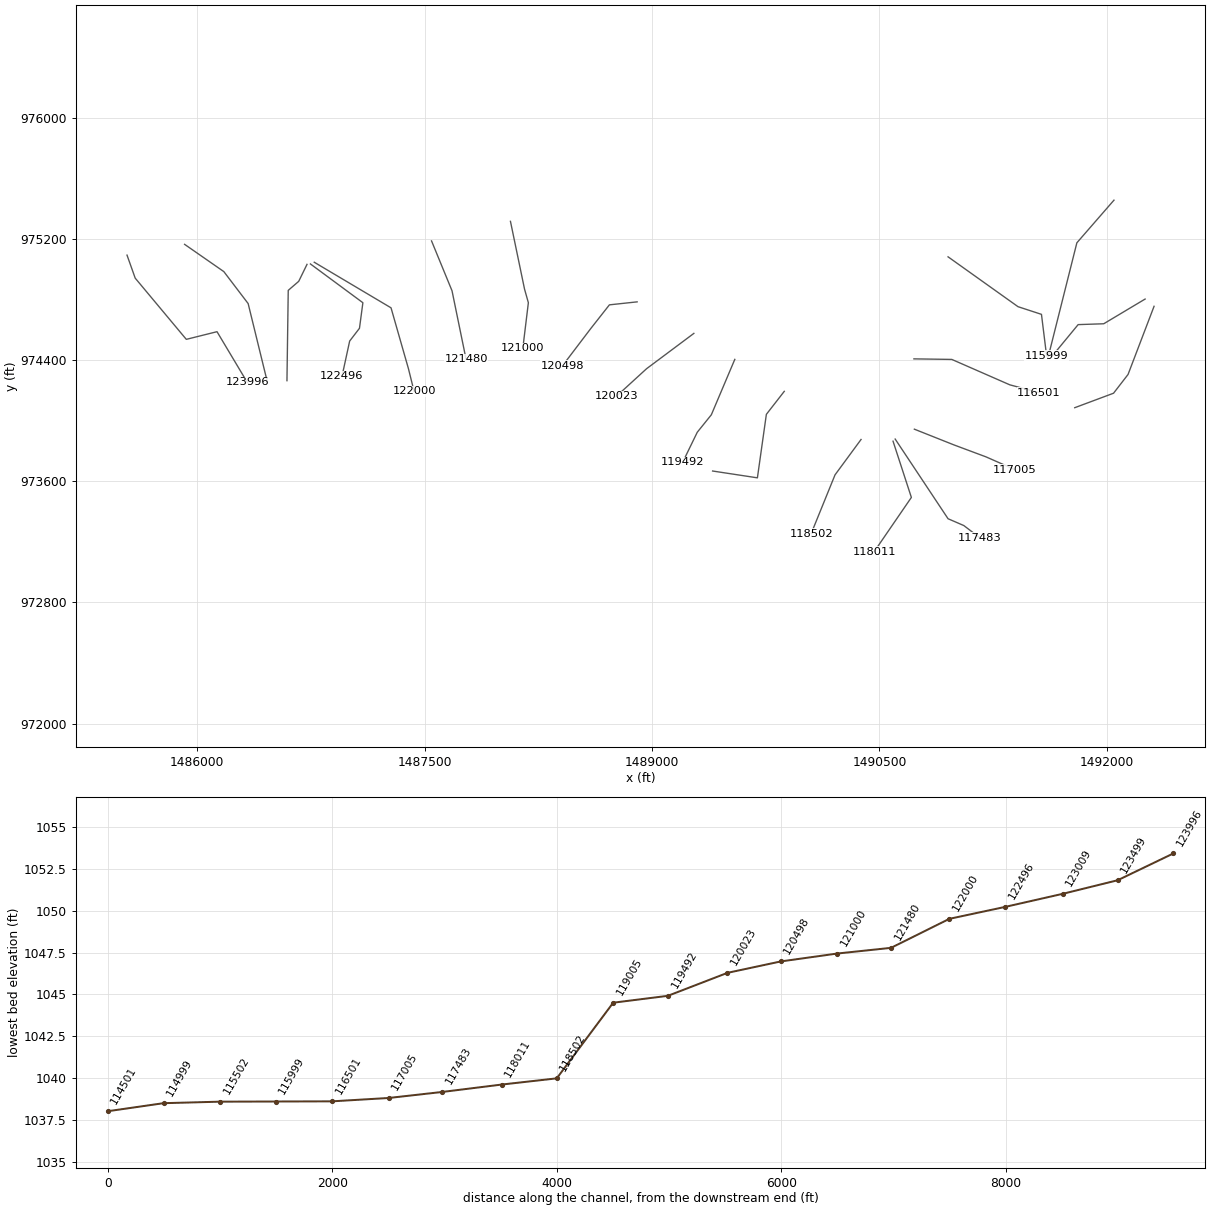
HEC-RAS study Fisher River.prj: Fisher River Limited Detail Study

--- Fisher River.g01 (geometry) --- (continued)

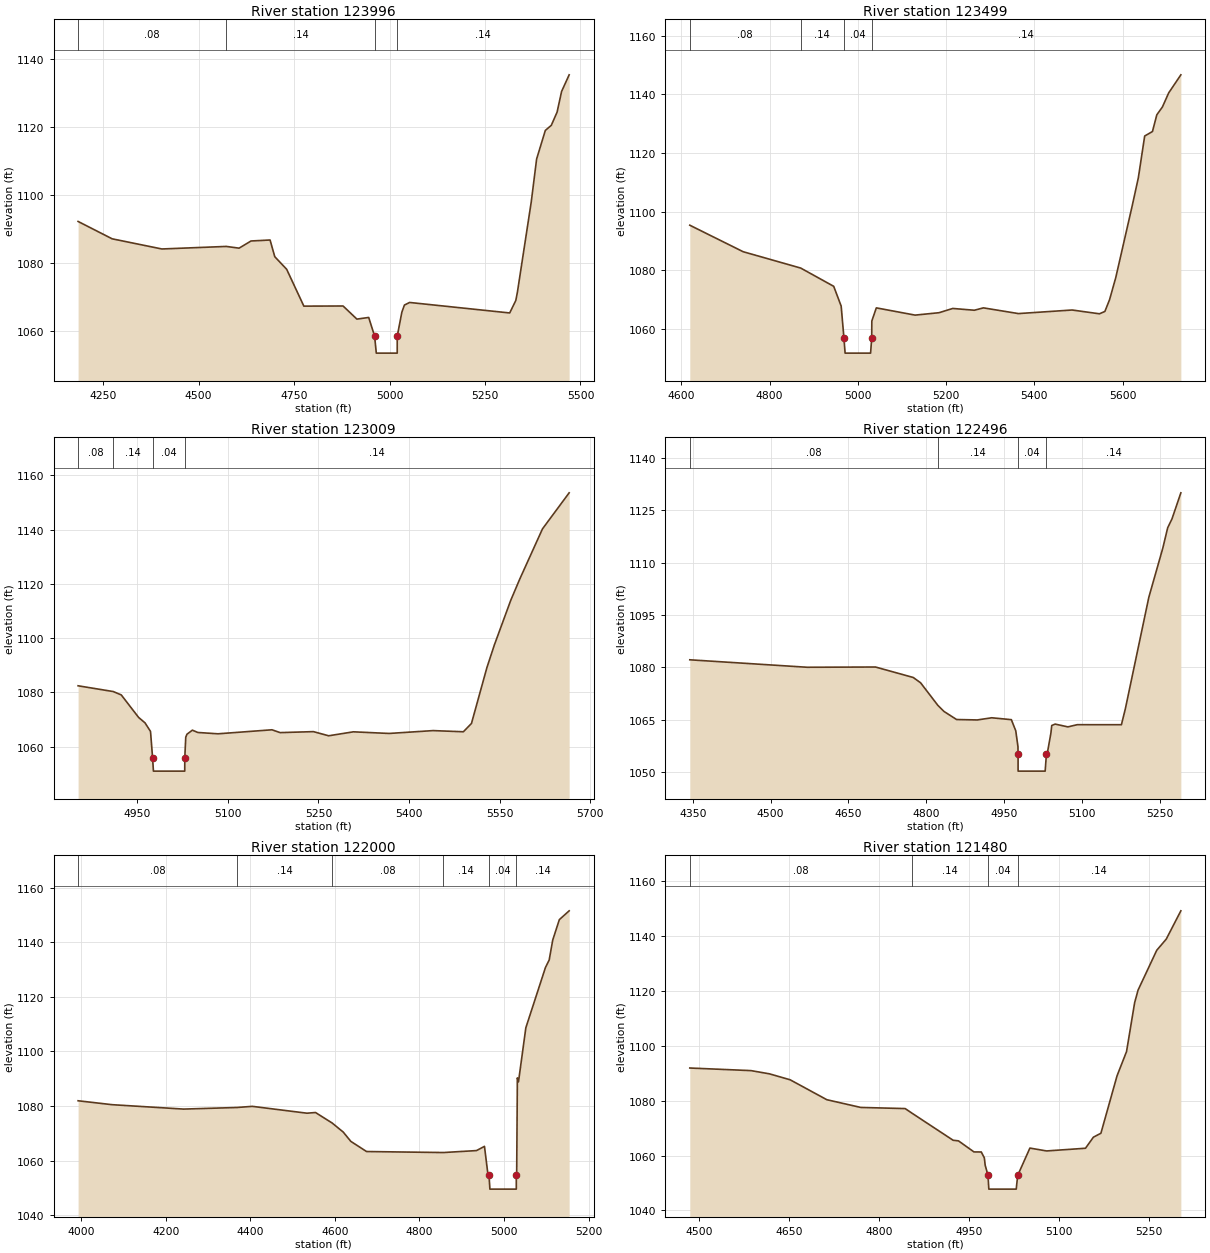
Type RM Length L Ch R = 1,123996,497,497,497
BEGIN DESCRIPTION:
Fisher River 248.0
END DESCRIPTION:
XS GIS Cut Line= 5
      1485537.46       975092.83      1485591.41       974940.90
      1485928.46       974536.71      1486131.00       974587.35
      1486330.73       974252.58
#Sta/Elev= 30
  4184.2 1092.16  4273.4 1087.05  4403.6 1084.06  4572.5 1084.81  4605.8 1084.30
  4637.1 1086.41  4687.0 1086.70  4699.3 1081.79  4730.5 1078.08  4775.5 1067.24
  4878.2 1067.28  4914.4 1063.42  4945.3 1063.91  4960.8 1058.41  4965.2 1053.41
  5020.0 1053.41  5020.1 1058.41  5032.1 1065.44  5038.8 1067.55  5052.4 1068.32
  5314.6 1065.23  5330.6 1068.91  5334.8 1071.37  5371.0 1097.89  5385.1 1110.54
  5407.9 1118.95  5423.5 1120.44  5438.7 1124.33  5450.5 1130.42  5470.3 1135.31
#Mann=4,-1,0
  4184.2    0.08       0  4572.5    0.14       0  4960.8    0.04       0
  5020.1    0.14       0
Bank Sta=4960.8,5020.1
XS Rating Curve= 0
Exp/Cntr=0.3,0.1

Type RM Length L Ch R = 1,123499,490,490,490
BEGIN DESCRIPTION:
Fisher River 247.0
END DESCRIPTION:
XS GIS Cut Line= 4
      1485917.19       975164.03      1486176.01       974983.98
      1486336.35       974773.01      1486462.93       974255.43
#Sta/Elev= 30
  4619.1 1095.42  4740.1 1086.38  4870.5 1080.81  4945.3 1074.59  4962.2 1067.86
  4968.6 1056.81  4971.1 1051.81  5028.9 1051.81  5031.4 1056.81  5031.7 1062.76
  5041.9 1067.24  5129.8 1064.77  5184.0 1065.59  5215.2 1067.04  5264.1 1066.43
  5284.7 1067.24  5364.0 1065.29  5485.8 1066.51  5547.6 1065.22  5560.0 1066.02
  5570.6 1070.04  5584.6 1077.54  5621.8 1101.96  5635.8 1111.57  5650.2 1125.83
  5667.8 1127.36  5677.7 1133.06  5690.4 1135.73  5704.6 1140.52  5732.2 1146.69
#Mann=4,-1,0
  4619.1    0.08       0  4870.5    0.14       0  4968.6    0.04       0
  5031.4    0.14       0
Bank Sta=4968.6,5031.4
XS Rating Curve= 0
Exp/Cntr=0.3,0.1

Type RM Length L Ch R = 1,123009,513,513,513
BEGIN DESCRIPTION:
Fisher River 246.0
END DESCRIPTION:
XS GIS Cut Line= 4
      1486724.55       975031.81      1486669.94       974919.85
      1486600.77       974860.21      1486592.33       974263.87
#Sta/Elev= 30
  4852.5 1082.44  4910.6 1080.32  4923.9 1079.08  4952.6 1070.79  4963.2 1068.78
  4972.3 1065.63  4975.7 1056.00  4977.1 1051.00  5028.9 1051.00  5029.0 1056.00
  5030.6 1063.51  5032.6 1064.61  5041.6 1066.09  5050.5 1065.24  5083.9 1064.75
  5173.2 1066.23  5186.7 1065.19  5241.8 1065.55  5267.0 1064.02  5307.8 1065.48
  5367.0 1064.88  5439.7 1065.93  5489.8 1065.50  5503.2 1068.56  5528.7 1089.10
  5541.0 1097.44  5568.1 1113.88  5583.0 1121.71  5620.7 1140.26  5664.8 1153.53
#Mann=4,-1,0
  4852.5    0.08       0  4910.6    0.14       0  4975.7    0.04       0
  5029.0    0.14       0
Bank Sta=4975.7,5029
XS Rating Curve= 0
Exp/Cntr=0.3,0.1

Type RM Length L Ch R = 1,122496,496,496,496
BEGIN DESCRIPTION:
Fisher River 245.0
END DESCRIPTION:
XS GIS Cut Line= 5
      1486747.05       975034.61      1487093.05       974778.63
      1487070.55       974609.85      1487005.85       974525.46
      1486955.22       974292.00
#Sta/Elev= 30
  4344.4 1082.15  4570.5 1080.01  4702.1 1080.08  4774.8 1077.08  4789.0 1075.55
  4822.2 1069.09  4834.1 1067.33  4858.3 1065.02  4898.2 1064.90  4925.9 1065.52
  4963.8 1064.98  4972.3 1061.78  4976.5 1057.26  4976.7 1055.22  4976.8 1050.22
  5028.9 1050.22  5031.4 1055.22  5032.9 1055.22  5039.9 1061.05  5041.6 1063.31
  5048.2 1063.71  5072.7 1062.91  5090.7 1063.54  5175.8 1063.53  5183.5 1068.18
  5228.6 1100.08  5255.6 1114.22  5264.9 1120.01  5273.2 1122.56  5290.3 1130.04
#Mann=4,-1,0
  4344.4    0.08       0  4822.2    0.14       0  4976.7    0.04       0
  5031.4    0.14       0
Bank Sta=4976.7,5031.4
XS Rating Curve= 0
Exp/Cntr=0.3,0.1

Type RM Length L Ch R = 1,122000,520,520,520
BEGIN DESCRIPTION:
Fisher River 244.0
END DESCRIPTION:
XS GIS Cut Line= 4
      1486772.36       975045.87      1487278.71       974744.88
      1487393.61       974342.93      1487430.61       974193.54
#Sta/Elev= 30
  3992.9 1081.92  4073.5 1080.48  4242.2 1078.87  4367.9 1079.45  4404.9 1079.87
  4534.0 1077.36  4554.2 1077.61  4593.4 1073.78  4619.8 1070.43  4637.7 1067.03
  4674.9 1063.30  4856.8 1062.93  4934.9 1063.65  4953.7 1065.20  4961.6 1055.27
  4962.7 1054.52  4964.5 1054.51  4966.5 1049.51  5028.9 1049.51  5029.0 1054.51
  5029.8 1054.51  5031.2 1084.09  5031.4 1090.32  5034.1 1088.87  5051.5 1108.70
  5097.9 1130.81  5106.7 1133.56  5115.1 1140.89  5130.7 1148.36  5153.9 1151.59
#Mann=6,-1,0
  3992.9    0.08       0  4367.9    0.14       0  4593.4    0.08       0
  4856.8    0.14       0  4964.5    0.04       0  5029.0    0.14       0
Bank Sta=4964.5,5029
XS Rating Curve= 0
Exp/Cntr=0.3,0.1

Type RM Length L Ch R = 1,121480,480,480,480
BEGIN DESCRIPTION:
Fisher River 243.0
END DESCRIPTION:
XS GIS Cut Line= 3
      1487545.93       975186.55      1487680.97       974857.40
      1487773.80       974404.49
#Sta/Elev= 30
  4485.1 1091.87  4587.1 1090.92  4617.8 1089.75  4652.3 1087.58  4713.4 1080.33
  4769.8 1077.52  4843.9 1077.10  4855.1 1075.45  4923.8 1065.57  4932.7 1065.35
  4958.5 1061.33  4970.7 1061.30  4975.8 1059.17  4977.2 1056.48  4981.9 1052.78
  4983.3 1047.78  5028.9 1047.78  5031.4 1052.78  5051.7 1062.72  5079.5 1061.68
  5144.3 1062.66  5157.5 1066.69  5170.0 1068.12  5196.9 1089.04  5212.7 1097.85
  5226.2 1115.66  5231.9 1120.23  5263.0 1134.72  5278.9 1138.81  5303.2 1149.09
#Mann=4,-1,0
  4485.1    0.08       0  4855.1    0.14       0  4981.9    0.04       0
  5031.4    0.14       0
Bank Sta=4981.9,5031.4
XS Rating Curve= 0
Exp/Cntr=0.3,0.1

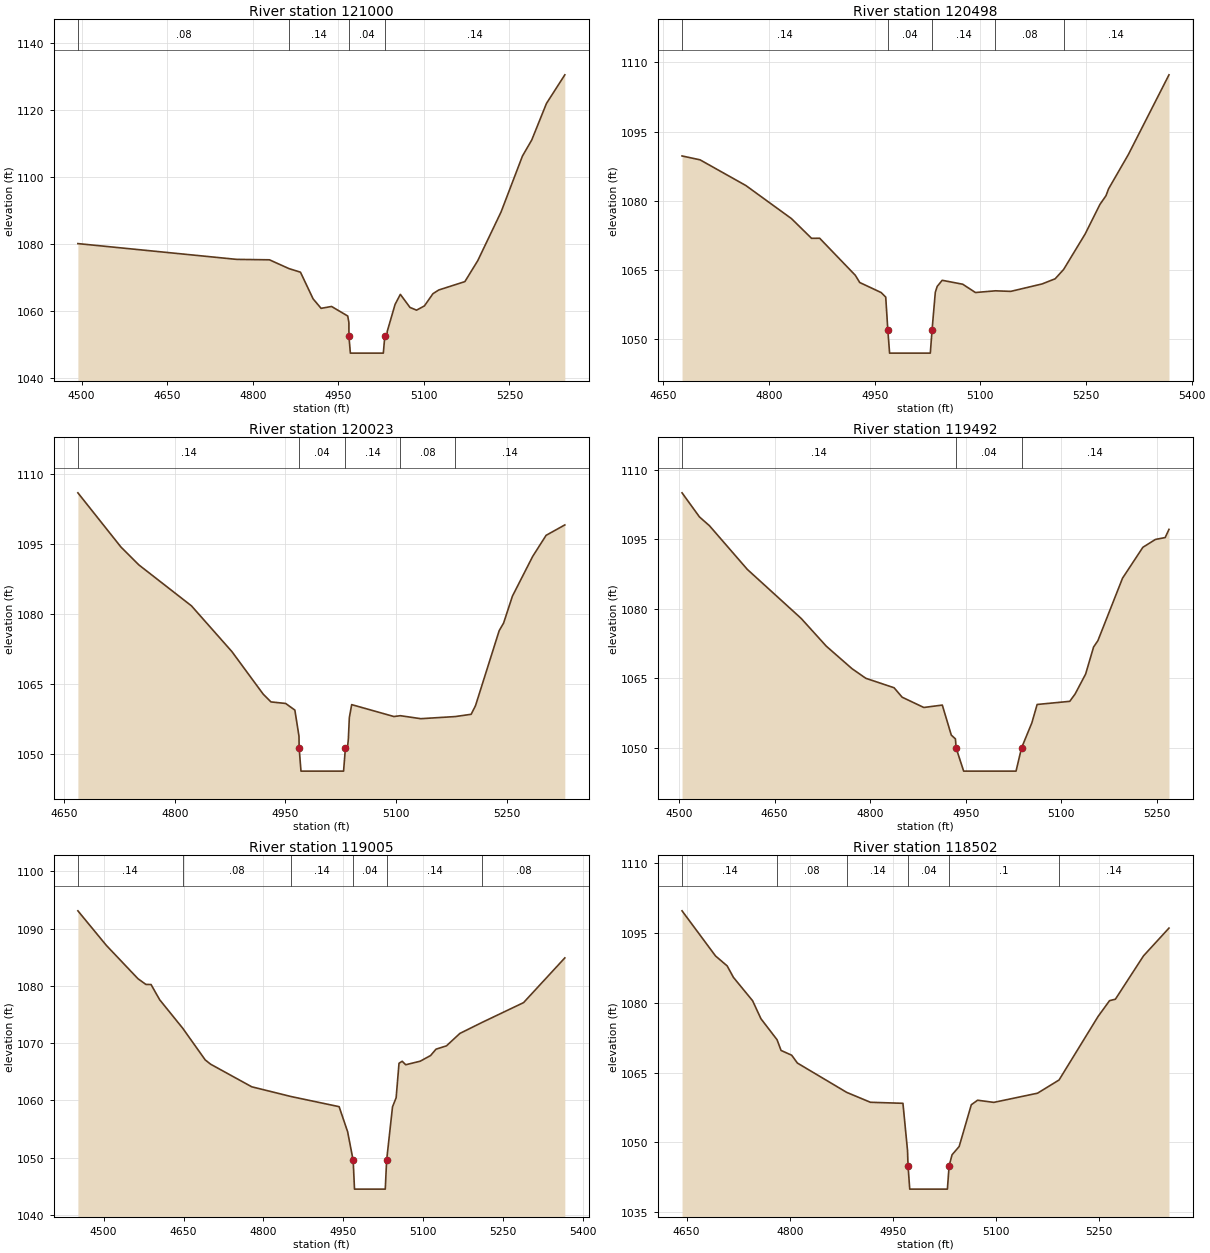
Type RM Length L Ch R = 1,121000,502,502,502
BEGIN DESCRIPTION:
Fisher River 242.0
END DESCRIPTION:
XS GIS Cut Line= 4
      1488066.36       975315.89      1488159.18       974868.65
      1488184.50       974778.63      1488147.93       974477.62
#Sta/Elev= 30
  4493.5 1080.14  4771.8 1075.43  4829.3 1075.30  4863.6 1072.67  4883.6 1071.61
  4905.8 1063.64  4919.8 1060.81  4938.1 1061.37  4966.5 1058.52  4968.5 1056.59
  4968.6 1052.44  4971.1 1047.44  5028.9 1047.44  5031.4 1052.44  5035.5 1052.44
  5035.7 1053.92  5049.5 1062.00  5058.7 1064.99  5075.6 1061.08  5087.1 1060.27
  5100.9 1061.54  5115.8 1065.18  5126.0 1066.29  5171.8 1068.79  5194.4 1075.05
  5235.3 1089.61  5272.8 1106.31  5289.0 1111.07  5314.8 1121.98  5347.0 1130.53
#Mann=4,-1,0
  4493.5    0.08       0  4863.6    0.14       0  4968.6    0.04       0
  5031.4    0.14       0
Bank Sta=4968.6,5031.4
XS Rating Curve= 0
Exp/Cntr=0.3,0.1

Type RM Length L Ch R = 1,120498,475,475,475
BEGIN DESCRIPTION:
Fisher River 241.0
END DESCRIPTION:
XS GIS Cut Line= 4
      1488901.82       974784.26      1488718.98       974764.57
      1488595.20       974607.04      1488409.56       974362.33
#Sta/Elev= 30
  4676.4 1089.72  4702.0 1088.88  4767.1 1083.30  4831.8 1076.13  4860.3 1071.86
  4871.8 1071.88  4922.4 1063.85  4928.7 1062.28  4959.2 1060.10  4965.6 1059.12
  4968.6 1051.97  4971.1 1046.97  5028.9 1046.97  5031.4 1051.97  5036.0 1060.16
  5038.7 1061.44  5045.8 1062.76  5074.9 1061.91  5093.0 1060.11  5121.4 1060.48
  5143.2 1060.36  5187.6 1061.97  5206.2 1063.09  5218.2 1065.11  5248.8 1072.81
  5269.7 1079.20  5278.4 1081.11  5282.0 1082.59  5310.2 1090.05  5367.8 1107.31
#Mann=5,-1,0
  4676.4    0.14       0  4968.6    0.04       0  5031.4    0.14       0
  5121.4    0.08       0  5218.2    0.14       0
Bank Sta=4968.6,5031.4
XS Rating Curve= 0
Exp/Cntr=0.3,0.1

Type RM Length L Ch R = 1,120023,531,531,531
BEGIN DESCRIPTION:
Fisher River 240.0
END DESCRIPTION:
XS GIS Cut Line= 3
      1489275.99       974576.12      1488963.71       974342.61
      1488763.99       974159.77
#Sta/Elev= 30
  4668.4 1105.88  4726.9 1094.26  4751.2 1090.44  4822.5 1081.68  4877.4 1071.88
  4919.9 1062.76  4930.4 1061.11  4950.3 1060.78  4962.8 1059.36  4968.4 1053.77
  4968.6 1051.29  4971.1 1046.29  5028.9 1046.29  5031.4 1051.29  5034.2 1051.29
  5035.4 1053.19  5036.7 1057.73  5039.9 1060.53  5097.2 1057.98  5105.9 1058.16
  5133.6 1057.52  5180.3 1057.97  5202.0 1058.46  5207.9 1060.30  5240.0 1076.35
  5246.0 1077.99  5258.0 1083.76  5285.5 1092.27  5303.7 1096.78  5329.1 1099.01
#Mann=5,-1,0
  4668.4    0.14       0  4968.6    0.04       0  5031.4    0.14       0
  5105.9    0.08       0  5180.3    0.14       0
Bank Sta=4968.6,5031.4
XS Rating Curve= 0
Exp/Cntr=0.3,0.1

Type RM Length L Ch R = 1,119492,487,487,487
BEGIN DESCRIPTION:
Fisher River 239.0
END DESCRIPTION:
XS GIS Cut Line= 4
      1489546.01       974404.53      1489391.29       974038.81
      1489298.46       973923.47      1489202.80       973726.53
#Sta/Elev= 30
  4504.8 1105.09  4532.2 1099.87  4547.8 1097.98  4607.2 1088.54  4691.7 1077.94
  4731.2 1071.93  4771.6 1067.06  4793.2 1064.99  4837.5 1062.95  4850.2 1060.90
  4884.2 1058.68  4913.2 1059.20  4927.3 1052.71  4933.8 1051.89  4934.9 1049.92
  4946.7 1044.92  5028.9 1044.92  5037.5 1049.92  5053.7 1055.35  5062.0 1059.33
  5113.2 1060.01  5121.6 1061.60  5138.1 1065.91  5150.6 1071.76  5157.3 1073.11
  5196.0 1086.63  5227.9 1093.31  5247.6 1095.01  5262.9 1095.42  5268.9 1097.19
#Mann=3,-1,0
  4504.8    0.14       0  4934.9    0.04       0  5037.5    0.14       0
Bank Sta=4934.9,5037.5
XS Rating Curve= 0
Exp/Cntr=0.3,0.1

Type RM Length L Ch R = 1,119005,503,503,503
BEGIN DESCRIPTION:
Fisher River 238.0
END DESCRIPTION:
XS GIS Cut Line= 4
      1489872.29       974193.49      1489754.17       974041.62
      1489695.09       973622.48      1489399.68       973667.50
#Sta/Elev= 30
  4451.6 1093.11  4505.0 1087.08  4564.5 1081.25  4579.3 1080.26  4589.0 1080.24
  4605.2 1077.58  4648.7 1072.58  4690.7 1067.08  4700.8 1066.33  4778.1 1062.38
  4852.4 1060.67  4942.2 1058.91  4958.2 1054.53  4968.6 1049.51  4971.1 1044.51
  5028.9 1044.51  5031.4 1049.51  5042.5 1058.88  5049.3 1060.47  5054.7 1066.49
  5060.7 1066.84  5067.3 1066.23  5094.5 1066.85  5114.0 1067.84  5124.2 1068.95
  5143.8 1069.53  5169.0 1071.70  5211.3 1073.65  5288.6 1077.08  5366.1 1084.89
#Mann=6,-1,0
  4451.6    0.14       0  4648.7    0.08       0  4852.4    0.14       0
  4968.6    0.04       0  5031.4    0.14       0  5211.3    0.08       0
Bank Sta=4968.6,5031.4
XS Rating Curve= 0
Exp/Cntr=0.3,0.1

Type RM Length L Ch R = 1,118502,491,491,491
BEGIN DESCRIPTION:
Fisher River 237.0
END DESCRIPTION:
XS GIS Cut Line= 3
      1490378.68       973875.69      1490207.06       973642.17
      1490049.55       973254.01
#Sta/Elev= 30
  4643.3 1099.67  4692.0 1090.00  4709.0 1087.86  4718.1 1085.40  4746.0 1080.39
  4758.1 1076.54  4781.6 1072.03  4787.4 1069.74  4802.9 1068.71  4811.2 1067.03
  4883.0 1060.74  4917.5 1058.62  4964.8 1058.40  4971.5 1048.22  4972.2 1045.00
  4974.7 1040.00  5029.5 1040.00  5032.0 1045.00  5036.3 1047.37  5046.6 1049.13
  5064.3 1058.09  5073.4 1059.06  5097.1 1058.60  5160.7 1060.57  5192.0 1063.40
  5248.8 1077.02  5265.5 1080.41  5274.0 1080.72  5314.9 1090.01  5352.0 1095.97
#Mann=6,-1,0
  4643.3    0.14       0  4781.6    0.08       0  4883.0    0.14       0
  4972.2    0.04       0  5032.0     0.1       0  5192.0    0.14       0
Bank Sta=4972.2,5032
XS Rating Curve= 0
Exp/Cntr=0.3,0.1

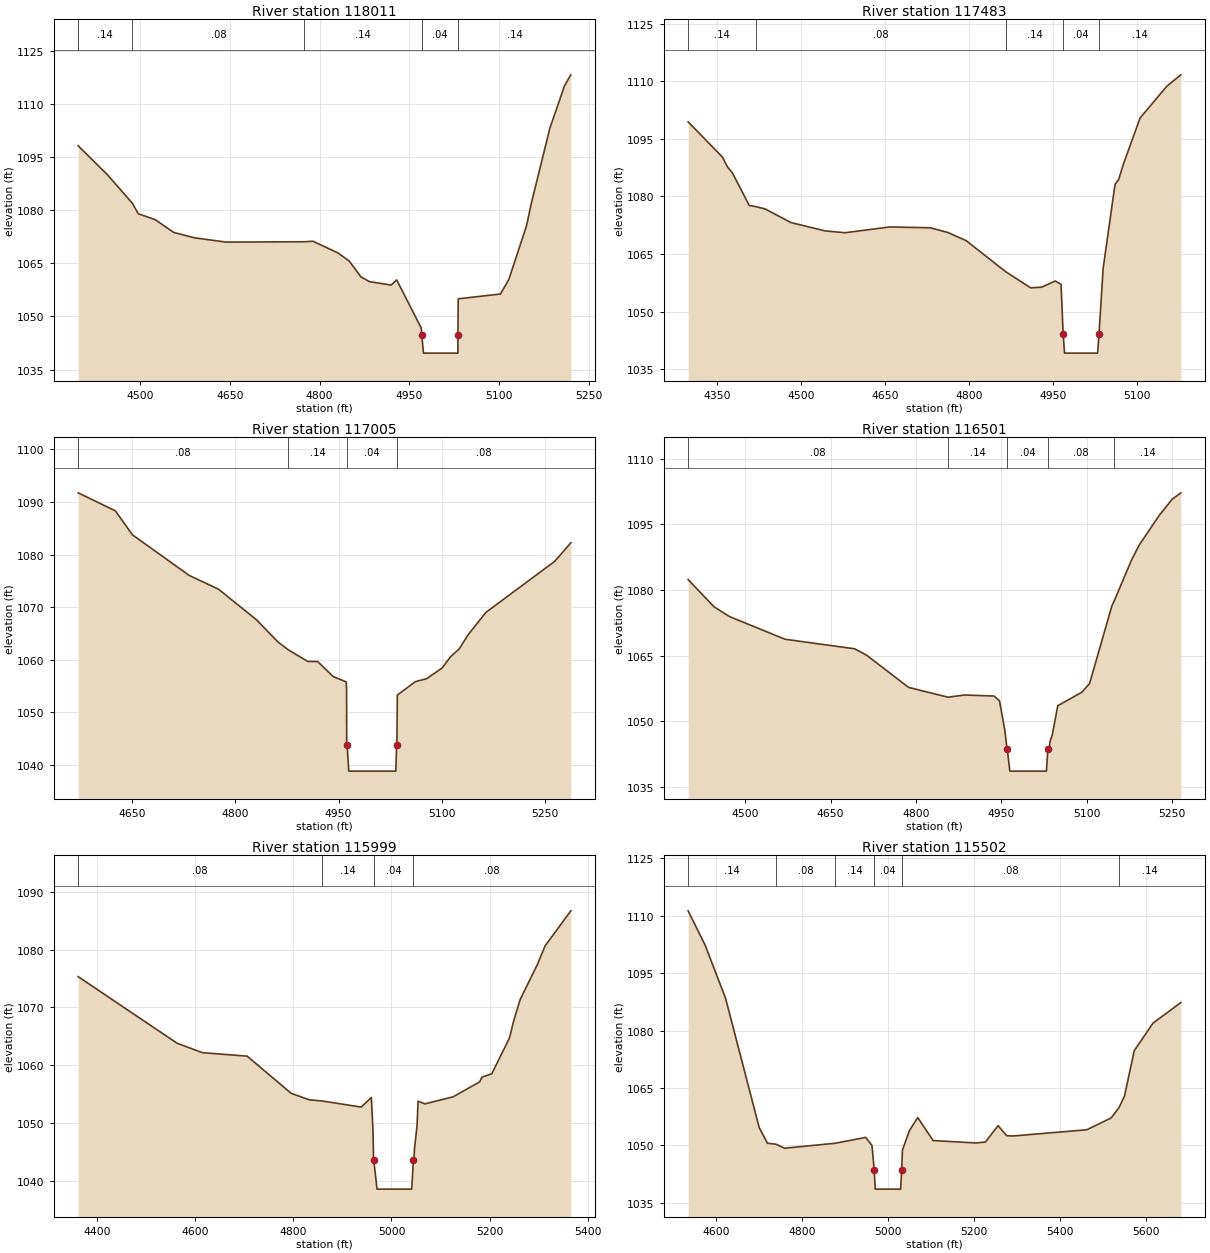
Type RM Length L Ch R = 1,118011,528,528,528
BEGIN DESCRIPTION:
Fisher River 236.0
END DESCRIPTION:
XS GIS Cut Line= 3
      1490589.64       973864.39      1490710.59       973493.08
      1490465.83       973135.79
#Sta/Elev= 30
  4396.4 1098.14  4445.2 1089.99  4487.0 1081.93  4496.9 1078.96  4525.1 1077.30
  4556.0 1073.70  4590.8 1072.17  4643.9 1070.96  4774.5 1071.06  4789.2 1071.20
  4831.5 1067.83  4849.7 1065.60  4869.2 1061.14  4883.2 1059.80  4919.7 1058.85
  4928.9 1060.29  4969.9 1046.73  4970.9 1044.63  4973.7 1039.63  5031.2 1039.63
  5031.3 1044.63  5031.7 1054.26  5032.1 1054.96  5102.3 1056.31  5116.3 1060.37
  5146.0 1075.59  5154.1 1082.00  5184.9 1103.04  5209.5 1115.07  5220.0 1118.16
#Mann=5,-1,0
  4396.4    0.14       0  4487.0    0.08       0  4774.5    0.14       0
  4970.9    0.04       0  5031.3    0.14       0
Bank Sta=4970.9,5031.3
XS Rating Curve= 0
Exp/Cntr=0.3,0.1

Type RM Length L Ch R = 1,117483,478,478,478
BEGIN DESCRIPTION:
Fisher River 235.0
END DESCRIPTION:
XS GIS Cut Line= 4
      1490603.71       973878.44      1490952.51       973352.43
      1491056.59       973307.42      1491163.48       973225.85
#Sta/Elev= 30
  4298.9 1099.45  4360.1 1090.27  4369.0 1087.72  4377.8 1086.18  4407.9 1077.67
  4419.6 1077.37  4436.4 1076.75  4482.4 1073.20  4543.6 1071.03  4578.9 1070.56
  4658.9 1072.07  4731.0 1071.85  4762.6 1070.61  4795.1 1068.49  4865.6 1060.39
  4910.0 1056.21  4929.5 1056.37  4953.9 1057.98  4964.3 1057.12  4968.0 1044.19
  4970.5 1039.19  5029.5 1039.19  5032.0 1044.19  5039.4 1061.29  5060.6 1083.19
  5067.1 1084.43  5075.8 1088.55  5105.2 1100.43  5152.9 1108.71  5177.9 1111.70
#Mann=5,-1,0
  4298.9    0.14       0  4419.6    0.08       0  4865.6    0.14       0
  4968.0    0.04       0  5032.0    0.14       0
Bank Sta=4968,5032
XS Rating Curve= 0
Exp/Cntr=0.3,0.1

Type RM Length L Ch R = 1,117005,504,504,504
BEGIN DESCRIPTION:
Fisher River 234.0
END DESCRIPTION:
XS GIS Cut Line= 4
      1490730.28       973943.73      1490991.90       973839.65
      1491202.87       973760.88      1491394.13       973676.50
#Sta/Elev= 30
  4571.7 1091.75  4625.7 1088.33  4650.7 1083.75  4733.1 1076.04  4775.7 1073.42
  4830.7 1067.63  4861.6 1063.43  4877.2 1061.88  4905.4 1059.68  4919.6 1059.68
  4942.3 1056.81  4961.1 1055.80  4961.7 1054.57  4961.9 1043.84  4962.5 1043.83
  4964.9 1038.83  5033.2 1038.83  5034.4 1043.83  5034.8 1043.84  5035.4 1053.22
  5035.7 1053.32  5061.7 1055.85  5078.0 1056.41  5100.4 1058.43  5112.8 1060.59
  5125.4 1062.07  5137.8 1064.68  5164.1 1069.01  5264.2 1078.73  5287.5 1082.24
#Mann=4,-1,0
  4571.7    0.08       0  4877.2    0.14       0  4962.5    0.04       0
  5034.4    0.08       0
Bank Sta=4962.5,5034.4
XS Rating Curve= 0
Exp/Cntr=0.3,0.1

Type RM Length L Ch R = 1,116501,502,502,502
BEGIN DESCRIPTION:
Fisher River 233.0
END DESCRIPTION:
XS GIS Cut Line= 4
      1490727.44       974407.88      1490977.14       974404.29
      1491360.40       974236.28      1491551.72       974185.64
#Sta/Elev= 30
  4399.6 1082.36  4444.9 1076.18  4472.3 1073.92  4570.0 1068.74  4692.4 1066.56
  4713.6 1065.08  4787.1 1057.75  4856.5 1055.51  4885.3 1056.01  4937.3 1055.78
  4947.0 1054.67  4956.3 1048.03  4960.3 1043.63  4960.7 1043.63  4965.1 1038.63
  5029.5 1038.63  5032.0 1043.63  5034.5 1043.63  5035.6 1045.29  5039.9 1046.96
  5049.4 1053.56  5091.8 1056.65  5105.4 1058.64  5144.6 1076.38  5148.9 1077.56
  5179.0 1086.80  5192.6 1090.24  5227.5 1096.97  5250.5 1100.69  5265.7 1102.17
#Mann=5,-1,0
  4399.6    0.08       0  4856.5    0.14       0  4960.7    0.04       0
  5032.0    0.08       0  5148.9    0.14       0
Bank Sta=4960.7,5032
XS Rating Curve= 0
Exp/Cntr=0.3,0.1

Type RM Length L Ch R = 1,115999,497,497,497
BEGIN DESCRIPTION:
Fisher River 232.0
END DESCRIPTION:
XS GIS Cut Line= 4
      1490952.54       975081.57      1491413.85       974752.47
      1491568.56       974701.84      1491602.32       974428.97
#Sta/Elev= 30
  4361.2 1075.32  4563.3 1063.80  4614.7 1062.19  4705.8 1061.59  4795.4 1055.17
  4832.3 1054.05  4859.1 1053.84  4938.3 1052.79  4958.9 1054.45  4962.2 1048.91
  4963.5 1043.62  4963.9 1043.62  4970.5 1038.62  5041.2 1038.62  5044.7 1043.62
  5045.7 1043.62  5046.8 1045.50  5052.1 1049.60  5054.2 1053.80  5068.3 1053.35
  5125.8 1054.57  5179.8 1057.15  5184.2 1057.94  5204.5 1058.55  5240.5 1064.72
  5249.3 1067.74  5262.2 1071.34  5297.7 1077.47  5313.3 1080.65  5365.6 1086.69
#Mann=4,-1,0
  4361.2    0.08       0  4859.1    0.14       0  4963.9    0.04       0
  5044.7    0.08       0
Bank Sta=4963.9,5044.7
XS Rating Curve= 0
Exp/Cntr=0.3,0.1

Type RM Length L Ch R = 1,115502,503,503,503
BEGIN DESCRIPTION:
Fisher River 231.0
END DESCRIPTION:
XS GIS Cut Line= 3
      1492046.79       975455.74      1491802.05       975174.14
      1491613.56       974423.03
#Sta/Elev= 30
  4534.6 1111.25  4574.2 1102.30  4621.9 1088.38  4700.2 1054.63  4719.5 1050.58
  4739.1 1050.34  4759.1 1049.29  4877.8 1050.59  4948.2 1052.12  4962.9 1049.98
  4968.0 1043.61  4970.5 1038.61  5029.5 1038.61  5032.0 1043.61  5033.7 1048.77
  5050.1 1053.91  5069.4 1057.30  5105.2 1051.29  5204.7 1050.66  5227.0 1050.89
  5256.4 1055.18  5276.6 1052.56  5291.2 1052.48  5463.3 1054.11  5520.0 1057.20
  5538.2 1059.88  5551.1 1062.94  5573.6 1074.73  5617.3 1081.93  5682.1 1087.30
#Mann=6,-1,0
  4534.6    0.14       0  4739.1    0.08       0  4877.8    0.14       0
  4968.0    0.04       0  5032.0    0.08       0  5538.2    0.14       0
Bank Sta=4968,5032
XS Rating Curve= 0
Exp/Cntr=0.3,0.1

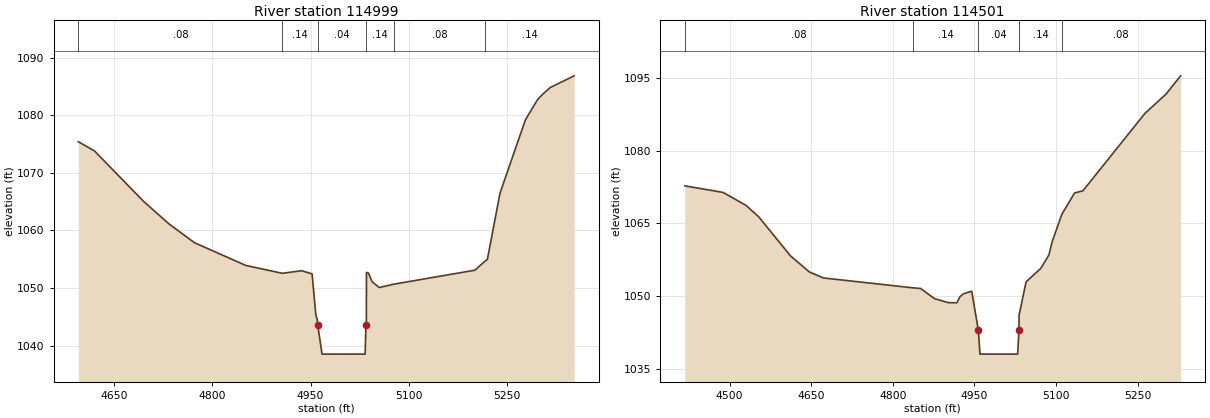
Type RM Length L Ch R = 1,114999,498,498,498
BEGIN DESCRIPTION:
Fisher River 230.0
END DESCRIPTION:
XS GIS Cut Line= 4
      1492252.14       974802.83      1491979.27       974639.67
      1491810.48       974634.04      1491638.88       974425.87
#Sta/Elev= 30
  4595.7 1075.42  4620.3 1073.82  4695.3 1065.05  4733.7 1061.17  4773.0 1057.87
  4851.1 1053.93  4907.0 1052.56  4936.7 1053.01  4952.4 1052.45  4958.2 1045.25
  4960.1 1044.64  4961.1 1043.52  4967.6 1038.52  5033.3 1038.52  5034.6 1043.52
  5035.2 1043.54  5035.4 1052.71  5038.4 1052.61  5043.9 1051.10  5054.8 1050.09
  5077.1 1050.67  5200.9 1053.10  5216.2 1054.66  5219.9 1054.99  5239.2 1066.49
  5277.9 1079.22  5296.7 1082.77  5303.6 1083.58  5315.8 1084.83  5352.3 1086.86
#Mann=6,-1,0
  4595.7    0.08       0  4907.0    0.14       0  4961.1    0.04       0
  5034.6    0.14       0  5077.1    0.08       0  5216.2    0.14       0
Bank Sta=4961.1,5034.6
XS Rating Curve= 0
Exp/Cntr=0.3,0.1

Type RM Length L Ch R = 1,114501,488,488,488
BEGIN DESCRIPTION:
Fisher River 229.0
END DESCRIPTION:
XS GIS Cut Line= 4
      1492311.20       974755.01      1492139.61       974304.92
      1492043.96       974181.15      1491787.96       974085.50
#Sta/Elev= 30
  4417.7 1072.74  4488.1 1071.38  4530.3 1068.70  4553.6 1066.35  4611.9 1058.31
  4646.9 1054.96  4672.9 1053.74  4837.7 1051.70  4851.0 1051.58  4876.7 1049.49
  4902.1 1048.65  4917.9 1048.63  4923.4 1049.87  4929.7 1050.47  4945.0 1051.02
  4957.2 1043.04  4960.3 1038.04  5029.5 1038.04  5032.0 1043.04  5032.1 1046.04
  5045.0 1052.93  5072.3 1055.75  5087.0 1058.49  5092.8 1061.17  5110.8 1066.87
  5134.2 1071.27  5149.5 1071.71  5263.5 1087.67  5302.2 1091.65  5329.1 1095.42
#Mann=5,-1,0
  4417.7    0.08       0  4837.7    0.14       0  4957.2    0.04       0
  5032.0    0.14       0  5110.8    0.08       0
Bank Sta=4957.2,5032
XS Rating Curve= 0
Exp/Cntr=0.3,0.1