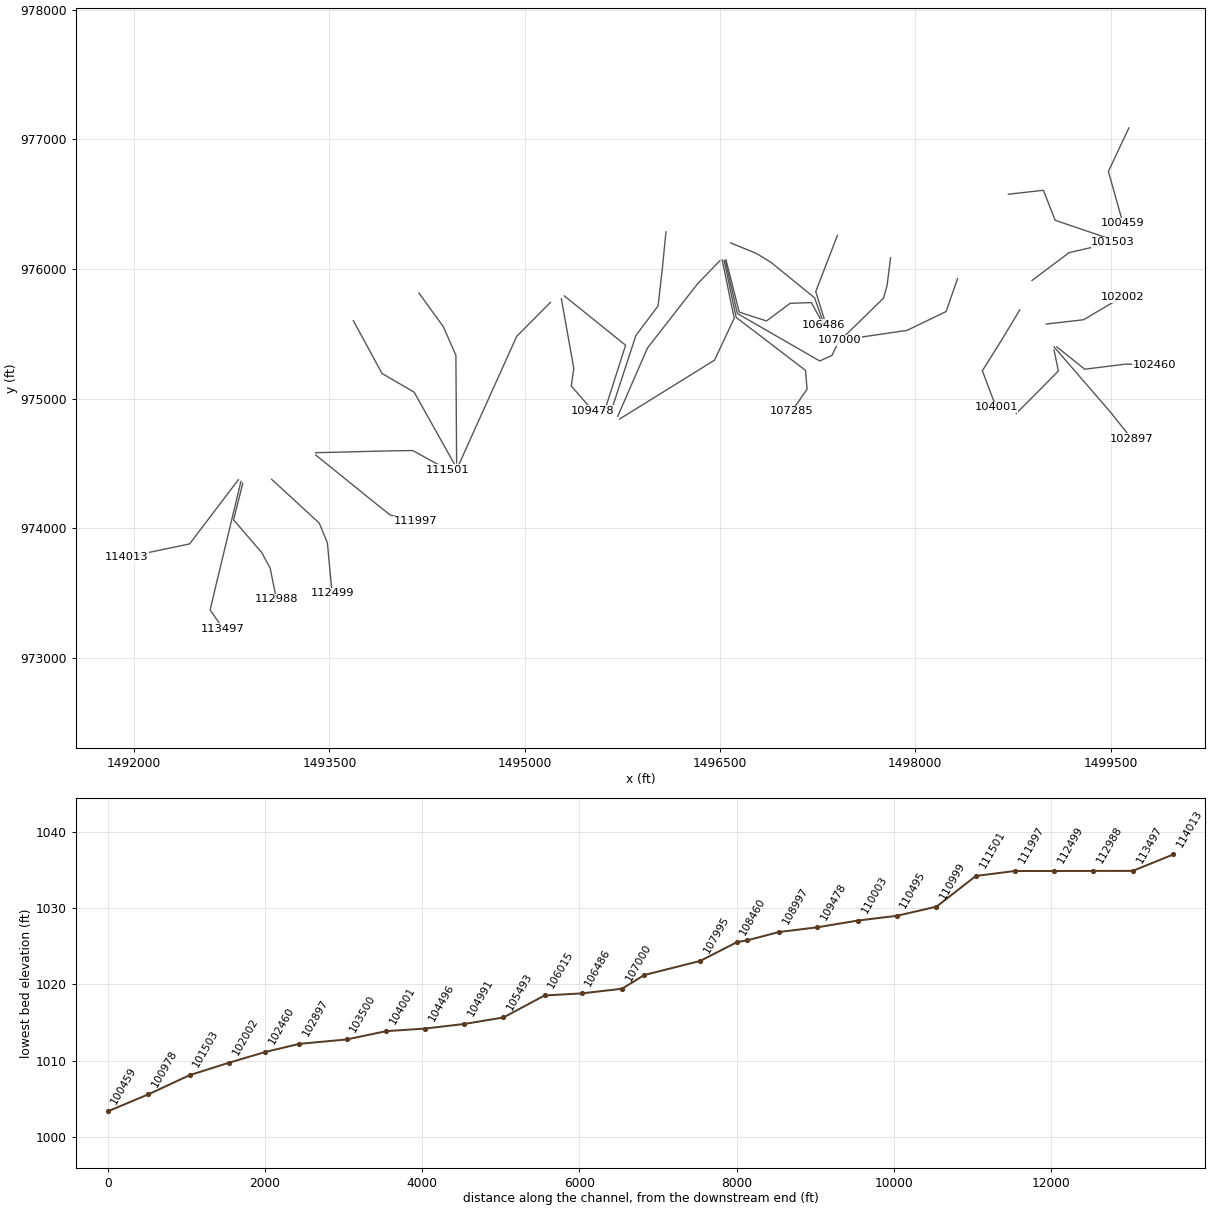
HEC-RAS study Fisher River.prj: Fisher River Limited Detail Study

--- Fisher River.g01 (geometry) --- (continued)

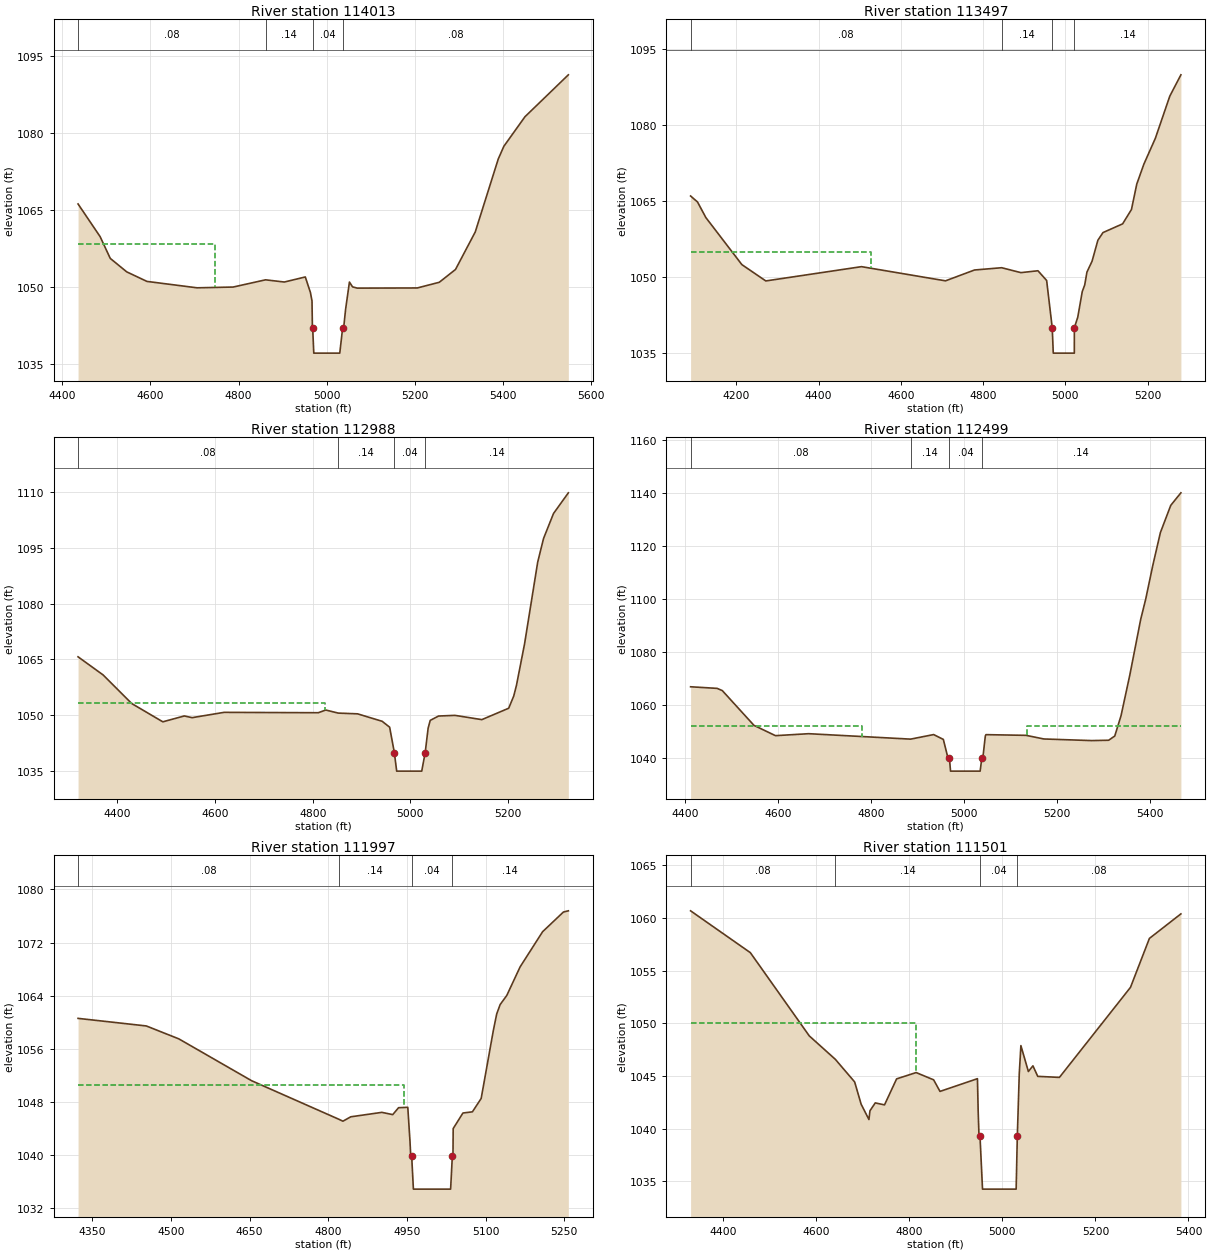
Type RM Length L Ch R = 1,114013,516,516,516
BEGIN DESCRIPTION:
Fisher River 228.0
END DESCRIPTION:
XS GIS Cut Line= 3
      1492800.68       974374.14      1492426.54       973879.03
      1491945.46       973777.75
#Sta/Elev= 30
  4435.8 1066.21  4485.8 1059.84  4508.9 1055.58  4546.3 1052.95  4592.1 1051.09
  4705.9 1049.84  4787.6 1049.99  4861.1 1051.40  4903.7 1050.97  4951.3 1051.96
  4963.0 1048.90  4966.5 1047.27  4967.4 1042.09  4968.0 1042.09  4970.5 1037.09
  5029.5 1037.09  5036.1 1042.09  5038.5 1042.20  5042.7 1045.64  5051.4 1050.96
  5058.5 1050.02  5069.2 1049.78  5205.2 1049.81  5255.2 1050.92  5292.0 1053.42
  5336.8 1060.74  5389.0 1074.99  5401.7 1077.47  5449.6 1083.24  5548.0 1091.42
#Mann=4,-1,0
  4435.8    0.08       0  4861.1    0.14       0  4968.0    0.04       0
  5036.1    0.08       0
#XS Ineff=2,0
    0.00 4745.70 1058.43               0
Permanent Ineff=
       F       F
Bank Sta=4968,5036.1
XS Rating Curve= 0
Exp/Cntr=0.3,0.1

Type RM Length L Ch R = 1,113497,509,509,509
BEGIN DESCRIPTION:
Fisher River 227.0
END DESCRIPTION:
XS GIS Cut Line= 4
      1492820.36       974360.05      1492626.26       973549.91
      1492584.06       973369.87      1492682.53       973226.39
#Sta/Elev= 30
  4088.8 1065.95  4105.6 1064.77  4125.9 1061.69  4213.5 1052.40  4271.6 1049.18
  4504.3 1052.00  4708.5 1049.20  4779.0 1051.34  4845.1 1051.79  4891.8 1050.82
  4933.3 1051.19  4954.4 1049.27  4968.0 1039.93  4970.5 1034.93  5021.7 1034.93
  5021.8 1039.93  5030.1 1042.04  5041.0 1047.08  5046.9 1048.38  5052.4 1050.93
  5064.8 1053.07  5079.0 1057.22  5091.4 1058.73  5139.1 1060.45  5160.6 1063.28
  5173.5 1068.30  5190.9 1072.26  5218.7 1077.34  5253.8 1085.66  5280.8 1089.87
#Mann=4,-1,0
  4088.8    0.08       0  4845.1    0.14       0  4968.0    0.04       0
  5021.8    0.14       0
#XS Ineff=2,0
    0.00 4526.50 1054.94               0
Permanent Ineff=
       F       F
Bank Sta=4968,5021.8
XS Rating Curve= 0
Exp/Cntr=0.3,0.1

Type RM Length L Ch R = 1,112988,489,489,489
BEGIN DESCRIPTION:
Fisher River 226.0
END DESCRIPTION:
XS GIS Cut Line= 5
      1492834.42       974345.98      1492764.10       974064.69
      1492980.70       973811.52      1493045.40       973690.56
      1493093.23       973451.41
#Sta/Elev= 30
  4319.4 1065.71  4370.7 1060.83  4429.3 1053.13  4493.0 1048.20  4537.0 1049.78
  4553.0 1049.32  4618.4 1050.75  4811.4 1050.65  4826.7 1051.38  4852.3 1050.55
  4891.9 1050.35  4942.3 1048.34  4957.6 1046.75  4967.2 1039.92  4972.0 1034.92
  5023.3 1034.92  5030.4 1039.92  5036.4 1046.48  5040.7 1048.58  5057.7 1049.76
  5091.3 1049.94  5146.4 1048.79  5201.4 1051.86  5211.7 1055.13  5217.3 1058.01
  5233.9 1069.19  5260.8 1091.21  5272.8 1097.59  5293.2 1104.31  5323.6 1109.88
#Mann=4,-1,0
  4319.4    0.08       0  4852.3    0.14       0  4967.2    0.04       0
  5030.4    0.14       0
#XS Ineff=2,0
    0.00 4824.90 1053.38               0
Permanent Ineff=
       F       F
Bank Sta=4967.2,5030.4
XS Rating Curve= 0
Exp/Cntr=0.3,0.1

Type RM Length L Ch R = 1,112499,502,502,502
BEGIN DESCRIPTION:
Fisher River 225.0
END DESCRIPTION:
XS GIS Cut Line= 4
      1493056.64       974376.94      1493422.34       974039.37
      1493484.23       973887.47      1493520.80       973496.49
#Sta/Elev= 30
  4411.5 1066.73  4468.6 1066.13  4479.7 1065.29  4547.8 1052.17  4594.0 1048.29
  4665.6 1049.03  4884.7 1046.98  4934.1 1048.70  4955.0 1046.88  4964.8 1039.99
  4968.0 1039.91  4970.5 1034.91  5034.2 1034.91  5037.8 1039.91  5040.0 1039.91
  5045.3 1048.16  5046.7 1048.67  5132.9 1048.41  5171.2 1047.04  5274.2 1046.43
  5310.6 1046.56  5323.7 1048.16  5337.2 1055.85  5356.1 1071.21  5379.5 1092.20
  5390.3 1099.86  5405.5 1112.55  5421.8 1124.90  5444.1 1135.18  5465.9 1139.90
#Mann=4,-1,0
  4411.5    0.08       0  4884.7    0.14       0  4968.0    0.04       0
  5037.8    0.14       0
#XS Ineff=2,0
    0.00 4780.00 1052.00 5134.30    0.00 1052.00
Permanent Ineff=
       F       F
Bank Sta=4968,5037.8
XS Rating Curve= 0
Exp/Cntr=0.3,0.1

Type RM Length L Ch R = 1,111997,496,496,496
BEGIN DESCRIPTION:
Fisher River 224.0
END DESCRIPTION:
XS GIS Cut Line= 4
      1493394.18       974565.44      1493858.36       974188.46
      1493968.07       974101.26      1494159.36       974053.43
#Sta/Elev= 30
  4322.7 1060.60  4452.9 1059.46  4515.1 1057.51  4653.8 1051.22  4820.2 1045.42
  4828.0 1045.13  4842.9 1045.79  4902.2 1046.46  4923.0 1046.12  4934.1 1047.16
  4951.7 1047.22  4955.9 1042.12  4957.3 1039.91  4959.1 1039.91  4962.4 1034.91
  5033.4 1034.91  5036.7 1039.91  5037.9 1039.91  5038.3 1044.02  5056.9 1046.36
  5075.0 1046.54  5091.7 1048.55  5114.9 1058.78  5121.3 1061.26  5127.9 1062.68
  5140.5 1064.04  5166.0 1068.35  5208.9 1073.64  5248.6 1076.60  5258.0 1076.78
#Mann=4,-1,0
  4322.7    0.08       0  4820.2    0.14       0  4959.1    0.04       0
  5036.7    0.14       0
#XS Ineff=2,0
    0.00 4944.10 1050.61               0
Permanent Ineff=
       F       F
Bank Sta=4959.1,5036.7
XS Rating Curve= 0
Exp/Cntr=0.3,0.1

Type RM Length L Ch R = 1,111501,502,502,502
BEGIN DESCRIPTION:
Fisher River 223.0
END DESCRIPTION:
XS GIS Cut Line= 4
      1493394.21       974582.28      1493959.63       974596.35
      1494139.66       974599.16      1494409.69       974450.08
#Sta/Elev= 30
  4329.6 1060.69  4458.0 1056.72  4584.8 1048.81  4640.7 1046.59  4682.3 1044.44
  4696.3 1042.32  4713.0 1040.87  4715.2 1041.70  4726.6 1042.45  4746.5 1042.26
  4772.5 1044.73  4814.5 1045.33  4852.1 1044.64  4865.8 1043.54  4946.3 1044.75
  4947.9 1041.59  4949.6 1039.35  4951.8 1039.26  4957.2 1034.26  5029.5 1034.26
  5032.0 1039.26  5036.2 1045.21  5039.7 1047.89  5055.8 1045.43  5065.6 1045.97
  5075.9 1044.97  5122.5 1044.87  5275.3 1053.42  5316.0 1058.07  5383.7 1060.40
#Mann=4,-1,0
  4329.6    0.08       0  4640.7    0.14       0  4951.8    0.04       0
  5032.0    0.08       0
#XS Ineff=2,0
    0.00 4813.60 1050.00               0
Permanent Ineff=
       F       F
Bank Sta=4951.8,5032
XS Rating Curve= 0
Exp/Cntr=0.3,0.1

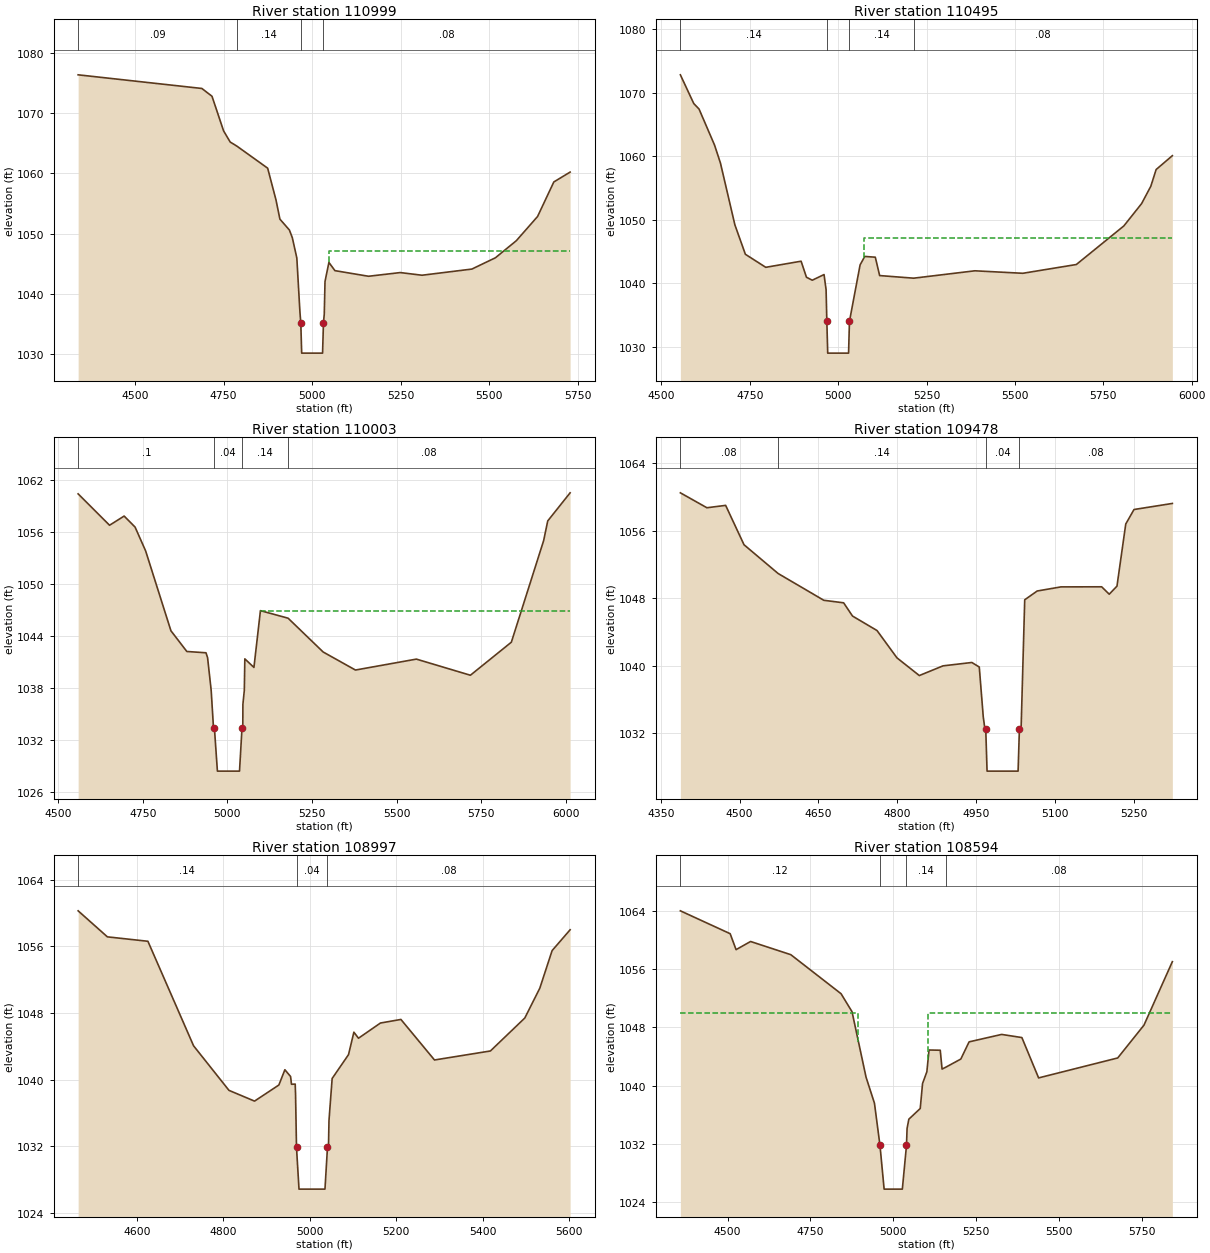
Type RM Length L Ch R = 1,110999,504,504,504
BEGIN DESCRIPTION:
Fisher River 222.0
END DESCRIPTION:
XS GIS Cut Line= 4
      1493683.97       975600.56      1493903.97       975193.73
      1494150.92       975049.24      1494463.16       974489.45
#Sta/Elev= 30
  4339.1 1076.31  4688.6 1074.05  4717.2 1072.76  4749.9 1067.03  4768.6 1065.18
  4787.8 1064.49  4874.4 1060.85  4897.9 1055.60  4909.0 1052.41  4935.8 1050.61
  4944.1 1049.33  4956.8 1045.97  4965.6 1036.99  4968.0 1035.22  4970.5 1030.22
  5029.5 1030.22  5032.0 1035.22  5034.3 1036.68  5036.4 1042.09  5047.4 1045.24
  5064.4 1043.88  5159.3 1042.95  5248.9 1043.56  5310.5 1043.12  5451.2 1044.14
  5517.7 1046.01  5576.8 1048.84  5636.8 1052.85  5682.7 1058.57  5728.7 1060.20
#Mann=4,-1,0
  4339.1    0.09       0  4787.8    0.14       0  4968.0    0.04       0
  5032.0    0.08       0
#XS Ineff=2,0
       0                 5047.40    0.00 1047.20
Permanent Ineff=
       F       F
Bank Sta=4968,5032
XS Rating Curve= 0
Exp/Cntr=0.3,0.1

Type RM Length L Ch R = 1,110495,492,492,492
BEGIN DESCRIPTION:
Fisher River 221.0
END DESCRIPTION:
XS GIS Cut Line= 4
      1494187.48       975814.39      1494375.96       975552.78
      1494471.60       975333.36      1494477.23       974503.47
#Sta/Elev= 30
  4553.7 1072.80  4591.6 1068.28  4606.5 1067.42  4650.3 1061.76  4667.1 1058.91
  4707.9 1049.20  4737.6 1044.57  4795.2 1042.52  4895.2 1043.48  4910.3 1040.96
  4926.8 1040.49  4960.1 1041.38  4965.9 1038.99  4968.0 1034.02  4970.5 1029.02
  5029.5 1029.02  5032.0 1034.02  5062.1 1042.90  5075.3 1044.23  5105.1 1044.11
  5117.4 1041.22  5213.7 1040.81  5386.8 1041.97  5522.4 1041.58  5673.8 1042.96
  5808.2 1049.03  5858.4 1052.54  5884.4 1055.26  5899.5 1057.90  5945.4 1060.08
#Mann=4,-1,0
  4553.7    0.14       0  4968.0    0.04       0  5032.0    0.14       0
  5213.7    0.08       0
#XS Ineff=2,0
       0                 5072.50    0.00 1047.16
Permanent Ineff=
       F       F
Bank Sta=4968,5032
XS Rating Curve= 0
Exp/Cntr=0.3,0.1

Type RM Length L Ch R = 1,110003,525,525,525
BEGIN DESCRIPTION:
Fisher River 220.0
END DESCRIPTION:
XS GIS Cut Line= 3
      1495197.35       975741.24      1494938.56       975479.64
      1494494.12       974489.48
#Sta/Elev= 30
  4559.1 1060.38  4651.9 1056.76  4695.0 1057.82  4727.3 1056.55  4758.5 1053.80
  4833.2 1044.59  4880.2 1042.20  4936.8 1042.05  4941.5 1041.48  4952.1 1037.72
  4958.9 1033.40  4961.6 1033.40  4970.5 1028.40  5035.8 1028.40  5043.2 1033.40
  5045.5 1033.45  5045.8 1036.10  5050.0 1037.73  5051.5 1041.35  5078.4 1040.36
  5097.6 1046.91  5179.3 1046.04  5282.9 1042.14  5378.3 1040.06  5558.3 1041.32
  5717.8 1039.46  5838.8 1043.27  5934.2 1054.99  5946.3 1057.26  6012.4 1060.50
#Mann=4,-1,0
  4559.1     0.1       0  4961.6    0.04       0  5043.2    0.14       0
  5179.3    0.08       0
#XS Ineff=2,0
       0                 5097.60    0.00 1046.92
Permanent Ineff=
       F       F
Bank Sta=4961.6,5043.2
XS Rating Curve= 0
Exp/Cntr=0.3,0.1

Type RM Length L Ch R = 1,109478,481,481,481
BEGIN DESCRIPTION:
Fisher River 219.0
END DESCRIPTION:
XS GIS Cut Line= 4
      1495281.75       975769.37      1495377.39       975232.09
      1495357.70       975097.07      1495523.65       974905.80
#Sta/Elev= 30
  4387.4 1060.52  4437.8 1058.75  4473.5 1059.03  4508.4 1054.36  4573.2 1050.95
  4660.1 1047.77  4697.8 1047.47  4714.7 1045.90  4761.3 1044.18  4799.2 1040.94
  4841.7 1038.84  4886.8 1039.99  4941.6 1040.39  4955.7 1039.85  4963.3 1033.92
  4966.4 1032.50  4968.0 1032.50  4970.5 1027.50  5029.5 1027.50  5032.0 1032.50
  5035.2 1032.52  5042.1 1047.83  5065.8 1048.87  5111.0 1049.36  5188.4 1049.37
  5202.8 1048.49  5217.5 1049.45  5234.2 1056.82  5249.9 1058.54  5322.8 1059.26
#Mann=4,-1,0
  4387.4    0.08       0  4573.2    0.14       0  4968.0    0.04       0
  5032.0    0.08       0
Bank Sta=4968,5032
XS Rating Curve= 0
Exp/Cntr=0.3,0.1

Type RM Length L Ch R = 1,108997,403,403,403
BEGIN DESCRIPTION:
Fisher River 218.0
END DESCRIPTION:
XS GIS Cut Line= 3
      1495304.81       975791.61      1495775.15       975411.28
      1495613.11       974902.65
#Sta/Elev= 30
  4464.1 1060.25  4531.8 1057.13  4625.6 1056.60  4731.3 1044.07  4813.2 1038.73
  4872.4 1037.44  4928.7 1039.37  4942.6 1041.20  4955.8 1040.39  4957.9 1039.46
  4966.5 1039.48  4967.3 1038.31  4969.5 1031.89  4975.3 1026.89  5035.4 1026.89
  5041.2 1031.89  5043.5 1031.90  5044.7 1035.12  5052.0 1040.15  5089.9 1043.01
  5102.3 1045.70  5113.0 1044.98  5163.8 1046.80  5211.2 1047.23  5288.9 1042.37
  5418.3 1043.45  5497.9 1047.40  5532.6 1050.97  5561.1 1055.48  5602.8 1057.98
#Mann=3,-1,0
  4464.1    0.14       0  4969.5    0.04       0  5041.2    0.08       0
Bank Sta=4969.5,5041.2
XS Rating Curve= 0
Exp/Cntr=0.5,0.3

Type RM Length L Ch R = 1,108594,134,134,134
BEGIN DESCRIPTION:
Prison Camp Rd - US
END DESCRIPTION:
XS GIS Cut Line= 5
      1496085.43       976285.83      1496057.15       976000.12
      1496024.95       975715.09      1495853.92       975485.54
      1495660.40       974891.48
#Sta/Elev= 30
  4357.5 1064.01  4507.8 1060.87  4525.6 1058.68  4569.4 1059.80  4690.8 1057.99
  4842.5 1052.63  4875.6 1050.16  4917.9 1041.18  4943.3 1037.60  4960.0 1031.80
  4972.5 1025.80  5027.5 1025.80  5040.0 1031.80  5041.8 1034.14  5047.1 1035.40
  5081.5 1036.87  5088.5 1040.30  5101.5 1041.91  5108.0 1044.90  5141.9 1044.87
  5147.4 1042.28  5159.9 1042.57  5204.0 1043.66  5229.0 1046.02  5327.1 1047.04
  5388.3 1046.61  5438.8 1041.07  5677.6 1043.81  5756.8 1048.31  5842.5 1057.03
#Mann=4,-1,0
  4357.5    0.12       0  4960.0    0.04       0  5040.0    0.14       0
  5159.9    0.08       0
#XS Ineff=2,0
    0.00 4895.00 1050.00 5105.00    0.00 1050.00
Permanent Ineff=
       F       F
Bank Sta=4960,5040
XS Rating Curve= 0
Exp/Cntr=0.5,0.3

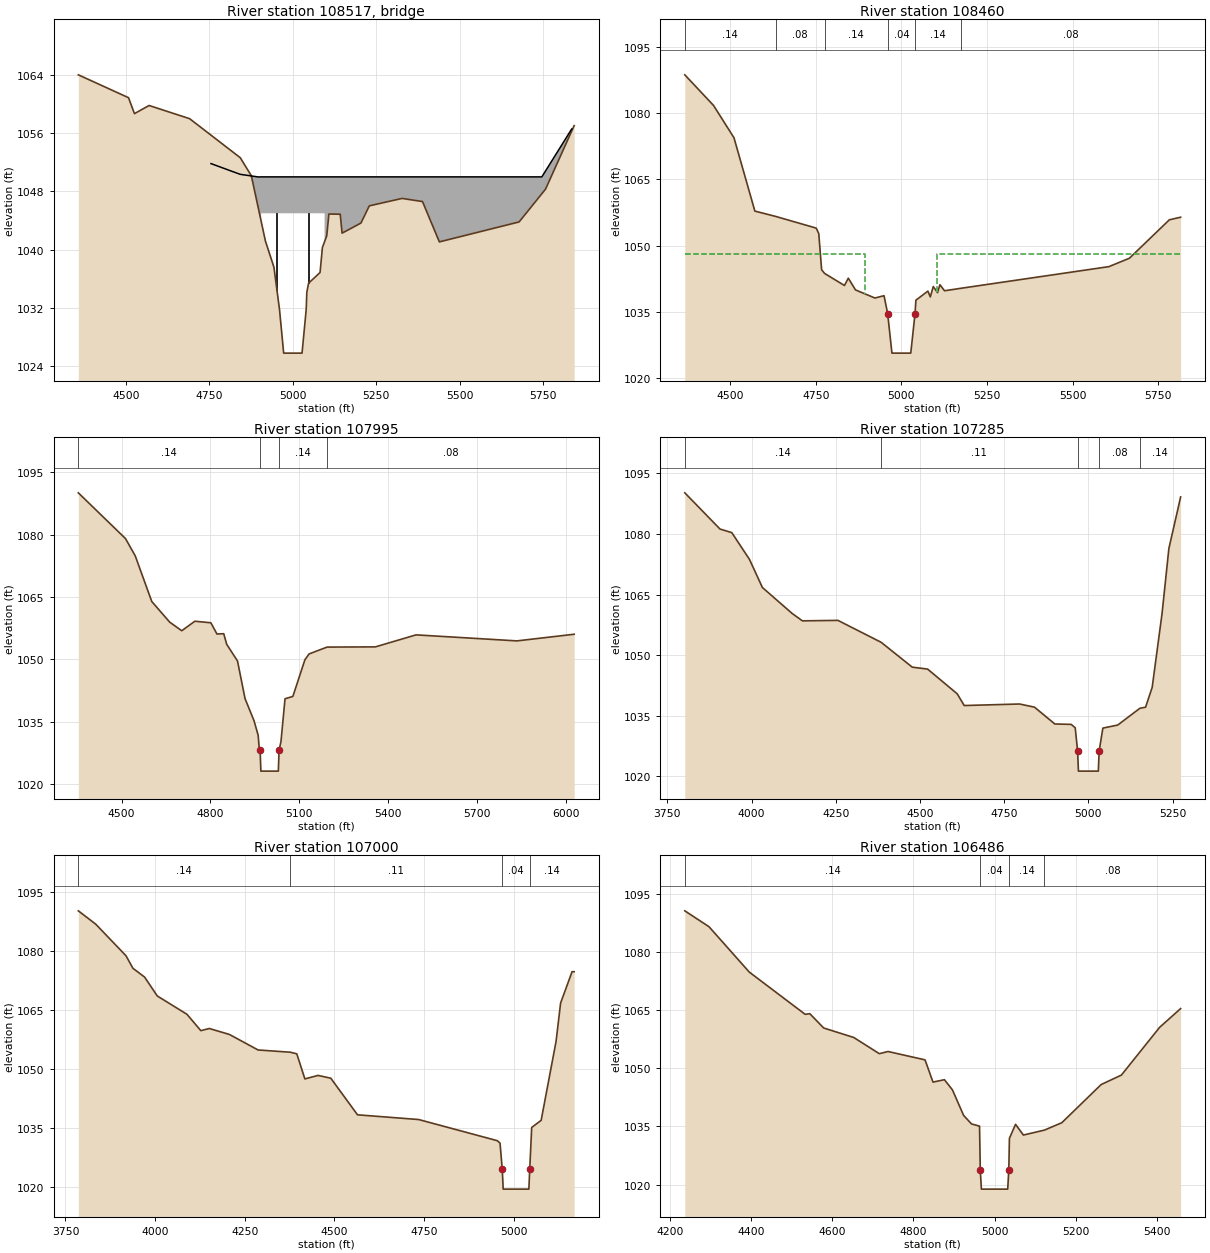
Type RM Length L Ch R =3,108517,,,
BEGIN DESCRIPTION:
Prison Camp Rd - TOR
Structure ID: LDS_FR_09
Approximate Survey Structure
END DESCRIPTION:
Bridge Culvert--1,0,-1,-1,0
Deck Dist Width WeirC Skew NumUp NumDn MinLoCord MaxHiCord MaxSubmerge Is_Ogee
61,32,3,,11,11,,,0.95,0,1,1,,,
  4754.8  4823.1  4842.2  4896.2  4904.3  4905.0  4905.0  5095.0  5095.0  5745.7
  5835.1
 1051.82 1050.67 1050.35 1049.99 1050.00 1050.00 1050.00 1050.00 1050.00 1050.00
 1056.57
 1005.80 1005.80 1005.80 1005.80 1005.80 1005.80 1045.00 1045.00 1005.80 1005.80
 1005.80
  4754.8  4823.1  4842.2  4896.2  4904.3  4905.0  4905.0  5095.0  5095.0  5745.7
  5835.1
 1051.82 1050.67 1050.35 1049.99 1050.00 1050.00 1050.00 1050.00 1050.00 1050.00
 1056.57
 1005.80 1005.80 1005.80 1005.80 1005.80 1005.80 1045.00 1045.00 1005.80 1005.80
 1005.80
Pier Skew, UpSta & Num, DnSta & Num=,4952.5,2,4952.5,2,0,0,0,0,0
       3       3
 1038.22 1045.00
       3       3
 1040.05 1045.00
Pier Skew, UpSta & Num, DnSta & Num=,5047.5,2,5047.5,2,0,0,0,0,0
       3       3
 1035.40 1045.00
       3       3
 1037.52 1045.00
Abutment Skew #Up #Dn=,2,2
  4905.0  4935.0
 1045.00 1038.46
  4905.0  4934.3
 1045.00 1038.23
Abutment Skew #Up #Dn=,2,2
  5066.8  5095.0
 1036.65 1045.00
  5065.4  5095.0
 1038.41 1045.00
BR Coef=1,1,0,1.25,0,,,0.8,0,2,0,
WSPro=,,,, 1 ,,,, 0 ,,,, 0 ,,,,-1 ,-1 ,-1 , 0 , 0 , 0 , 0 , 0
BC Design=,,0,,0,,,,,,

Type RM Length L Ch R = 1,108460,465,465,465
BEGIN DESCRIPTION:
Prison Camp Rd - DS
END DESCRIPTION:
XS GIS Cut Line= 5
      1496498.44       976062.33      1496325.80       975882.66
      1496125.04       975623.87      1495943.94       975391.03
      1495714.39       974862.18
#Sta/Elev= 30
  4367.5 1088.78  4451.5 1081.82  4511.1 1074.49  4572.2 1057.82  4632.9 1056.61
  4751.4 1053.95  4758.9 1052.67  4767.1 1044.49  4776.0 1043.65  4833.8 1040.92
  4845.1 1042.58  4866.1 1039.91  4922.9 1038.07  4949.4 1038.60  4960.0 1034.55
  4972.5 1025.55  5027.5 1025.55  5040.0 1034.55  5042.5 1037.57  5077.5 1039.64
  5084.6 1038.32  5093.2 1040.67  5105.7 1039.30  5112.7 1041.09  5126.1 1039.72
  5173.0 1040.27  5606.2 1045.20  5666.2 1047.11  5782.8 1055.84  5815.7 1056.43
#Mann=6,-1,0
  4367.5    0.14       0  4632.9    0.08       0  4776.0    0.14       0
  4960.0    0.04       0  5040.0    0.14       0  5173.0    0.08       0
#XS Ineff=2,0
    0.00 4895.00 1048.00 5105.00    0.00 1048.00
Permanent Ineff=
       F       F
Bank Sta=4960,5040
XS Rating Curve= 0
Exp/Cntr=0.5,0.3

Type RM Length L Ch R = 1,107995,710,710,710
BEGIN DESCRIPTION:
Fisher River 216.0
END DESCRIPTION:
XS GIS Cut Line= 4
      1496516.99       976069.24      1496609.52       975619.68
      1496458.26       975295.97      1495729.14       974842.16
#Sta/Elev= 30
  4353.8 1090.04  4513.2 1079.03  4546.1 1074.87  4601.9 1063.90  4662.4 1058.94
  4703.2 1056.86  4747.4 1059.15  4801.5 1058.78  4822.1 1056.08  4845.0 1056.15
  4855.1 1053.60  4891.6 1049.58  4917.0 1040.54  4947.3 1035.23  4961.3 1031.73
  4965.5 1028.09  4968.0 1028.09  4970.5 1023.09  5029.5 1023.09  5032.0 1028.09
  5038.4 1030.21  5052.1 1040.50  5078.6 1041.06  5119.2 1049.87  5133.3 1051.28
  5194.2 1052.93  5357.4 1052.98  5494.8 1055.87  5835.5 1054.42  6028.9 1056.02
#Mann=4,-1,0
  4353.8    0.14       0  4968.0    0.04       0  5032.0    0.14       0
  5194.2    0.08       0
Bank Sta=4968,5032
XS Rating Curve= 0
Exp/Cntr=0.3,0.1

Type RM Length L Ch R = 1,107285,285,285,285
BEGIN DESCRIPTION:
Fisher River 215.0
END DESCRIPTION:
XS GIS Cut Line= 5
      1496532.04       976064.65      1496624.65       975625.73
      1497157.10       975217.31      1497169.20       975072.09
      1497051.22       974902.68
#Sta/Elev= 30
  3802.0 1090.19  3906.5 1081.22  3941.5 1080.33  3994.0 1073.70  4032.4 1066.73
  4121.0 1060.28  4151.2 1058.47  4256.5 1058.59  4385.0 1053.15  4477.2 1047.00
  4522.8 1046.52  4610.7 1040.39  4631.4 1037.49  4795.8 1037.87  4840.0 1037.09
  4900.4 1032.92  4949.0 1032.82  4960.9 1031.98  4968.0 1026.24  4970.5 1021.24
  5029.5 1021.24  5032.0 1026.24  5043.0 1031.90  5087.0 1032.65  5152.9 1036.81
  5169.8 1037.08  5189.4 1041.99  5218.8 1060.37  5238.9 1076.37  5273.8 1089.16
#Mann=5,-1,0
  3802.0    0.14       0  4385.0    0.11       0  4968.0    0.04       0
  5032.0    0.08       0  5152.9    0.14       0
Bank Sta=4968,5032
XS Rating Curve= 0
Exp/Cntr=0.3,0.1

Type RM Length L Ch R = 1,107000,514,514,514
BEGIN DESCRIPTION:
Fisher River 214.0
END DESCRIPTION:
XS GIS Cut Line= 5
      1496541.32       976063.48      1496633.72       975655.98
      1497266.01       975289.92      1497359.80       975332.27
      1497417.28       975450.26
#Sta/Elev= 30
  3785.8 1090.29  3834.4 1086.89  3918.8 1078.84  3938.1 1075.66  3970.5 1073.43
  4006.0 1068.61  4088.7 1063.95  4127.4 1059.78  4151.0 1060.33  4206.9 1058.82
  4287.1 1054.86  4376.9 1054.29  4395.0 1053.88  4417.5 1047.50  4454.3 1048.38
  4489.8 1047.67  4564.3 1038.35  4734.8 1037.15  4953.9 1031.77  4961.7 1031.15
  4968.0 1024.43  4970.5 1019.43  5042.1 1019.43  5044.5 1024.43  5050.0 1035.13
  5076.4 1036.95  5118.0 1057.07  5130.6 1066.80  5162.6 1074.80  5168.4 1074.79
#Mann=4,-1,0
  3785.8    0.14       0  4376.9    0.11       0  4968.0    0.04       0
  5044.5    0.14       0
Bank Sta=4968,5044.5
XS Rating Curve= 0
Exp/Cntr=0.3,0.1

Type RM Length L Ch R = 1,106486,471,471,471
BEGIN DESCRIPTION:
Fisher River 213.0
END DESCRIPTION:
XS GIS Cut Line= 6
      1496545.99       976070.46      1496648.30       975666.38
      1496857.60       975598.50      1497039.11       975734.64
      1497202.29       975740.17      1497296.28       975568.21
#Sta/Elev= 30
  4236.0 1090.67  4295.8 1086.56  4395.0 1074.86  4532.9 1063.95  4544.4 1064.11
  4578.6 1060.42  4652.8 1057.97  4715.8 1053.79  4737.4 1054.35  4828.6 1052.19
  4848.2 1046.45  4876.4 1047.07  4896.2 1044.44  4923.7 1037.86  4943.2 1035.65
  4962.8 1035.09  4963.0 1035.04  4964.8 1023.82  4967.6 1018.82  5032.5 1018.82
  5035.2 1023.82  5036.7 1031.92  5051.8 1035.55  5071.2 1032.78  5123.2 1034.06
  5166.0 1035.97  5263.0 1045.82  5312.9 1048.26  5407.2 1060.59  5459.0 1065.43
#Mann=4,-1,0
  4236.0    0.14       0  4964.8    0.04       0  5035.2    0.14       0
  5123.2    0.08       0
#XS Ineff=2,0
       0                 5051.80    0.00 1035.55
Permanent Ineff=
       F       F
Bank Sta=4964.8,5035.2
XS Rating Curve= 0
Exp/Cntr=0.3,0.1

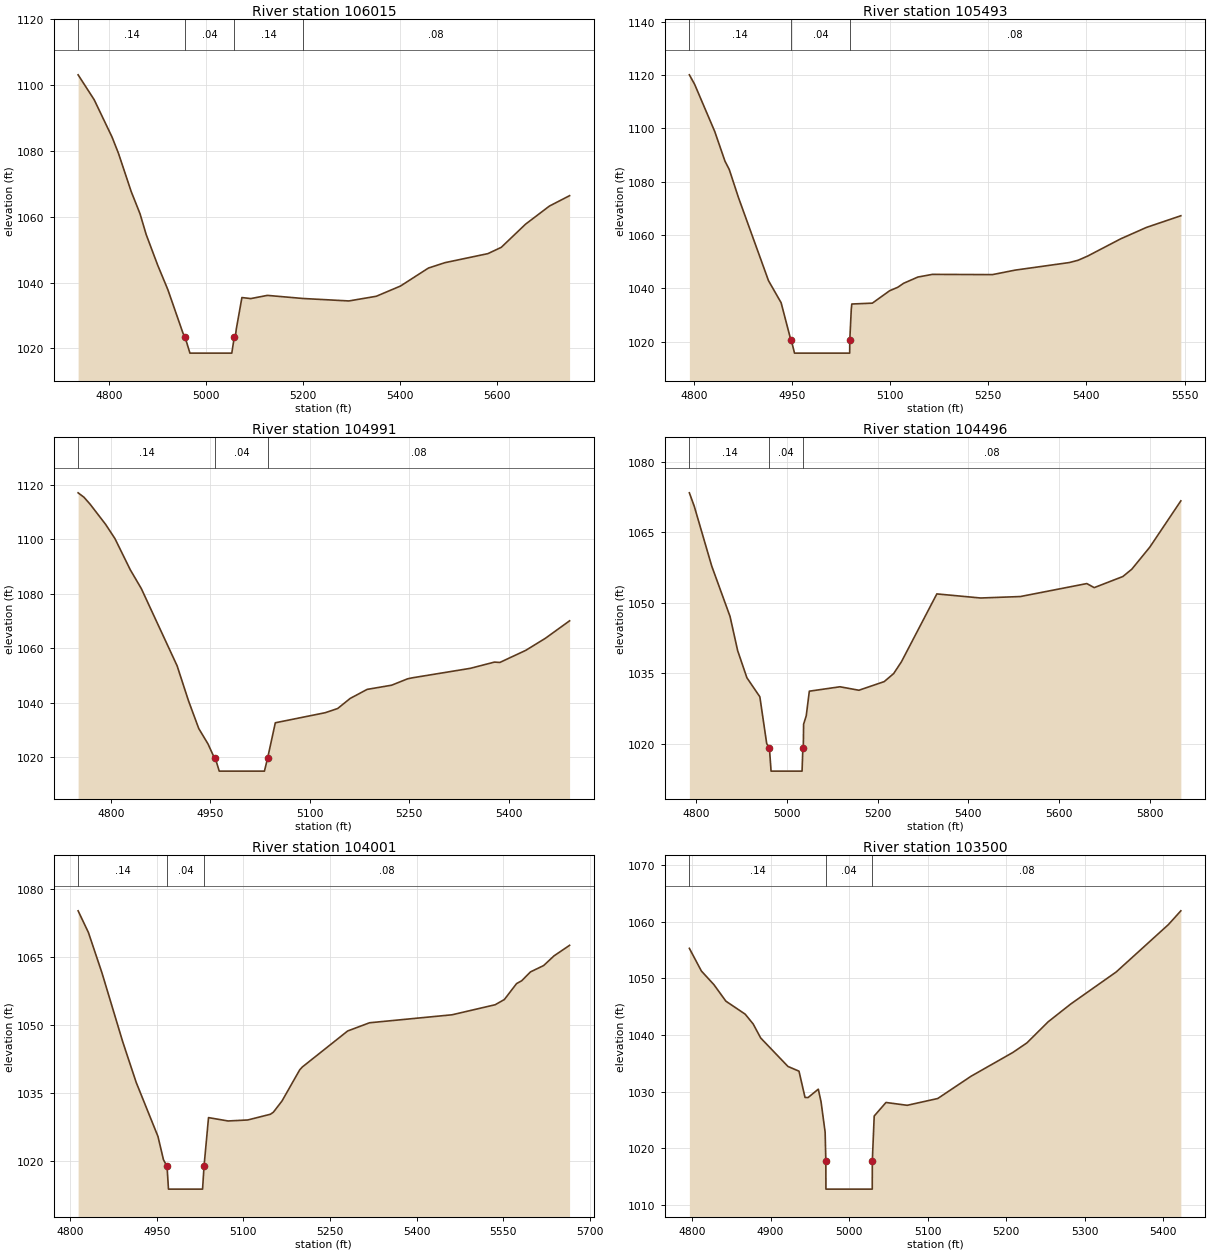
Type RM Length L Ch R = 1,106015,522,522,522
BEGIN DESCRIPTION:
Fisher River 212.0
END DESCRIPTION:
XS GIS Cut Line= 5
      1496582.34       976200.52      1496778.96       976119.70
      1496893.90       976049.27      1497226.68       975776.99
      1497305.34       975556.14
#Sta/Elev= 30
  4736.9 1103.14  4770.0 1095.57  4806.8 1084.21  4820.0 1079.27  4846.2 1067.66
  4864.4 1060.89  4877.0 1054.61  4900.9 1045.22  4921.7 1037.83  4952.8 1024.62
  4956.8 1023.55  4967.1 1018.55  5053.3 1018.55  5058.5 1023.55  5060.6 1023.55
  5062.5 1025.81  5074.1 1035.44  5092.5 1035.13  5126.5 1036.10  5199.7 1035.16
  5294.4 1034.41  5350.7 1035.83  5400.4 1038.93  5458.1 1044.41  5492.2 1046.05
  5580.5 1048.79  5608.1 1050.71  5658.0 1057.74  5707.2 1063.25  5748.7 1066.41
#Mann=4,-1,0
  4736.9    0.14       0  4956.8    0.04       0  5058.5    0.14       0
  5199.7    0.08       0
#XS Ineff=2,0
       0                 5126.50    0.00 1036.10
Permanent Ineff=
       F       F
Bank Sta=4956.8,5058.5
XS Rating Curve= 0
Exp/Cntr=0.3,0.1

Type RM Length L Ch R = 1,105493,502,502,502
BEGIN DESCRIPTION:
Fisher River 211.0
END DESCRIPTION:
XS GIS Cut Line= 3
      1497402.16       976258.03      1497235.76       975825.40
      1497320.48       975550.07
#Sta/Elev= 30
  4792.8 1120.09  4800.8 1116.55  4831.6 1098.83  4847.2 1087.73  4853.8 1084.57
  4867.8 1074.10  4913.8 1042.86  4933.1 1034.58  4947.9 1020.66  4948.5 1020.66
  4953.6 1015.66  5038.0 1015.66  5038.1 1020.66  5038.2 1020.89  5040.4 1032.10
  5041.2 1034.09  5072.6 1034.41  5099.0 1039.06  5111.6 1040.38  5120.4 1041.86
  5142.3 1044.21  5164.4 1045.21  5256.3 1045.12  5290.8 1046.80  5373.9 1049.65
  5387.2 1050.50  5401.9 1052.08  5452.6 1058.57  5491.8 1062.83  5544.4 1067.21
#Mann=3,-1,0
  4792.8    0.14       0  4948.5    0.04       0  5038.1    0.08       0
Bank Sta=4948.5,5038.1
XS Rating Curve= 0
Exp/Cntr=0.3,0.1

Type RM Length L Ch R = 1,104991,495,495,495
BEGIN DESCRIPTION:
Fisher River 210.0
END DESCRIPTION:
XS GIS Cut Line= 4
      1497810.57       976085.58      1497783.34       975870.78
      1497756.11       975773.97      1497453.56       975477.47
#Sta/Elev= 30
  4750.9 1117.15  4759.8 1115.51  4768.9 1112.99  4792.4 1105.53  4806.4 1100.32
  4829.6 1088.82  4846.1 1081.96  4900.1 1053.54  4917.1 1040.79  4932.7 1030.48
  4946.8 1024.74  4956.0 1019.80  4957.3 1019.80  4963.6 1014.80  5031.7 1014.80
  5036.7 1019.80  5048.1 1032.58  5123.4 1036.29  5142.1 1037.83  5160.9 1041.53
  5186.5 1044.86  5223.4 1046.40  5247.5 1048.75  5254.5 1049.11  5342.1 1052.61
  5378.4 1054.90  5386.5 1054.77  5425.5 1059.21  5455.0 1063.63  5491.6 1070.08
#Mann=3,-1,0
  4750.9    0.14       0  4957.3    0.04       0  5036.7    0.08       0
Bank Sta=4957.3,5036.7
XS Rating Curve= 0
Exp/Cntr=0.3,0.1

Type RM Length L Ch R = 1,104496,495,495,495
BEGIN DESCRIPTION:
Fisher River 209.0
END DESCRIPTION:
XS GIS Cut Line= 4
      1498325.00       975925.01      1498237.14       975671.11
      1497937.63       975525.89      1497462.63       975456.30
#Sta/Elev= 30
  4785.9 1073.42  4796.7 1070.55  4835.1 1057.84  4875.4 1047.12  4892.2 1039.83
  4912.5 1034.07  4941.0 1030.02  4956.1 1020.05  4962.0 1019.20  4965.7 1014.20
  5033.9 1014.20  5035.7 1019.20  5036.7 1019.44  5037.3 1024.19  5043.1 1025.97
  5049.9 1031.21  5117.4 1032.15  5159.0 1031.41  5214.7 1033.25  5235.4 1034.95
  5252.6 1037.47  5330.5 1051.91  5427.0 1051.04  5514.3 1051.35  5660.5 1054.11
  5676.9 1053.25  5739.9 1055.61  5759.6 1057.17  5799.1 1061.85  5867.5 1071.71
#Mann=3,-1,0
  4785.9    0.14       0  4962.0    0.04       0  5035.7    0.08       0
Bank Sta=4962,5035.7
XS Rating Curve= 0
Exp/Cntr=0.3,0.1

Type RM Length L Ch R = 1,104001,501,501,501
BEGIN DESCRIPTION:
Fisher River 208.0
END DESCRIPTION:
XS GIS Cut Line= 4
      1498802.85       975683.18      1498651.60       975432.11
      1498515.46       975214.28      1498621.35       974932.93
#Sta/Elev= 30
  4814.1 1075.19  4831.9 1070.43  4855.4 1061.51  4891.2 1046.38  4914.5 1037.42
  4952.3 1025.47  4961.8 1020.35  4968.0 1018.86  4970.5 1013.86  5029.5 1013.86
  5032.0 1018.86  5039.8 1029.62  5073.7 1028.88  5107.7 1029.10  5146.9 1030.36
  5152.1 1030.82  5166.9 1033.27  5197.6 1040.14  5202.1 1040.77  5280.6 1048.71
  5318.4 1050.52  5461.3 1052.28  5535.8 1054.49  5551.8 1055.64  5572.9 1059.15
  5581.8 1059.78  5597.0 1061.73  5619.8 1063.13  5637.7 1065.26  5664.7 1067.59
#Mann=3,-1,0
  4814.1    0.14       0  4968.0    0.04       0  5032.0    0.08       0
Bank Sta=4968,5032
XS Rating Curve= 0
Exp/Cntr=0.3,0.1

Type RM Length L Ch R = 1,103500,603,603,603
BEGIN DESCRIPTION:
Fisher River 207.0
END DESCRIPTION:
XS GIS Cut Line= 4
      1499066.07       975374.64      1499099.35       975214.28
      1499072.83       975184.83      1498775.64       974884.53
#Sta/Elev= 30
  4796.6 1055.31  4811.9 1051.31  4827.9 1048.89  4843.1 1045.98  4867.7 1043.68
  4877.9 1041.94  4887.4 1039.48  4922.2 1034.44  4936.2 1033.61  4943.9 1028.97
  4947.8 1028.95  4960.8 1030.43  4964.3 1028.21  4969.5 1022.83  4970.4 1017.77
  4970.5 1012.77  5029.5 1012.77  5029.6 1017.77  5032.0 1025.69  5047.0 1028.08
  5074.0 1027.58  5112.9 1028.78  5155.4 1032.72  5208.5 1036.91  5226.5 1038.61
  5253.5 1042.33  5282.5 1045.50  5340.2 1051.14  5406.6 1059.50  5422.5 1061.94
#Mann=3,-1,0
  4796.6    0.14       0  4970.4    0.04       0  5029.6    0.08       0
Bank Sta=4970.4,5029.6
XS Rating Curve= 0
Exp/Cntr=0.3,0.1

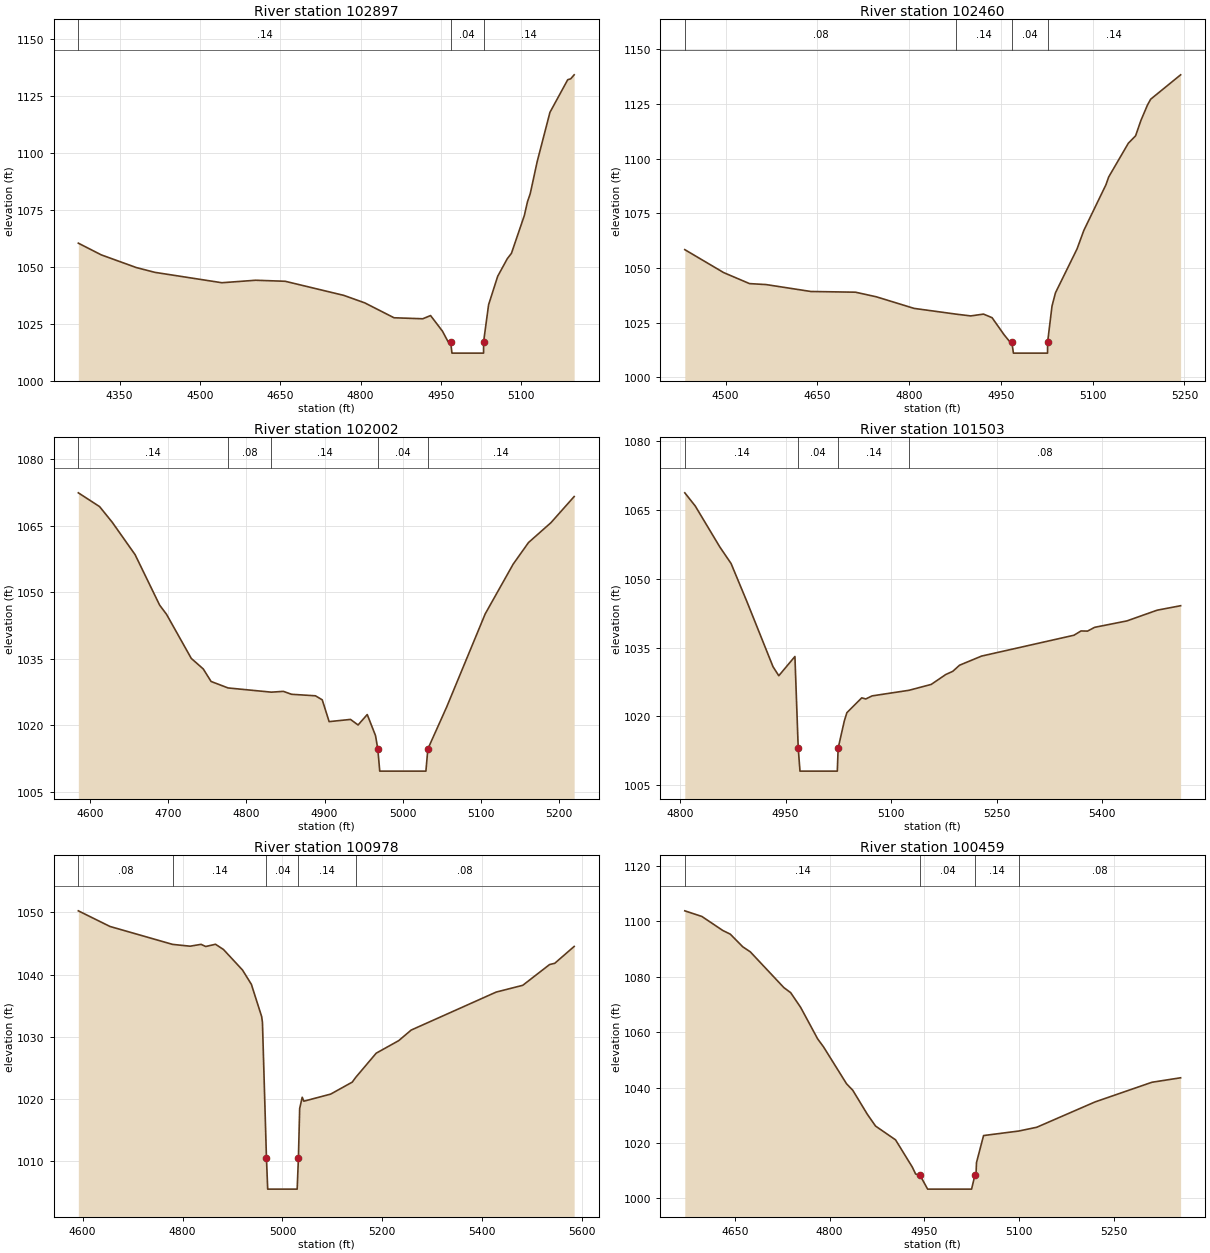
Type RM Length L Ch R = 1,102897,437,437,437
BEGIN DESCRIPTION:
Fisher River 206.0
END DESCRIPTION:
XS GIS Cut Line= 3
      1499066.08       975398.82      1499495.66       974899.65
      1499662.04       974690.92
#Sta/Elev= 30
  4273.1 1060.49  4316.0 1055.34  4381.4 1049.77  4416.0 1047.67  4541.0 1043.11
  4604.0 1044.20  4659.2 1043.75  4768.6 1037.56  4807.8 1034.26  4862.4 1027.72
  4916.0 1027.28  4930.6 1028.69  4952.8 1021.83  4963.2 1017.22  4968.0 1017.19
  4970.5 1012.19  5029.5 1012.19  5029.6 1017.19  5038.9 1033.45  5055.9 1045.96
  5073.9 1053.71  5081.5 1056.01  5105.6 1072.63  5111.5 1078.70  5116.6 1082.22
  5129.6 1096.32  5153.4 1117.95  5186.6 1132.28  5192.1 1132.67  5198.6 1134.43
#Mann=3,-1,0
  4273.1    0.14       0  4968.0    0.04       0  5029.6    0.14       0
Bank Sta=4968,5029.6
XS Rating Curve= 0
Exp/Cntr=0.3,0.1

Type RM Length L Ch R = 1,102460,458,458,458
BEGIN DESCRIPTION:
Fisher River 205.0
END DESCRIPTION:
XS GIS Cut Line= 4
      1499087.24       975398.83      1499302.04       975226.39
      1499616.68       975265.71      1499834.45       975259.66
#Sta/Elev= 30
  4433.4 1058.39  4496.9 1047.91  4539.2 1042.87  4566.3 1042.43  4639.5 1039.27
  4712.3 1038.95  4746.4 1036.85  4808.3 1031.54  4877.2 1028.91  4900.7 1028.11
  4921.6 1028.94  4935.6 1027.31  4955.4 1019.46  4965.0 1016.16  4968.0 1016.11
  4970.5 1011.11  5026.3 1011.11  5026.4 1016.11  5033.6 1032.63  5039.2 1038.65
  5074.5 1058.72  5085.6 1067.18  5121.7 1088.01  5126.2 1091.58  5158.3 1106.99
  5170.2 1110.40  5178.8 1117.35  5189.7 1124.53  5194.9 1127.13  5243.8 1138.26
#Mann=4,-1,0
  4433.4    0.08       0  4877.2    0.14       0  4968.0    0.04       0
  5026.4    0.14       0
Bank Sta=4968,5026.4
XS Rating Curve= 0
Exp/Cntr=0.3,0.1

Type RM Length L Ch R = 1,102002,499,499,499
BEGIN DESCRIPTION:
Fisher River 204.0
END DESCRIPTION:
XS GIS Cut Line= 3
      1499005.58       975574.60      1499292.97       975607.88
      1499589.43       975783.33
#Sta/Elev= 30
  4585.2 1072.41  4612.4 1069.30  4628.5 1065.79  4657.8 1058.47  4689.1 1047.12
  4697.9 1045.05  4729.6 1035.10  4744.9 1032.73  4754.9 1029.91  4776.6 1028.45
  4832.0 1027.50  4847.3 1027.68  4857.8 1027.02  4888.3 1026.68  4897.0 1025.77
  4905.8 1020.86  4933.1 1021.36  4942.8 1020.11  4954.5 1022.46  4965.1 1017.71
  4968.0 1014.71  4970.5 1009.71  5029.5 1009.71  5032.0 1014.71  5056.0 1024.14
  5105.3 1045.14  5141.0 1056.33  5160.6 1061.20  5189.3 1065.68  5219.0 1071.57
#Mann=5,-1,0
  4585.2    0.14       0  4776.6    0.08       0  4832.0    0.14       0
  4968.0    0.04       0  5032.0    0.14       0
Bank Sta=4968,5032
XS Rating Curve= 0
Exp/Cntr=0.3,0.1

Type RM Length L Ch R = 1,101503,525,525,525
BEGIN DESCRIPTION:
Fisher River 203.0
END DESCRIPTION:
XS GIS Cut Line= 3
      1498896.65       975910.41      1499181.03       976125.20
      1499519.84       976203.86
#Sta/Elev= 30
  4806.9 1068.70  4821.7 1065.84  4856.6 1056.92  4872.6 1053.31  4895.3 1044.94
  4932.2 1030.82  4940.4 1028.86  4963.3 1033.05  4968.0 1013.08  4970.5 1008.08
  5023.5 1008.08  5024.7 1013.08  5033.5 1019.04  5037.1 1020.81  5058.2 1024.04
  5063.9 1023.80  5073.0 1024.47  5125.4 1025.69  5156.9 1026.97  5177.5 1029.12
  5187.5 1029.82  5197.1 1031.15  5228.4 1033.14  5359.6 1037.68  5369.6 1038.61
  5378.9 1038.58  5388.9 1039.40  5434.8 1040.80  5477.6 1043.13  5511.1 1044.11
#Mann=4,-1,0
  4806.9    0.14       0  4968.0    0.04       0  5024.7    0.14       0
  5125.4    0.08       0
Bank Sta=4968,5024.7
XS Rating Curve= 0
Exp/Cntr=0.3,0.1

Type RM Length L Ch R = 1,100978,519,519,519
BEGIN DESCRIPTION:
Fisher River 202.0
END DESCRIPTION:
XS GIS Cut Line= 4
      1498715.17       976575.98      1498984.39       976606.23
      1499075.00       976375.00      1499522.93       976222.00
#Sta/Elev= 30
  4591.4 1050.25  4654.7 1047.74  4780.1 1044.86  4815.2 1044.57  4837.1 1044.87
  4846.4 1044.52  4866.0 1044.88  4882.0 1044.04  4920.0 1040.75  4937.8 1038.45
  4958.4 1033.27  4960.0 1032.34  4968.0 1010.56  4970.5 1005.56  5029.5 1005.56
  5032.0 1010.56  5034.5 1018.50  5039.6 1020.31  5042.9 1019.68  5096.6 1020.82
  5139.7 1022.74  5146.9 1023.52  5187.7 1027.39  5232.7 1029.40  5257.7 1031.10
  5427.8 1037.20  5481.1 1038.29  5534.9 1041.63  5545.1 1041.82  5584.0 1044.53
#Mann=5,-1,0
  4591.4    0.08       0  4780.1    0.14       0  4968.0    0.04       0
  5032.0    0.14       0  5146.9    0.08       0
Bank Sta=4968,5032
XS Rating Curve= 0
Exp/Cntr=0.3,0.1

Type RM Length L Ch R = 1,100459,462,462,462
BEGIN DESCRIPTION:
Fisher River 201.0
END DESCRIPTION:
XS GIS Cut Line= 3
      1499640.86       977087.21      1499483.56       976751.44
      1499595.49       976352.12
#Sta/Elev= 30
  4570.6 1103.79  4597.7 1101.75  4630.9 1096.68  4642.6 1095.38  4662.5 1090.79
  4674.4 1088.98  4727.5 1076.08  4738.3 1074.25  4754.1 1068.95  4781.1 1057.55
  4790.4 1054.66  4826.9 1041.33  4836.7 1039.01  4859.8 1030.33  4872.8 1026.08
  4904.5 1021.10  4931.0 1011.28  4936.3 1008.76  4943.3 1008.31  4955.3 1003.31
  5024.9 1003.31  5030.2 1008.31  5031.9 1008.31  5032.7 1012.88  5043.9 1022.65
  5099.8 1024.29  5128.2 1025.65  5220.6 1034.80  5310.6 1041.89  5356.1 1043.51
#Mann=4,-1,0
  4570.6    0.14       0  4943.3    0.04       0  5030.2    0.14       0
  5099.8    0.08       0
Bank Sta=4943.3,5030.2
XS Rating Curve= 0
Exp/Cntr=0.3,0.1