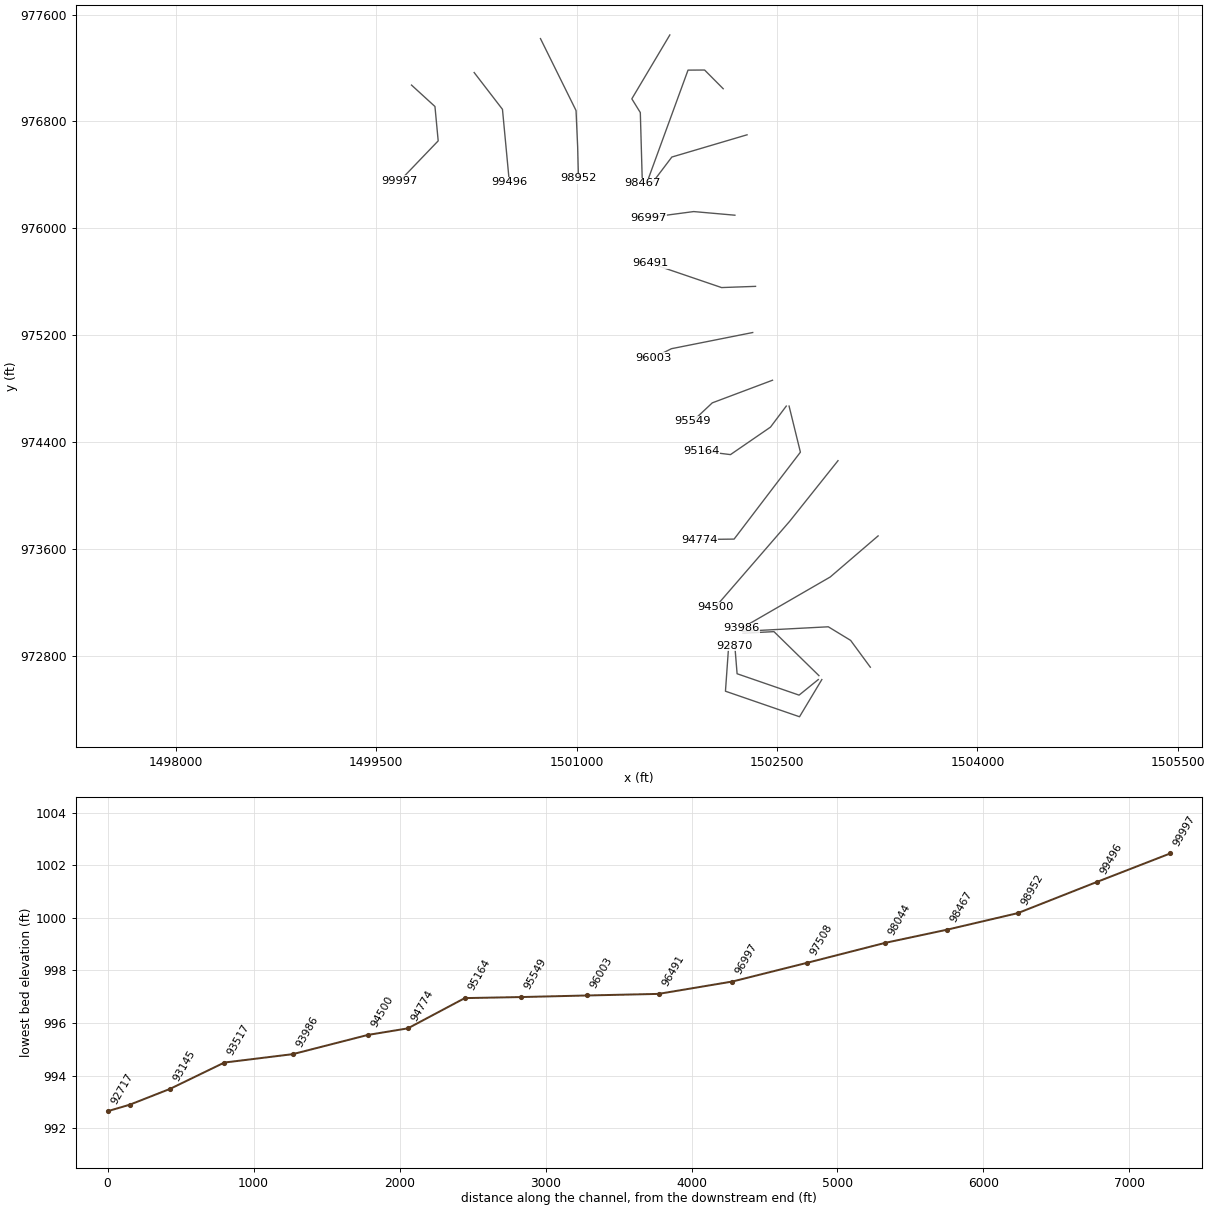
HEC-RAS study Fisher River.prj: Fisher River Limited Detail Study

--- Fisher River.g01 (geometry) --- (continued)

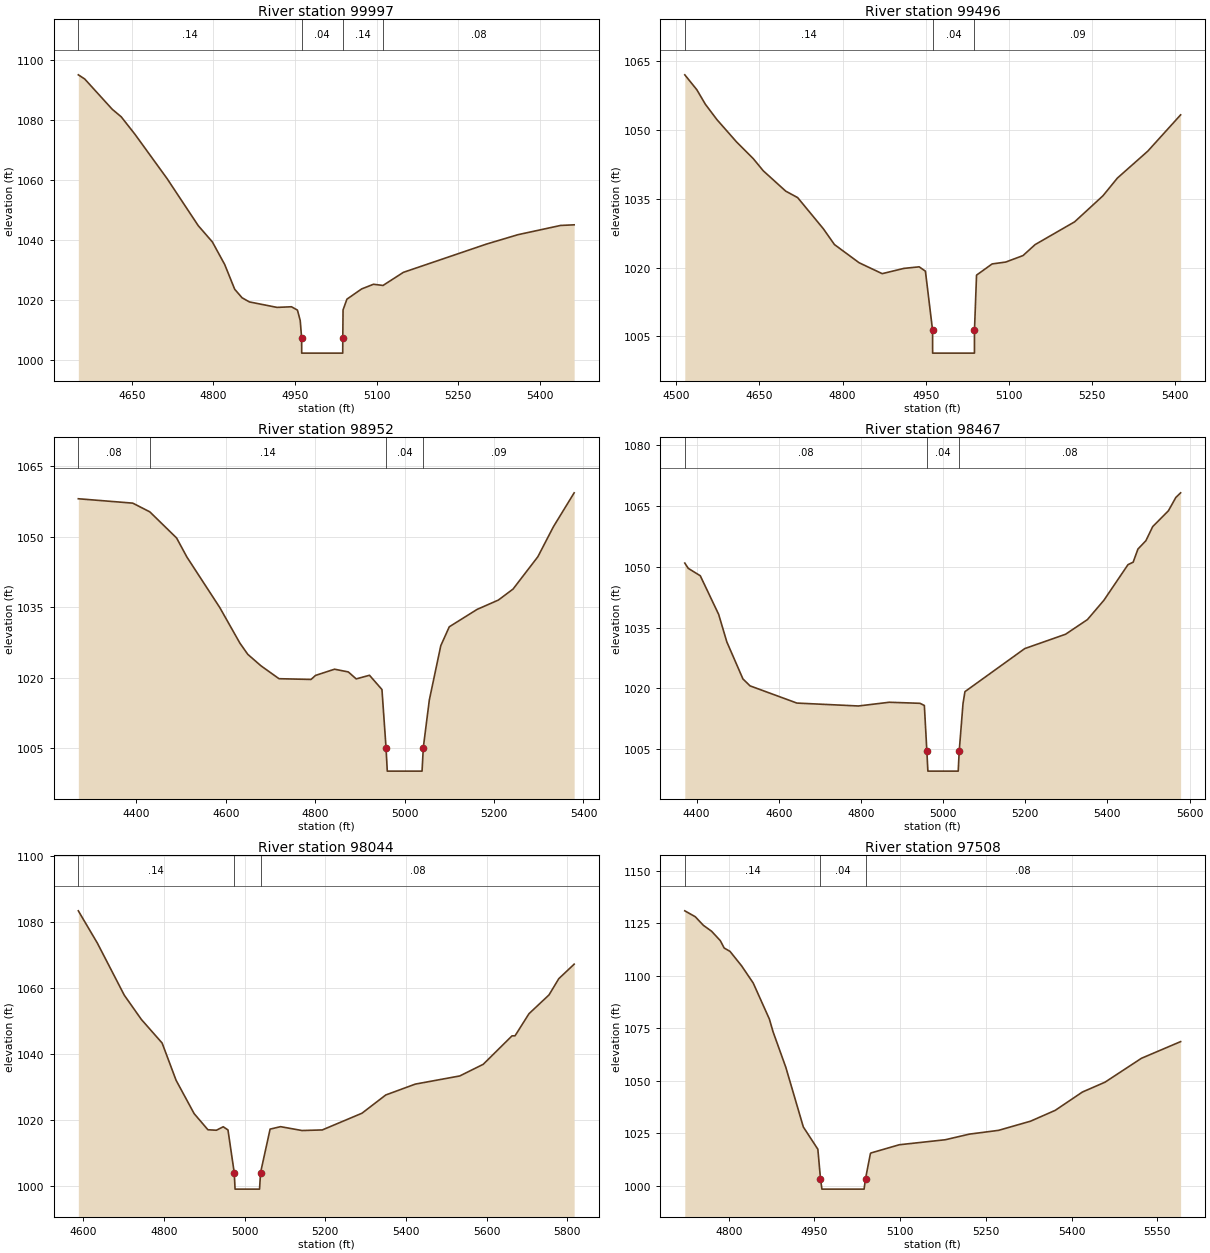
Type RM Length L Ch R = 1,99997,501,501,501
BEGIN DESCRIPTION:
Fisher River 200.0
END DESCRIPTION:
XS GIS Cut Line= 4
      1499764.95       977072.09      1499940.38       976911.78
      1499964.59       976654.63      1499677.20       976355.15
#Sta/Elev= 30
  4551.9 1095.07  4563.6 1093.69  4614.3 1083.59  4630.7 1081.10  4656.0 1075.27
  4714.9 1060.55  4772.2 1044.88  4798.2 1039.45  4820.8 1031.96  4839.2 1023.71
  4852.8 1020.86  4866.1 1019.50  4916.9 1017.67  4943.5 1017.88  4954.5 1016.76
  4959.6 1013.28  4962.2 1007.45  4962.3 1002.45  5037.7 1002.45  5037.8 1007.45
  5038.3 1016.84  5045.4 1020.41  5072.4 1023.81  5094.2 1025.37  5111.7 1024.97
  5149.2 1029.34  5301.6 1038.73  5359.7 1041.87  5437.9 1044.94  5462.9 1045.15
#Mann=4,-1,0
  4551.9    0.14       0  4962.2    0.04       0  5037.8    0.14       0
  5111.7    0.08       0
Bank Sta=4962.2,5037.8
XS Rating Curve= 0
Exp/Cntr=0.3,0.1

Type RM Length L Ch R = 1,99496,544,544,544
BEGIN DESCRIPTION:
Fisher River 199.0
END DESCRIPTION:
XS GIS Cut Line= 3
      1500233.85       977165.89      1500445.61       976890.61
      1500497.04       976346.04
#Sta/Elev= 30
  4515.3 1062.06  4537.0 1058.81  4552.4 1055.64  4573.2 1052.30  4608.4 1047.46
  4638.6 1043.81  4656.9 1041.12  4697.4 1036.69  4718.9 1035.28  4765.2 1028.49
  4785.2 1025.05  4829.7 1021.08  4871.3 1018.70  4910.6 1019.85  4938.0 1020.19
  4949.3 1019.24  4962.2 1006.37  4962.3 1001.37  5037.7 1001.37  5037.8 1006.37
  5041.5 1018.38  5069.6 1020.82  5094.1 1021.23  5125.3 1022.64  5147.2 1025.04
  5218.5 1030.01  5269.5 1035.68  5295.6 1039.55  5350.4 1045.42  5409.6 1053.33
#Mann=3,-1,0
  4515.3    0.14       0  4962.2    0.04       0  5037.8    0.09       0
Bank Sta=4962.2,5037.8
XS Rating Curve= 0
Exp/Cntr=0.3,0.1

Type RM Length L Ch R = 1,98952,485,485,485
BEGIN DESCRIPTION:
Fisher River 198.0
END DESCRIPTION:
XS GIS Cut Line= 4
      1500730.00       977420.01      1500996.21       976881.53
      1501008.32       976609.25      1501014.37       976373.26
#Sta/Elev= 30
  4269.9 1058.06  4391.6 1057.13  4429.8 1055.28  4489.7 1049.73  4512.9 1045.66
  4586.5 1034.92  4631.2 1027.41  4649.0 1025.00  4678.4 1022.57  4718.9 1019.82
  4790.5 1019.66  4800.6 1020.52  4843.1 1021.84  4873.9 1021.26  4891.6 1019.78
  4921.3 1020.55  4949.2 1017.52  4958.3 1005.18  4961.1 1000.18  5038.9 1000.18
  5041.7 1005.18  5055.2 1015.31  5080.8 1026.83  5099.8 1030.85  5162.1 1034.55
  5209.6 1036.53  5242.5 1038.87  5298.0 1045.74  5332.7 1052.10  5379.2 1059.32
#Mann=4,-1,0
  4269.9    0.08       0  4429.8    0.14       0  4958.3    0.04       0
  5041.7    0.09       0
Bank Sta=4958.3,5041.7
XS Rating Curve= 0
Exp/Cntr=0.3,0.1

Type RM Length L Ch R = 1,98467,423,423,423
BEGIN DESCRIPTION:
Fisher River 197.0
END DESCRIPTION:
XS GIS Cut Line= 4
      1501698.08       977447.25      1501413.71       976969.26
      1501477.24       976866.40      1501492.36       976337.00
#Sta/Elev= 30
  4371.5 1050.94  4379.9 1049.64  4409.2 1047.80  4453.9 1038.27  4473.8 1031.47
  4513.0 1022.32  4530.3 1020.61  4644.3 1016.36  4794.0 1015.64  4869.2 1016.56
  4943.9 1016.30  4954.5 1015.76  4960.6 1004.55  4963.1  999.55  5036.9  999.55
  5039.4 1004.55  5048.6 1016.24  5053.3 1019.18  5198.9 1029.82  5298.2 1033.36
  5351.4 1036.98  5391.4 1041.74  5450.1 1050.55  5462.7 1051.16  5474.3 1054.40
  5493.7 1056.46  5510.2 1059.94  5548.5 1063.86  5566.5 1067.14  5578.2 1068.29
#Mann=3,-1,0
  4371.5    0.08       0  4960.6    0.04       0  5039.4    0.08       0
Bank Sta=4960.6,5039.4
XS Rating Curve= 0
Exp/Cntr=0.3,0.1

Type RM Length L Ch R = 1,98044,536,536,536
BEGIN DESCRIPTION:
Fisher River 196.0
END DESCRIPTION:
XS GIS Cut Line= 4
      1502097.42       977044.90      1501958.29       977184.79
      1501834.22       977184.06      1501522.63       976330.95
#Sta/Elev= 30
  4587.5 1083.35  4634.9 1073.53  4701.4 1057.81  4743.7 1050.47  4795.3 1043.30
  4829.9 1032.03  4874.7 1021.92  4908.9 1017.03  4930.0 1016.89  4946.8 1017.94
  4958.6 1016.98  4974.1 1004.05  4976.2  999.05  5036.9  999.05  5039.4 1004.05
  5063.1 1017.23  5089.0 1017.97  5142.3 1016.80  5192.5 1016.98  5290.9 1022.04
  5349.9 1027.57  5423.1 1030.86  5533.4 1033.33  5591.6 1036.86  5663.0 1045.48
  5670.4 1045.48  5705.1 1052.19  5754.7 1057.87  5779.0 1062.80  5817.1 1067.19
#Mann=3,-1,0
  4587.5    0.14       0  4974.1    0.04       0  5039.4    0.08       0
Bank Sta=4974.1,5039.4
XS Rating Curve= 0
Exp/Cntr=0.3,0.1

Type RM Length L Ch R = 1,97508,511,511,511
BEGIN DESCRIPTION:
Fisher River 195.0
END DESCRIPTION:
XS GIS Cut Line= 3
      1502275.91       976700.01      1501713.21       976533.62
      1501543.82       976309.78
#Sta/Elev= 30
  4723.2 1130.81  4741.5 1128.00  4755.7 1123.91  4770.1 1121.08  4785.3 1116.62
  4792.1 1113.11  4802.3 1111.50  4822.6 1104.60  4842.9 1096.43  4871.2 1079.26
  4877.6 1073.23  4899.9 1056.34  4930.6 1027.88  4956.0 1017.28  4960.6 1003.29
  4963.1  998.29  5036.9  998.29  5039.4 1003.29  5048.0 1015.26  5049.1 1015.52
  5098.5 1019.42  5178.9 1021.80  5221.1 1024.48  5272.2 1026.28  5328.1 1030.64
  5371.3 1035.80  5418.9 1044.53  5458.4 1049.21  5522.2 1060.60  5590.7 1068.53
#Mann=3,-1,0
  4723.2    0.14       0  4960.6    0.04       0  5039.4    0.08       0
Bank Sta=4960.6,5039.4
XS Rating Curve= 0
Exp/Cntr=0.3,0.1

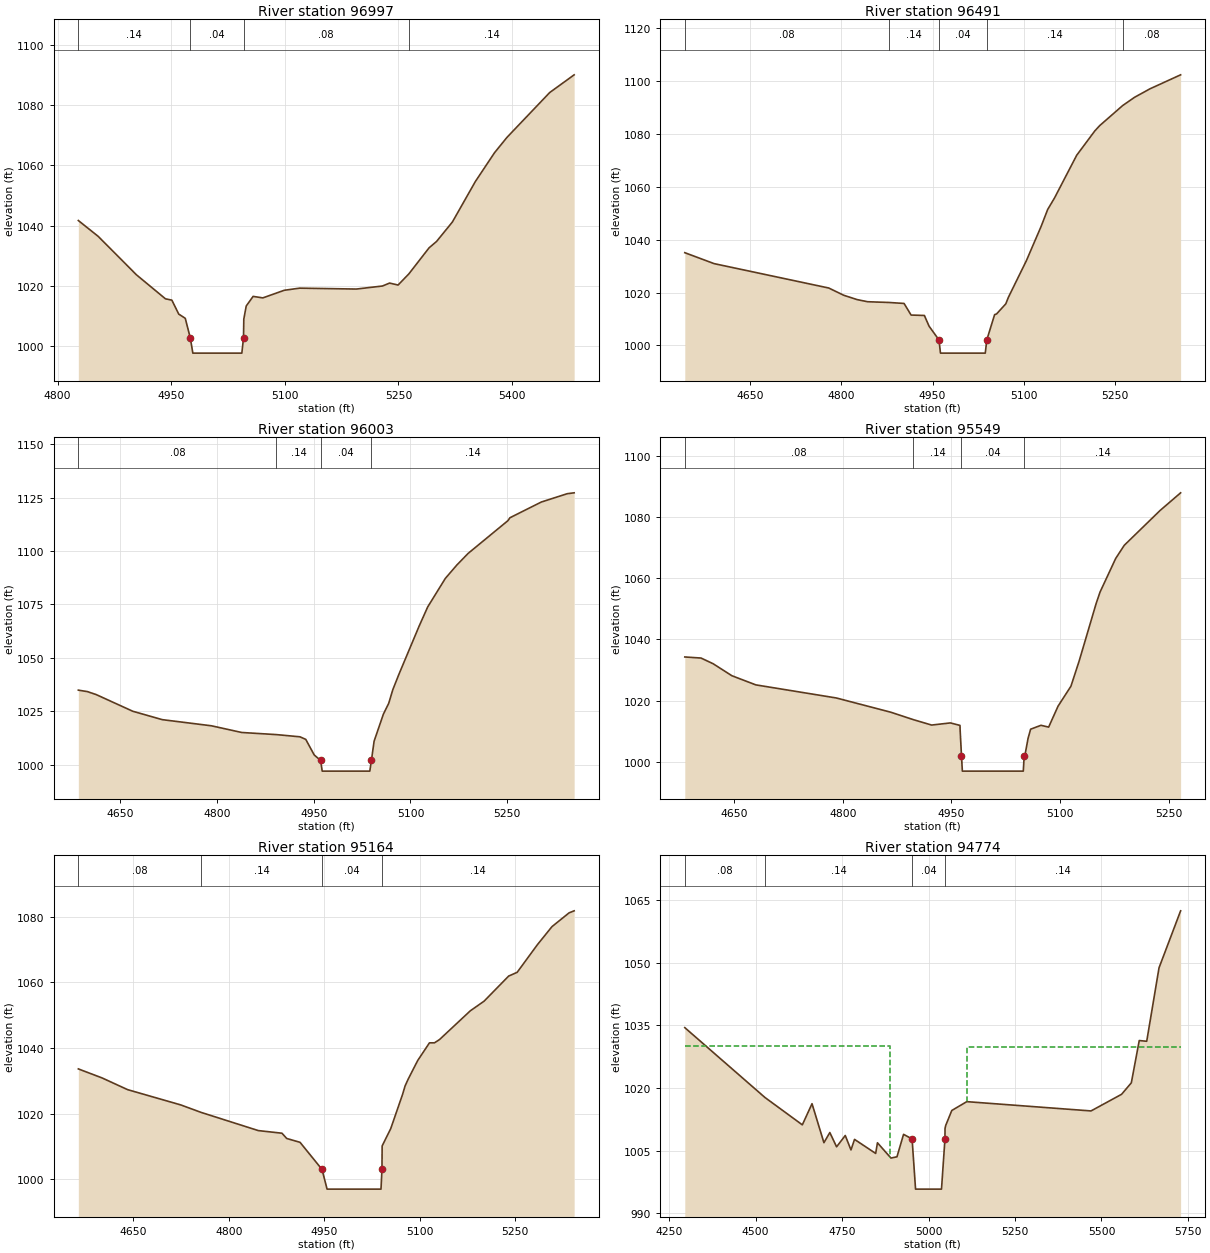
Type RM Length L Ch R = 1,96997,506,506,506
BEGIN DESCRIPTION:
Fisher River 194.0
END DESCRIPTION:
XS GIS Cut Line= 3
      1502185.20       976098.28      1501876.58       976125.51
      1501534.70       976080.12
#Sta/Elev= 30
  4827.4 1041.66  4853.6 1036.40  4904.3 1023.58  4942.4 1015.64  4950.9 1015.19
  4960.0 1010.55  4968.6 1009.15  4975.3 1002.58  4978.6  997.58  5043.3  997.58
  5045.5 1002.58  5045.9 1008.89  5049.1 1013.25  5058.2 1016.44  5071.0 1015.94
  5099.3 1018.47  5119.6 1019.18  5194.5 1018.88  5229.0 1019.89  5238.4 1020.87
  5249.6 1020.21  5263.8 1023.91  5290.5 1032.57  5300.4 1034.70  5321.3 1041.16
  5351.6 1054.60  5377.0 1064.21  5393.5 1069.33  5449.8 1084.20  5482.1 1090.09
#Mann=4,-1,0
  4827.4    0.14       0  4975.3    0.04       0  5045.5    0.08       0
  5263.8    0.14       0
Bank Sta=4975.3,5045.5
XS Rating Curve= 0
Exp/Cntr=0.3,0.1

Type RM Length L Ch R = 1,96491,488,488,488
BEGIN DESCRIPTION:
Fisher River 193.0
END DESCRIPTION:
XS GIS Cut Line= 3
      1502339.41       975565.82      1502085.33       975556.75
      1501552.86       975738.27
#Sta/Elev= 30
  4541.9 1035.10  4590.2 1030.96  4779.0 1021.74  4803.7 1019.00  4825.7 1017.36
  4843.0 1016.55  4878.0 1016.27  4903.1 1015.90  4914.7 1011.51  4936.6 1011.35
  4944.3 1007.30  4960.6 1002.11  4963.1  997.11  5036.9  997.11  5039.4 1002.11
  5052.3 1011.68  5055.4 1011.91  5070.7 1015.75  5075.0 1018.23  5104.6 1032.07
  5129.1 1045.15  5139.7 1051.44  5150.9 1055.77  5187.5 1071.95  5217.3 1081.14
  5225.3 1083.14  5263.2 1090.74  5282.9 1093.88  5308.5 1097.11  5358.7 1102.37
#Mann=5,-1,0
  4541.9    0.08       0  4878.0    0.14       0  4960.6    0.04       0
  5039.4    0.14       0  5263.2    0.08       0
Bank Sta=4960.6,5039.4
XS Rating Curve= 0
Exp/Cntr=0.3,0.1

Type RM Length L Ch R = 1,96003,454,454,454
BEGIN DESCRIPTION:
Fisher River 192.0
END DESCRIPTION:
XS GIS Cut Line= 3
      1502318.29       975220.34      1501710.19       975099.32
      1501577.03       975032.74
#Sta/Elev= 30
  4584.9 1034.92  4598.9 1034.24  4612.4 1032.87  4669.5 1025.03  4715.1 1021.12
  4791.3 1018.25  4838.3 1015.12  4892.1 1014.13  4928.6 1013.10  4937.6 1011.89
  4950.7 1004.61  4960.6 1002.05  4963.1  997.05  5036.9  997.05  5039.4 1002.05
  5043.6 1011.08  5058.0 1023.73  5066.2 1028.72  5072.5 1035.06  5081.7 1042.08
  5113.3 1064.79  5126.7 1073.84  5154.1 1087.20  5172.0 1093.46  5189.4 1098.87
  5251.0 1114.15  5254.2 1115.53  5302.9 1122.89  5343.1 1126.78  5353.8 1127.19
#Mann=4,-1,0
  4584.9    0.08       0  4892.1    0.14       0  4960.6    0.04       0
  5039.4    0.14       0
Bank Sta=4960.6,5039.4
XS Rating Curve= 0
Exp/Cntr=0.3,0.1

Type RM Length L Ch R = 1,95549,385,385,385
BEGIN DESCRIPTION:
Fisher River 191.0
END DESCRIPTION:
XS GIS Cut Line= 3
      1502466.48       974863.34      1502015.74       974693.93
      1501867.47       974554.73
#Sta/Elev= 30
  4581.7 1034.26  4604.1 1033.91  4620.7 1032.07  4646.8 1028.13  4679.8 1025.15
  4791.1 1020.87  4866.3 1016.22  4897.5 1013.79  4922.7 1012.03  4948.6 1012.73
  4961.8 1011.92  4962.0 1010.55  4963.9 1001.99  4965.1  996.99  5049.3  996.99
  5050.5 1001.99  5051.4 1002.00  5055.9 1007.72  5059.4 1010.68  5073.7 1011.95
  5084.3 1011.36  5097.3 1018.20  5115.1 1024.72  5126.6 1033.07  5149.8 1051.63
  5155.2 1055.40  5176.9 1066.42  5188.8 1070.73  5238.3 1082.10  5266.6 1087.85
#Mann=4,-1,0
  4581.7    0.08       0  4897.5    0.14       0  4963.9    0.04       0
  5050.5    0.14       0
Bank Sta=4963.9,5050.5
XS Rating Curve= 0
Exp/Cntr=0.3,0.1

Type RM Length L Ch R = 1,95164,390,390,390
BEGIN DESCRIPTION:
Fisher River 190.0
END DESCRIPTION:
XS GIS Cut Line= 4
      1502569.40       974669.76      1502451.39       974512.41
      1502151.88       974306.69      1501934.01       974333.93
#Sta/Elev= 30
  4563.4 1033.63  4600.8 1030.87  4640.9 1027.30  4724.5 1022.64  4756.3 1020.37
  4846.4 1014.81  4883.6 1014.01  4891.0 1012.41  4912.0 1011.23  4946.6 1002.95
  4954.5  996.95  5039.3  996.95  5040.8 1002.95  5041.1 1010.13  5054.6 1015.41
  5073.1 1025.79  5077.2 1028.45  5082.1 1030.53  5097.0 1036.19  5115.5 1041.58
  5123.4 1041.59  5131.3 1042.58  5179.7 1051.35  5201.4 1054.30  5240.0 1061.95
  5253.4 1063.10  5285.3 1071.55  5308.1 1077.03  5335.0 1081.24  5343.0 1081.86
#Mann=4,-1,0
  4563.4    0.08       0  4756.3    0.14       0  4946.6    0.04       0
  5040.8    0.14       0
Bank Sta=4946.6,5040.8
XS Rating Curve= 0
Exp/Cntr=0.5,0.3

Type RM Length L Ch R = 1,94774,274,274,274
BEGIN DESCRIPTION:
Highway 601 - US
END DESCRIPTION:
XS GIS Cut Line= 5
      1502590.55       974669.72      1502675.26       974324.84
      1502474.37       974062.44      1502179.11       973674.40
      1501918.93       973671.38
#Sta/Elev= 30
  4295.4 1034.44  4527.1 1017.73  4635.2 1011.18  4663.2 1016.24  4697.6 1006.91
  4714.7 1009.34  4734.2 1005.92  4759.3 1008.63  4775.8 1005.18  4786.1 1007.70
  4847.2 1004.34  4852.4 1006.89  4891.4 1003.23  4908.8 1003.54  4927.8 1008.91
  4952.5 1007.80  4962.5  995.80  5037.5  995.80  5047.5 1007.80  5047.7 1010.31
  5049.6 1011.02  5067.3 1014.62  5110.6 1016.73  5469.8 1014.51  5558.1 1018.49
  5586.3 1021.24  5609.2 1031.35  5630.8 1031.18  5666.4 1048.76  5728.8 1062.39
#Mann=4,-1,0
  4295.4    0.08       0  4527.1    0.14       0  4952.5    0.04       0
  5047.5    0.14       0
#XS Ineff=2,0
    0.00 4890.00 1030.00 5110.00    0.00 1029.70
Permanent Ineff=
       F       F
Bank Sta=4952.5,5047.5
XS Rating Curve= 0
Exp/Cntr=0.5,0.3

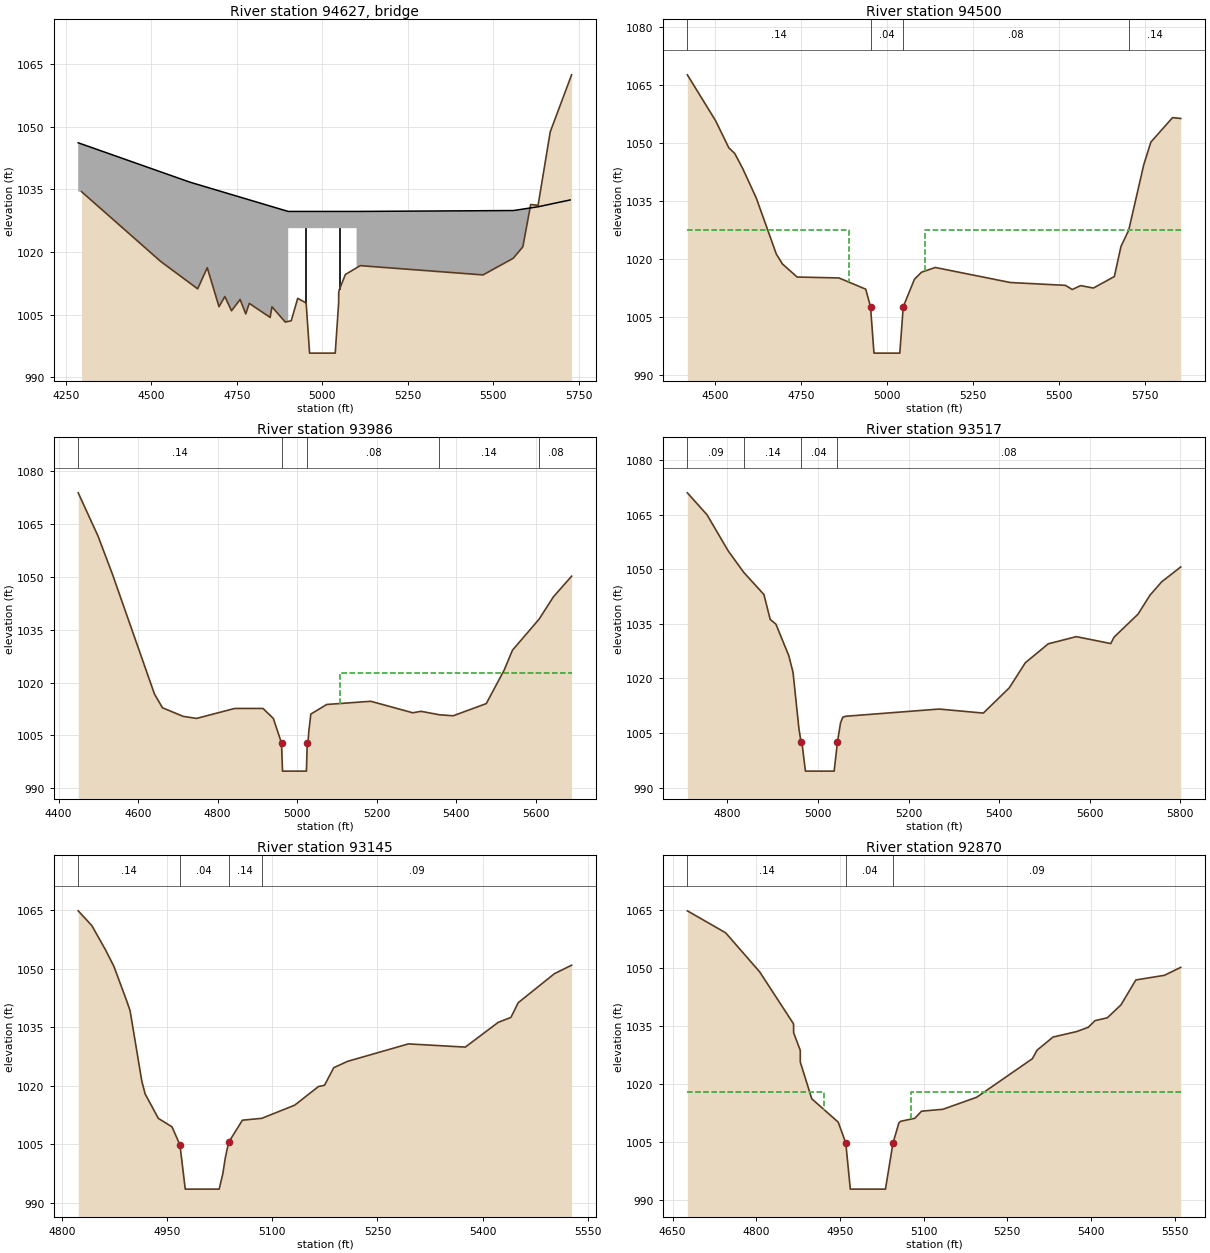
Type RM Length L Ch R =3,94627,,,
BEGIN DESCRIPTION:
Highway 601 - TOR
Structure ID: LDS_FR_08
Approximate Survey Structure
END DESCRIPTION:
Bridge Culvert--1,0,-1,-1,0
Deck Dist Width WeirC Skew NumUp NumDn MinLoCord MaxHiCord MaxSubmerge Is_Ogee
124.5,45,3,,9,9,,,0.95,0,1,1,,,
  4285.8  4611.7  4900.0  4900.0  5100.0  5100.0  5559.2  5631.3  5724.5
 1046.13 1036.73 1029.70 1029.70 1029.70 1029.70 1029.92 1030.83 1032.45
  975.80  975.80  975.80 1025.70 1025.70  975.80  975.80  975.80  975.80
  4285.8  4611.7  4900.0  4900.0  5100.0  5100.0  5559.2  5631.3  5724.5
 1046.13 1036.73 1029.70 1029.70 1029.70 1029.70 1029.92 1030.83 1032.45
  975.80  975.80  975.80 1025.70 1025.70  975.80  975.80  975.80  975.80
Pier Skew, UpSta & Num, DnSta & Num=,4950,2,4950,2,0,0,0,0,0
       3       3
 1009.90 1025.70
       3       3
 1016.42 1025.70
Pier Skew, UpSta & Num, DnSta & Num=,5050,2,5050,2,0,0,0,0,0
       3       3
 1011.15 1025.70
       3       3
 1016.80 1025.70
Abutment Skew #Up #Dn=,2,2
  4900.0  4931.0
 1025.70 1007.70
  4900.0  4931.0
 1025.70 1012.34
Abutment Skew #Up #Dn=,2,2
  5069.0  5100.0
 1014.70 1025.70
  5069.0  5100.0
 1012.15 1025.70
BR Coef=1,1,0,1.25,0,,,0.8,0,2,0,
WSPro=,,,, 1 ,,,, 0 ,,,, 0 ,,,,-1 ,-1 ,-1 , 0 , 0 , 0 , 0 , 0
BC Design=,,0,,0,,,,,,

Type RM Length L Ch R = 1,94500,514,514,514
BEGIN DESCRIPTION:
Highway 601 - DS
END DESCRIPTION:
XS GIS Cut Line= 3
      1502956.62       974261.32      1502595.38       973808.31
      1502036.93       973163.14
#Sta/Elev= 30
  4420.6 1067.52  4502.4 1055.69  4540.9 1048.66  4558.2 1047.18  4581.3 1043.30
  4620.8 1035.64  4679.0 1021.16  4696.9 1018.58  4739.5 1015.23  4860.9 1014.99
  4938.5 1012.09  4952.5 1007.55  4962.5  995.55  5037.5  995.55  5047.5 1007.55
  5080.0 1014.65  5100.4 1016.47  5140.5 1017.70  5358.6 1013.81  5518.4 1013.08
  5538.2 1012.00  5562.6 1013.01  5599.6 1012.38  5660.5 1015.35  5679.7 1023.13
  5702.2 1027.33  5745.9 1044.27  5766.7 1050.15  5829.5 1056.45  5853.3 1056.24
#Mann=4,-1,0
  4420.6    0.14       0  4952.5    0.04       0  5047.5    0.08       0
  5702.2    0.14       0
#XS Ineff=2,0
    0.00 4890.00 1027.50 5110.00    0.00 1027.50
Permanent Ineff=
       F       F
Bank Sta=4952.5,5047.5
XS Rating Curve= 0
Exp/Cntr=0.5,0.3

Type RM Length L Ch R = 1,93986,469,469,469
BEGIN DESCRIPTION:
Fisher River 188.0
END DESCRIPTION:
XS GIS Cut Line= 3
      1503256.74       973698.32      1502898.53       973390.93
      1502232.98       973006.13
#Sta/Elev= 30
  4449.3 1073.91  4499.1 1061.63  4535.3 1050.81  4641.0 1016.75  4661.2 1012.82
  4713.3 1010.38  4746.9 1009.80  4842.8 1012.63  4914.0 1012.63  4940.0 1009.80
  4960.6 1002.82  4963.1  994.82  5023.2  994.82  5025.3 1002.82  5027.2 1001.82
  5027.5 1003.40  5029.1 1005.92  5034.3 1011.03  5074.3 1013.76  5185.0 1014.67
  5290.8 1011.40  5311.5 1011.82  5357.7 1010.83  5392.3 1010.55  5475.5 1014.01
  5520.5 1023.52  5541.3 1029.17  5608.5 1038.03  5644.2 1044.33  5690.1 1050.22
#Mann=5,-1,0
  4449.3    0.14       0  4960.6    0.04       0  5025.3    0.08       0
  5357.7    0.14       0  5608.5    0.08       0
#XS Ineff=2,0
       0                 5107.70    0.00 1022.78
Permanent Ineff=
       F       F
Bank Sta=4960.6,5025.3
XS Rating Curve= 0
Exp/Cntr=0.3,0.1

Type RM Length L Ch R = 1,93517,372,372,372
BEGIN DESCRIPTION:
Fisher River 187.0
END DESCRIPTION:
XS GIS Cut Line= 4
      1503198.61       972715.72      1503051.00       972916.56
      1502884.01       973018.21      1502240.25       972984.33
#Sta/Elev= 30
  4711.4 1070.99  4754.7 1064.98  4801.5 1055.05  4836.0 1049.11  4880.4 1043.05
  4894.4 1036.18  4906.9 1034.91  4935.4 1026.22  4944.7 1021.66  4957.8 1006.10
  4962.5 1002.48  4965.1 1001.58  4972.1  994.50  5035.5  994.50  5042.8 1002.50
  5049.6 1007.75  5054.6 1009.34  5061.9 1009.59  5267.0 1011.56  5364.9 1010.45
  5422.2 1017.39  5457.6 1024.28  5508.2 1029.49  5570.2 1031.46  5646.3 1029.56
  5653.6 1031.33  5706.5 1037.65  5732.9 1042.86  5758.7 1046.53  5800.8 1050.62
#Mann=4,-1,0
  4711.4    0.09       0  4836.0    0.14       0  4962.5    0.04       0
  5042.8    0.08       0
Bank Sta=4962.5,5042.8
XS Rating Curve= 0
Exp/Cntr=0.3,0.1

Type RM Length L Ch R = 1,93145,275,275,275
BEGIN DESCRIPTION:
Fisher River 186.0
END DESCRIPTION:
XS GIS Cut Line= 4
      1502813.82       972652.76      1502700.07       972764.09
      1502477.40       972981.91      1502245.07       972969.81
#Sta/Elev= 30
  4823.5 1064.90  4842.9 1061.12  4862.6 1054.83  4874.5 1050.60  4893.4 1041.42
  4897.5 1039.23  4914.1 1021.26  4918.9 1017.92  4937.8 1011.64  4957.2 1009.48
  4968.5 1004.86  4976.1  993.50  5024.4  993.50  5029.7  997.50  5033.1 1001.46
  5037.9 1005.51  5057.6 1011.19  5085.3 1011.67  5132.2 1015.05  5166.0 1019.83
  5174.6 1020.14  5187.7 1024.65  5207.4 1026.28  5294.2 1030.76  5375.3 1029.94
  5422.3 1036.30  5440.3 1037.55  5450.7 1041.33  5502.3 1048.77  5526.8 1050.95
#Mann=4,-1,0
  4823.5    0.14       0  4968.5    0.04       0  5037.9    0.14       0
  5085.3    0.09       0
Bank Sta=4968.5,5037.9
XS Rating Curve= 0
Exp/Cntr=0.5,0.3

Type RM Length L Ch R = 1,92870,153,153,153
BEGIN DESCRIPTION:
Old Highway-601 - US
END DESCRIPTION:
XS GIS Cut Line= 4
      1502808.94       972623.20      1502665.34       972506.78
      1502201.50       972666.79      1502184.55       972874.97
#Sta/Elev= 30
  4676.4 1064.88  4745.1 1059.19  4806.0 1049.10  4866.8 1035.63  4866.9 1033.35
  4878.8 1028.79  4878.9 1025.74  4899.4 1016.27  4946.8 1010.23  4960.4 1004.80
  4968.5  992.90  5031.5  992.90  5045.0 1004.80  5055.5 1010.01  5058.6 1010.44
  5084.1 1011.22  5096.2 1013.06  5134.5 1013.55  5195.0 1016.66  5294.9 1026.64
  5303.3 1028.85  5332.0 1032.24  5373.9 1033.64  5395.1 1034.76  5407.1 1036.48
  5429.1 1037.21  5453.6 1040.54  5480.3 1047.00  5531.5 1048.20  5560.8 1050.26
#Mann=3,-1,0
  4676.4    0.14       0  4960.4    0.04       0  5045.0    0.09       0
#XS Ineff=2,0
    0.00 4922.00 1018.10 5077.00    0.00 1018.10
Permanent Ineff=
       F       F
Bank Sta=4960.4,5045
XS Rating Curve= 0
Exp/Cntr=0.5,0.3

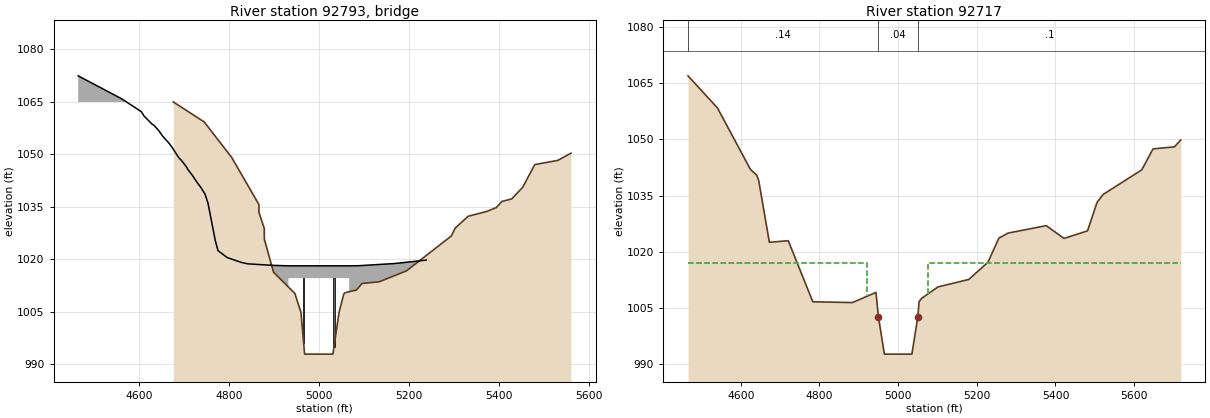
Type RM Length L Ch R =3,92793,,,
BEGIN DESCRIPTION:
Old Highway-601 - TOR
Structure ID: LDS_FR_07
Approximate Survey Structure
END DESCRIPTION:
Bridge Culvert--1,0,-1,-1,0
Deck Dist Width WeirC Skew NumUp NumDn MinLoCord MaxHiCord MaxSubmerge Is_Ogee
61,32,3,,39,39,,,0.95,0,1,1,,,
  4464.9  4562.6  4578.9  4605.4  4611.1  4611.4  4629.6  4632.6  4643.8  4653.3
  4667.1  4667.6  4671.1  4673.6  4674.4  4688.4  4692.4  4694.3  4705.9  4708.7
  4718.1  4729.4  4737.2  4746.7  4753.4  4769.8  4775.9  4796.3  4827.8  4841.7
  4893.1  4896.4  4932.5  4932.5  5067.5  5067.5  5089.0  5170.7  5238.8
 1072.34 1065.72 1064.32 1062.11 1060.92 1060.87 1058.50 1058.33 1056.75 1055.04
 1053.07 1052.99 1052.38 1051.93 1051.79 1049.01 1048.44 1048.26 1046.29 1045.63
 1044.07 1041.90 1040.57 1038.66 1036.11 1025.34 1022.43 1020.46 1019.08 1018.67
 1018.28 1018.25 1018.10 1018.10 1018.10 1018.10 1018.14 1018.78 1019.74
  972.90  972.90  972.90  972.90  972.90  972.90  972.90  972.90  972.90  972.90
  972.90  972.90  972.90  972.90  972.90  972.90  972.90  972.90  972.90  972.90
  972.90  972.90  972.90  972.90  972.90  972.90  972.90  972.90  972.90  972.90
  972.90  972.90  972.90 1014.60 1014.60  972.90  972.90  972.90  972.90
  4464.9  4562.6  4578.9  4605.4  4611.1  4611.4  4629.6  4632.6  4643.8  4653.3
  4667.1  4667.6  4671.1  4673.6  4674.4  4688.4  4692.4  4694.3  4705.9  4708.7
  4718.1  4729.4  4737.2  4746.7  4753.4  4769.8  4775.9  4796.3  4827.8  4841.7
  4893.1  4896.4  4932.5  4932.5  5067.5  5067.5  5089.0  5170.7  5238.8
 1072.34 1065.72 1064.32 1062.11 1060.92 1060.87 1058.50 1058.33 1056.75 1055.04
 1053.07 1052.99 1052.38 1051.93 1051.79 1049.01 1048.44 1048.26 1046.29 1045.63
 1044.07 1041.90 1040.57 1038.66 1036.11 1025.34 1022.43 1020.46 1019.08 1018.67
 1018.28 1018.25 1018.10 1018.10 1018.10 1018.10 1018.14 1018.78 1019.74
  972.90  972.90  972.90  972.90  972.90  972.90  972.90  972.90  972.90  972.90
  972.90  972.90  972.90  972.90  972.90  972.90  972.90  972.90  972.90  972.90
  972.90  972.90  972.90  972.90  972.90  972.90  972.90  972.90  972.90  972.90
  972.90  972.90  972.90 1014.60 1014.60  972.90  972.90  972.90  972.90
Pier Skew, UpSta & Num, DnSta & Num=,4966.3,2,4966.3,2,0,0,0,0,0
       3       3
  993.90 1015.60
       3       3
  993.65 1015.60
Pier Skew, UpSta & Num, DnSta & Num=,5033.8,2,5033.8,2,0,0,0,0,0
       3       3
  993.90 1015.60
       3       3
  993.65 1015.60
BR Coef=1,1,0,1.25,0,,,0.8,0,2,0,
WSPro=,,,, 1 ,,,, 0 ,,,, 0 ,,,,-1 ,-1 ,-1 , 0 , 0 , 0 , 0 , 0
BC Design=,,0,,0,,,,,,

Type RM Length L Ch R = 1,92717,242,242,242
BEGIN DESCRIPTION:
Old Highway-601 - DS
END DESCRIPTION:
XS GIS Cut Line= 4
      1502835.59       972623.21      1502668.60       972344.90
      1502114.37       972536.10      1502138.57       972877.40
#Sta/Elev= 30
  4465.7 1067.01  4540.6 1058.42  4624.4 1042.01  4640.5 1040.46  4645.5 1039.02
  4672.6 1022.53  4720.6 1022.96  4783.1 1006.63  4883.9 1006.43  4943.6 1009.14
  4950.0 1002.55  4965.0  992.65  5035.0  992.65  5050.0 1002.55  5053.3 1006.69
  5060.0 1007.58  5101.2 1010.60  5179.7 1012.61  5228.3 1017.19  5256.2 1023.65
  5279.6 1024.99  5376.5 1026.98  5421.7 1023.57  5481.5 1025.58  5505.8 1033.18
  5520.9 1035.29  5619.6 1041.89  5648.1 1047.49  5702.6 1048.03  5718.7 1049.88
#Mann=3,-1,0
  4465.7    0.14       0  4950.0    0.04       0  5050.0     0.1       0
#XS Ineff=2,0
    0.00 4922.00 1017.00 5077.00    0.00 1017.00
Permanent Ineff=
       F       F
Bank Sta=4950,5050
XS Rating Curve= 0
Exp/Cntr=0.5,0.3