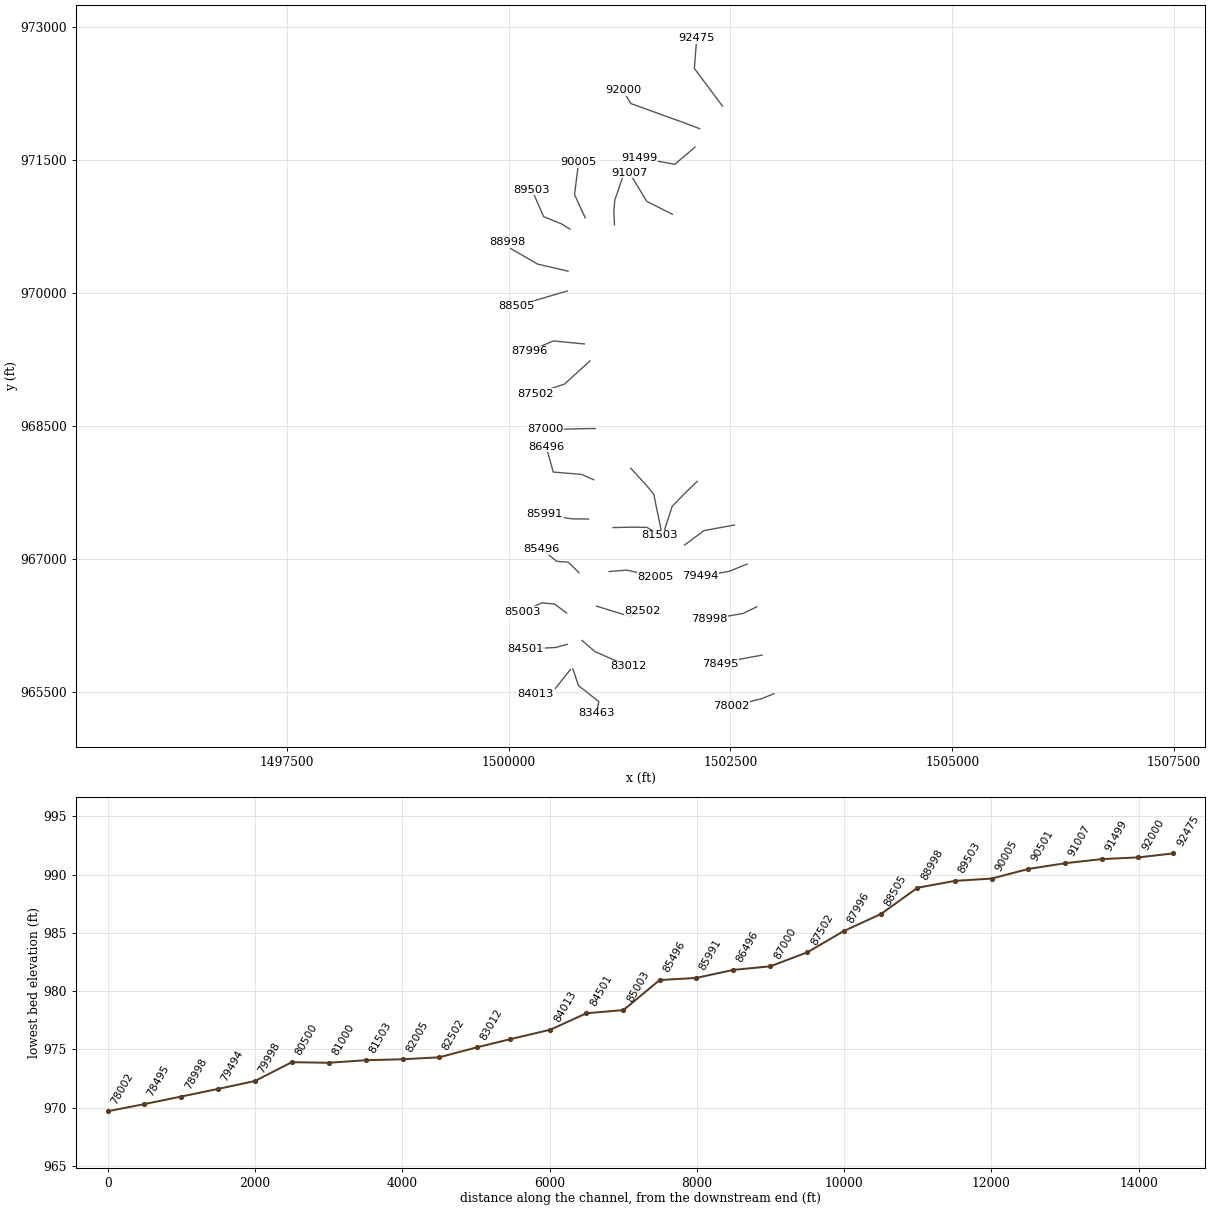
HEC-RAS study Fisher River.prj: Fisher River Limited Detail Study

--- Fisher River.g01 (geometry) --- (continued)

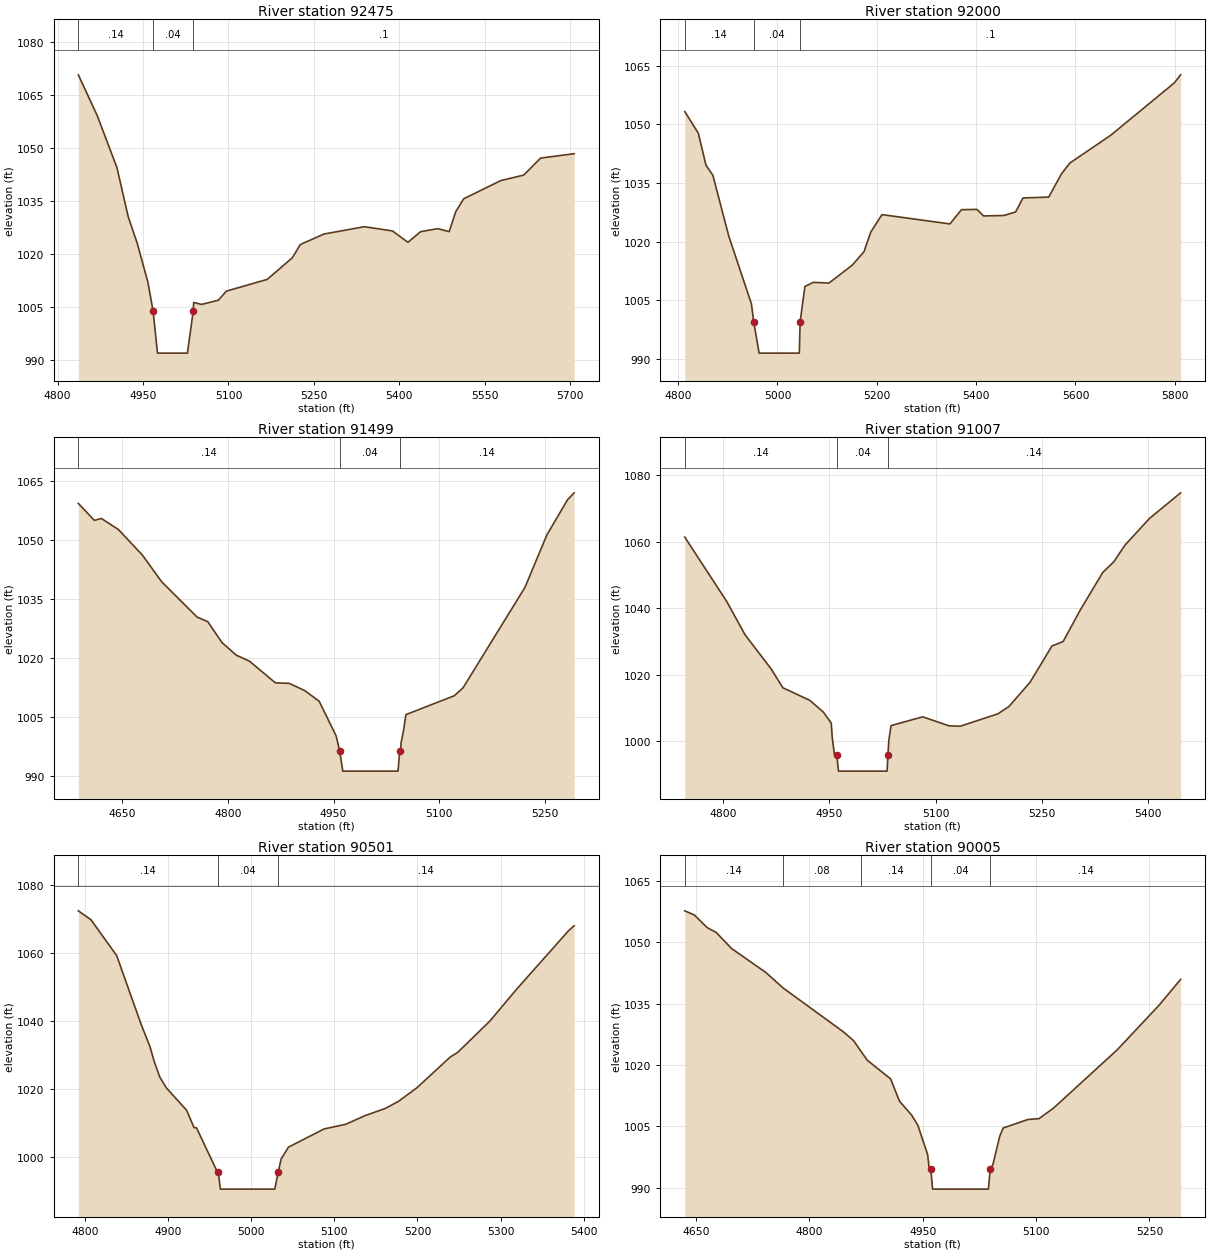
Type RM Length L Ch R = 1,92475,475,475,475
BEGIN DESCRIPTION:
Fisher River 185.0
END DESCRIPTION:
XS GIS Cut Line= 3
      1502409.62       972107.75      1502092.59       972533.68
      1502119.20       972872.47
#Sta/Elev= 30
  4836.3 1070.59  4869.5 1059.05  4904.1 1044.34  4923.9 1030.43  4939.7 1022.95
  4958.5 1011.89  4967.7 1003.64  4975.3  991.83  5027.9  991.83  5038.0 1003.64
  5038.9 1006.18  5052.5 1005.61  5082.1 1006.80  5096.4 1009.38  5168.1 1012.70
  5212.2 1018.83  5226.2 1022.57  5267.9 1025.54  5338.8 1027.61  5388.0 1026.41
  5415.2 1023.19  5437.4 1026.20  5467.6 1027.06  5487.6 1026.21  5499.2 1031.88
  5513.1 1035.51  5578.1 1040.65  5618.4 1042.21  5648.3 1047.04  5707.1 1048.26
#Mann=3,-1,0
  4836.3    0.14       0  4967.7    0.04       0  5038.0     0.1       0
Bank Sta=4967.7,5038
XS Rating Curve= 0
Exp/Cntr=0.3,0.1

Type RM Length L Ch R = 1,92000,501,501,501
BEGIN DESCRIPTION:
Fisher River 184.0
END DESCRIPTION:
XS GIS Cut Line= 4
      1502153.14       971853.58      1501978.57       971919.22
      1501376.46       972136.93      1501289.06       972284.41
#Sta/Elev= 30
  4813.5 1053.26  4840.8 1047.71  4856.1 1039.57  4870.0 1036.98  4902.1 1021.39
  4947.6 1004.11  4952.3  999.49  4963.1  991.49  5044.0  991.49  5045.7  999.49
  5055.3 1008.53  5072.4 1009.59  5103.7 1009.41  5150.6 1013.98  5174.2 1017.41
  5187.8 1022.41  5210.4 1026.91  5347.3 1024.53  5370.4 1028.17  5401.6 1028.25
  5415.0 1026.57  5455.9 1026.69  5479.5 1027.59  5494.3 1031.17  5546.2 1031.40
  5571.9 1037.35  5588.5 1040.08  5671.0 1047.21  5798.8 1060.57  5811.7 1062.66
#Mann=3,-1,0
  4813.5    0.14       0  4952.3    0.04       0  5045.7     0.1       0
Bank Sta=4952.3,5045.7
XS Rating Curve= 0
Exp/Cntr=0.3,0.1

Type RM Length L Ch R = 1,91499,492,492,492
BEGIN DESCRIPTION:
Fisher River 183.0
END DESCRIPTION:
XS GIS Cut Line= 3
      1502099.84       971645.21      1501872.34       971451.59
      1501473.03       971524.19
#Sta/Elev= 30
  4587.3 1059.28  4610.1 1054.97  4620.1 1055.45  4644.0 1052.69  4678.0 1046.24
  4705.6 1039.42  4756.1 1030.42  4771.2 1029.28  4791.4 1023.97  4811.8 1020.76
  4830.5 1019.25  4867.2 1013.76  4887.2 1013.60  4908.8 1011.80  4929.5 1009.09
  4953.6 1000.31  4958.8  996.34  4963.1  991.34  5041.6  991.34  5044.0  996.34
  5045.1  996.34  5046.0  998.57  5049.3 1001.53  5052.8 1005.68  5121.6 1010.47
  5134.1 1012.50  5222.0 1037.97  5253.0 1051.23  5282.5 1060.21  5291.9 1061.96
#Mann=3,-1,0
  4587.3    0.14       0  4958.8    0.04       0  5044.0    0.14       0
Bank Sta=4958.8,5044
XS Rating Curve= 0
Exp/Cntr=0.3,0.1

Type RM Length L Ch R = 1,91007,506,506,506
BEGIN DESCRIPTION:
Fisher River 182.0
END DESCRIPTION:
XS GIS Cut Line= 4
      1501845.68       970887.69      1501660.60       970980.86
      1501555.29       971035.31      1501361.68       971354.76
#Sta/Elev= 30
  4746.3 1061.37  4805.5 1042.01  4831.3 1032.00  4868.1 1021.74  4884.6 1016.07
  4922.8 1012.27  4941.8 1008.73  4952.9 1005.40  4954.2 1001.25  4957.3  996.00
  4960.6  995.99  4963.1  990.99  5031.6  990.99  5032.8  995.99  5034.1 1000.27
  5037.2 1004.68  5081.8 1007.33  5119.0 1004.62  5134.6 1004.49  5187.8 1008.22
  5203.3 1010.39  5233.3 1017.73  5264.1 1028.63  5279.9 1029.97  5304.0 1039.43
  5336.0 1050.83  5351.3 1053.93  5366.9 1058.92  5401.8 1067.03  5445.6 1074.71
#Mann=3,-1,0
  4746.3    0.14       0  4960.6    0.04       0  5032.8    0.14       0
Bank Sta=4960.6,5032.8
XS Rating Curve= 0
Exp/Cntr=0.3,0.1

Type RM Length L Ch R = 1,90501,496,496,496
BEGIN DESCRIPTION:
Fisher River 181.0
END DESCRIPTION:
XS GIS Cut Line= 4
      1501192.25       970769.12      1501184.99       970926.40
      1501197.10       971052.25      1501298.76       971347.56
#Sta/Elev= 30
  4792.3 1072.29  4807.5 1069.67  4838.4 1059.14  4867.9 1038.87  4878.4 1032.41
  4883.8 1027.83  4890.4 1023.35  4898.2 1020.23  4922.5 1013.69  4931.4 1008.57
  4934.4 1008.50  4959.6  995.49  4960.6  995.49  4963.1  990.49  5028.5  990.49
  5032.6  995.49  5036.2  999.39  5045.0 1002.83  5087.8 1008.18  5113.7 1009.54
  5137.4 1012.12  5161.2 1014.18  5177.0 1016.25  5199.6 1020.32  5239.5 1029.32
  5248.3 1030.65  5287.0 1039.85  5319.8 1049.39  5382.0 1066.51  5388.5 1067.91
#Mann=3,-1,0
  4792.3    0.14       0  4960.6    0.04       0  5032.6    0.14       0
Bank Sta=4960.6,5032.6
XS Rating Curve= 0
Exp/Cntr=0.3,0.1

Type RM Length L Ch R = 1,90005,502,502,502
BEGIN DESCRIPTION:
Fisher River 180.0
END DESCRIPTION:
XS GIS Cut Line= 3
      1500863.12       970846.48      1500742.09       971110.34
      1500788.07       971473.35
#Sta/Elev= 30
  4635.1 1057.73  4647.7 1056.71  4664.9 1053.60  4676.6 1052.46  4697.0 1048.51
  4742.2 1042.68  4765.4 1038.84  4845.2 1028.11  4858.6 1025.96  4868.2 1023.39
  4876.8 1021.17  4907.5 1016.63  4919.1 1011.22  4935.3 1007.77  4943.5 1005.31
  4956.5  998.12  4958.6  994.67  4960.6  994.67  4963.1  989.67  5036.9  989.67
  5039.4  994.67  5042.7  995.54  5052.0 1002.66  5056.5 1004.62  5089.4 1006.71
  5103.8 1006.90  5123.0 1009.47  5207.4 1023.74  5262.7 1034.63  5291.3 1040.97
#Mann=5,-1,0
  4635.1    0.14       0  4765.4    0.08       0  4868.2    0.14       0
  4960.6    0.04       0  5039.4    0.14       0
Bank Sta=4960.6,5039.4
XS Rating Curve= 0
Exp/Cntr=0.3,0.1

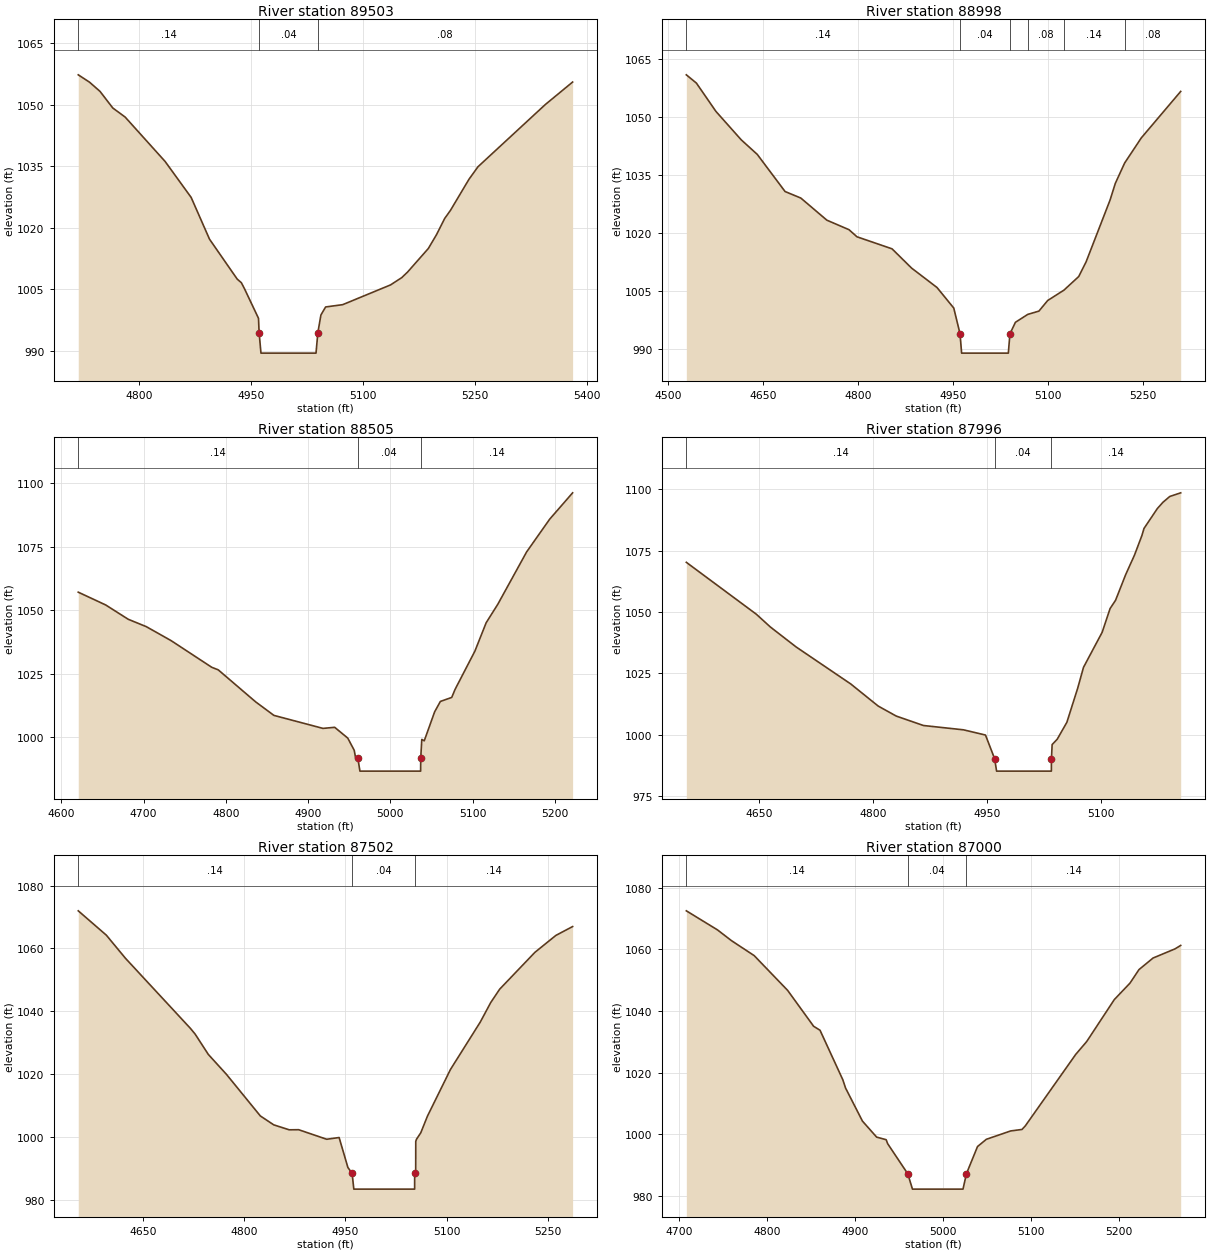
Type RM Length L Ch R = 1,89503,505,505,505
BEGIN DESCRIPTION:
Fisher River 179.0
END DESCRIPTION:
XS GIS Cut Line= 4
      1500691.28       970720.67      1500596.87       970778.76
      1500393.57       970861.05      1500260.46       971166.00
#Sta/Elev= 30
  4718.1 1057.29  4733.2 1055.50  4747.3 1053.25  4764.4 1049.21  4781.0 1046.99
  4834.6 1036.17  4869.5 1027.41  4894.1 1017.24  4931.2 1007.52  4936.8 1006.63
  4940.9 1005.20  4959.8  997.95  4960.6  994.47  4963.1  989.47  5036.9  989.47
  5039.4  994.47  5043.5  998.77  5049.8 1000.72  5072.7 1001.28  5136.8 1006.09
  5151.8 1007.86  5159.6 1009.21  5187.5 1014.96  5198.5 1018.34  5209.4 1022.27
  5217.1 1024.23  5241.9 1031.80  5254.0 1034.87  5344.2 1050.02  5381.0 1055.53
#Mann=3,-1,0
  4718.1    0.14       0  4960.6    0.04       0  5039.4    0.08       0
Bank Sta=4960.6,5039.4
XS Rating Curve= 0
Exp/Cntr=0.3,0.1

Type RM Length L Ch R = 1,88998,493,493,493
BEGIN DESCRIPTION:
Fisher River 178.0
END DESCRIPTION:
XS GIS Cut Line= 4
      1500669.47       970246.31      1500325.81       970326.18
      1500023.28       970500.43      1499986.96       970570.65
#Sta/Elev= 30
  4528.2 1061.01  4544.1 1058.87  4575.0 1051.52  4615.0 1044.15  4640.3 1040.38
  4684.2 1030.76  4709.0 1029.08  4750.2 1023.34  4785.2 1020.87  4797.8 1019.03
  4853.2 1015.91  4884.0 1010.93  4924.2 1005.89  4950.7 1000.56  4960.6  993.88
  4963.1  988.88  5036.9  988.88  5039.4  993.88  5048.1  996.87  5067.6  998.92
  5085.2  999.77  5099.1 1002.52  5124.8 1005.21  5148.1 1008.73  5159.7 1012.51
  5197.6 1028.55  5205.9 1032.87  5220.6 1038.14  5247.0 1044.67  5309.2 1056.71
#Mann=6,-1,0
  4528.2    0.14       0  4960.6    0.04       0  5039.4    0.14       0
  5067.6    0.08       0  5124.8    0.14       0  5220.6    0.08       0
Bank Sta=4960.6,5039.4
XS Rating Curve= 0
Exp/Cntr=0.3,0.1

Type RM Length L Ch R = 1,88505,509,509,509
BEGIN DESCRIPTION:
Fisher River 177.0
END DESCRIPTION:
XS GIS Cut Line= 3
      1500659.78       970023.15      1500379.97       969940.14
      1500083.76       969851.32
#Sta/Elev= 30
  4620.6 1057.08  4653.9 1052.06  4681.4 1046.41  4703.4 1043.50  4733.6 1037.99
  4782.9 1027.52  4790.8 1026.51  4836.2 1013.93  4858.5 1008.58  4918.2 1003.46
  4932.4 1003.89  4948.3  999.64  4956.2  994.81  4957.9  991.64  4960.6  991.64
  4963.1  986.64  5036.9  986.64  5037.0  991.64  5038.3  999.13  5041.3  998.58
  5053.9 1009.96  5060.9 1014.07  5074.7 1015.65  5078.8 1018.83  5102.9 1033.89
  5116.6 1045.06  5130.8 1052.36  5165.8 1072.94  5193.8 1085.81  5221.7 1096.19
#Mann=3,-1,0
  4620.6    0.14       0  4960.6    0.04       0  5037.0    0.14       0
Bank Sta=4960.6,5037
XS Rating Curve= 0
Exp/Cntr=0.3,0.1

Type RM Length L Ch R = 1,87996,494,494,494
BEGIN DESCRIPTION:
Fisher River 176.0
END DESCRIPTION:
XS GIS Cut Line= 3
      1500853.39       969425.36      1500502.48       969459.24
      1500229.03       969340.67
#Sta/Elev= 30
  4554.1 1070.30  4646.3 1049.12  4664.5 1043.98  4698.5 1035.81  4770.5 1020.70
  4806.6 1011.69  4830.4 1007.60  4866.2 1003.76  4918.9 1002.00  4947.8  999.87
  4959.9  990.16  4962.4  985.16  5034.5  985.16  5034.6  990.16  5035.5  995.99
  5042.2  998.17  5054.9 1005.07  5069.1 1018.93  5076.8 1027.49  5101.3 1041.75
  5111.8 1051.46  5119.0 1054.84  5132.4 1065.37  5143.9 1073.25  5153.7 1081.27
  5156.4 1084.11  5174.0 1092.24  5181.4 1094.80  5190.3 1097.15  5204.7 1098.64
#Mann=3,-1,0
  4554.1    0.14       0  4959.9    0.04       0  5034.6    0.14       0
Bank Sta=4959.9,5034.6
XS Rating Curve= 0
Exp/Cntr=0.3,0.1

Type RM Length L Ch R = 1,87502,502,502,502
BEGIN DESCRIPTION:
Fisher River 175.0
END DESCRIPTION:
XS GIS Cut Line= 3
      1500916.38       969233.71      1500628.34       968972.29
      1500301.60       968863.38
#Sta/Elev= 30
  4553.6 1071.96  4595.3 1064.20  4623.7 1056.83  4719.9 1034.55  4727.0 1032.71
  4746.5 1026.25  4773.4 1019.90  4823.7 1006.65  4843.6 1003.81  4866.5 1002.23
  4880.6 1002.26  4922.2  999.22  4940.6  999.77  4953.6  990.25  4959.9  988.34
  4962.4  983.34  5052.6  983.34  5052.7  988.34  5054.2  988.34  5054.3  998.53
  5055.4  999.23  5061.7 1001.26  5071.7 1006.61  5105.8 1021.45  5150.0 1036.54
  5165.5 1042.75  5178.8 1047.01  5231.1 1058.75  5262.2 1064.14  5287.0 1066.95
#Mann=3,-1,0
  4553.6    0.14       0  4959.9    0.04       0  5052.7    0.14       0
Bank Sta=4959.9,5052.7
XS Rating Curve= 0
Exp/Cntr=0.3,0.1

Type RM Length L Ch R = 1,87000,504,504,504
BEGIN DESCRIPTION:
Fisher River 174.0
END DESCRIPTION:
XS GIS Cut Line= 4
      1500976.88       968471.54      1500814.70       968469.12
      1500638.02       968464.28      1500415.37       968466.70
#Sta/Elev= 30
  4708.4 1072.52  4743.9 1066.31  4759.6 1062.85  4785.5 1057.97  4823.5 1046.68
  4853.0 1035.03  4860.3 1033.73  4886.2 1017.64  4889.3 1014.96  4908.5 1004.22
  4924.6  999.03  4935.4  998.19  4937.1  996.90  4959.9  987.14  4965.3  982.14
  5022.7  982.14  5026.6  987.14  5039.2  995.97  5049.2  998.32  5076.9 1001.04
  5089.7 1001.52  5093.4 1002.65  5150.8 1025.91  5163.2 1030.06  5194.6 1043.70
  5212.4 1049.04  5222.6 1053.43  5238.6 1057.19  5263.6 1060.17  5270.0 1061.29
#Mann=3,-1,0
  4708.4    0.14       0  4959.9    0.04       0  5026.6    0.14       0
Bank Sta=4959.9,5026.6
XS Rating Curve= 0
Exp/Cntr=0.3,0.1

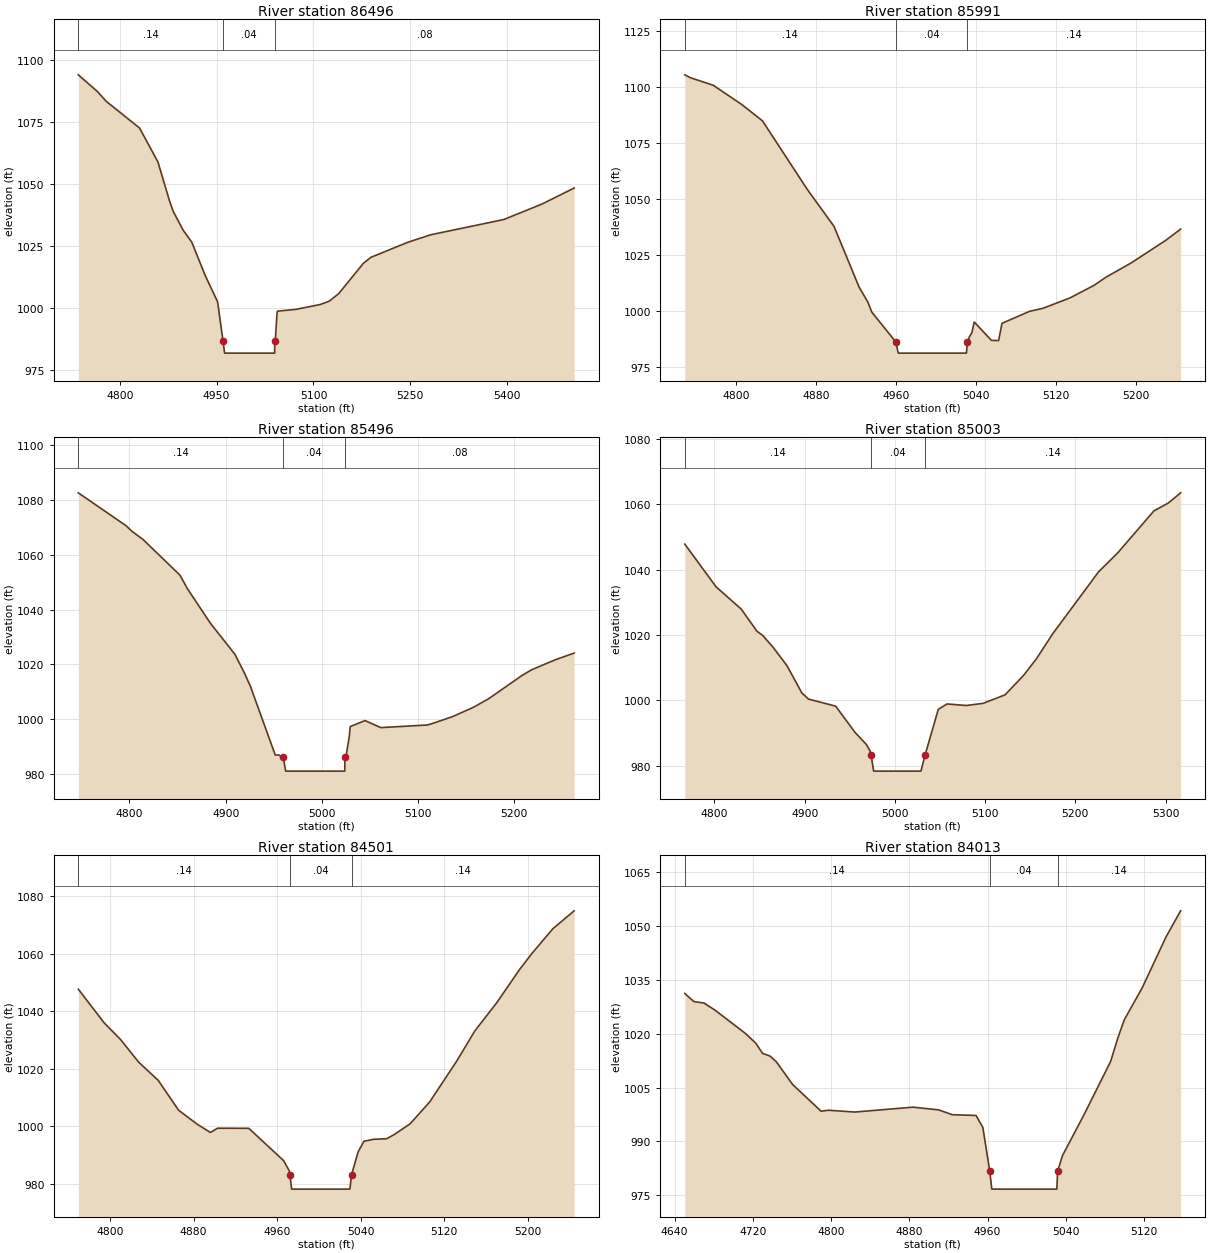
Type RM Length L Ch R = 1,86496,505,505,505
BEGIN DESCRIPTION:
Fisher River 173.0
END DESCRIPTION:
XS GIS Cut Line= 4
      1500959.94       967893.09      1500821.96       967953.61
      1500502.48       967980.23      1500422.62       968265.82
#Sta/Elev= 30
  4735.9 1094.12  4765.6 1087.35  4779.0 1083.45  4830.7 1072.66  4859.2 1058.95
  4877.2 1043.18  4882.7 1039.14  4897.8 1031.59  4911.6 1026.61  4932.1 1013.31
  4950.8 1002.96  4951.7 1002.30  4959.9  986.83  4962.4  981.83  5039.9  981.83
  5040.0  986.83  5040.9  986.84  5043.6  997.95  5044.3  998.77  5072.4  999.47
  5110.5 1001.45  5124.7 1002.82  5139.1 1005.84  5177.2 1018.03  5189.0 1020.49
  5246.2 1026.56  5281.5 1029.58  5394.7 1035.73  5454.0 1041.99  5503.7 1048.44
#Mann=3,-1,0
  4735.9    0.14       0  4959.9    0.04       0  5040.0    0.08       0
Bank Sta=4959.9,5040
XS Rating Curve= 0
Exp/Cntr=0.3,0.1

Type RM Length L Ch R = 1,85991,495,495,495
BEGIN DESCRIPTION:
Fisher River 172.0
END DESCRIPTION:
XS GIS Cut Line= 4
      1500899.45       967450.20      1500717.89       967452.62
      1500584.77       967469.56      1500408.13       967505.86
#Sta/Elev= 30
  4748.8 1105.36  4754.4 1104.07  4777.2 1100.72  4805.8 1092.11  4826.5 1084.82
  4871.5 1054.12  4898.1 1037.72  4923.3 1010.52  4932.0 1003.90  4935.9  999.44
  4959.9  986.14  4962.4  981.14  5030.6  981.14  5031.5  986.14  5032.6  986.99
  5033.2  988.11  5036.1  990.37  5038.4  995.03  5055.6  986.83  5062.8  986.76
  5066.1  994.29  5066.5  994.51  5093.9  999.82  5107.4 1001.18  5134.4 1005.83
  5158.4 1011.42  5169.9 1014.95  5195.8 1021.50  5229.8 1031.42  5244.9 1036.49
#Mann=3,-1,0
  4748.8    0.14       0  4959.9    0.04       0  5031.5    0.14       0
Bank Sta=4959.9,5031.5
XS Rating Curve= 0
Exp/Cntr=0.3,0.1

Type RM Length L Ch R = 1,85496,493,493,493
BEGIN DESCRIPTION:
Fisher River 171.0
END DESCRIPTION:
XS GIS Cut Line= 4
      1500792.92       966845.13      1500671.90       966963.73
      1500541.21       966973.41      1500374.19       967108.96
#Sta/Elev= 30
  4746.8 1082.65  4796.4 1070.63  4802.7 1068.55  4814.0 1065.63  4852.5 1052.57
  4860.3 1047.59  4884.1 1035.01  4909.6 1023.67  4919.2 1017.04  4925.7 1012.01
  4951.6  986.82  4955.0  986.89  4959.9  985.96  4962.4  980.96  5023.9  980.96
  5024.0  985.96  5025.0  985.96  5028.6  993.70  5029.5  997.23  5044.9  999.43
  5061.4  996.86  5109.8  997.82  5116.6  998.55  5135.7 1000.85  5157.3 1004.22
  5173.5 1007.41  5207.9 1015.85  5218.1 1017.98  5242.5 1021.61  5262.4 1024.09
#Mann=3,-1,0
  4746.8    0.14       0  4959.9    0.04       0  5024.0    0.08       0
Bank Sta=4959.9,5024
XS Rating Curve= 0
Exp/Cntr=0.3,0.1

Type RM Length L Ch R = 1,85003,502,502,502
BEGIN DESCRIPTION:
Fisher River 170.0
END DESCRIPTION:
XS GIS Cut Line= 4
      1500652.58       966391.07      1500514.59       966492.75
      1500374.21       966504.85      1500158.77       966405.60
#Sta/Elev= 30
  4767.2 1047.76  4801.8 1034.73  4829.8 1027.89  4847.1 1021.16  4853.8 1019.78
  4865.0 1016.25  4880.5 1010.59  4896.9 1002.28  4904.4 1000.39  4934.4  998.24
  4955.6  990.31  4968.3  986.56  4972.8  984.41  4973.6  983.38  4976.5  978.38
  5028.9  978.38  5033.6  983.38  5048.1  997.24  5057.8  998.91  5079.2  998.44
  5097.9  999.10  5122.1 1001.69  5142.9 1007.72  5156.9 1012.72  5174.8 1020.31
  5225.8 1039.30  5246.9 1045.06  5287.2 1057.94  5302.8 1060.27  5316.7 1063.44
#Mann=3,-1,0
  4767.2    0.14       0  4973.6    0.04       0  5033.6    0.14       0
Bank Sta=4973.6,5033.6
XS Rating Curve= 0
Exp/Cntr=0.3,0.1

Type RM Length L Ch R = 1,84501,488,488,488
BEGIN DESCRIPTION:
Fisher River 169.0
END DESCRIPTION:
XS GIS Cut Line= 3
      1500662.23       966037.74      1500526.69       966001.44
      1500192.73       965984.50
#Sta/Elev= 30
  4769.6 1047.69  4794.2 1036.05  4810.1 1030.15  4827.3 1022.34  4846.2 1015.93
  4865.5 1005.61  4883.5 1000.68  4896.1  997.84  4902.9  999.31  4932.8  999.28
  4966.2  988.01  4971.7  984.37  4972.2  983.11  4973.8  978.11  5029.6  978.11
  5031.2  983.11  5037.4  991.02  5043.0  994.76  5052.5  995.47  5064.6  995.63
  5071.9  997.07  5087.2 1000.82  5106.0 1008.47  5131.6 1022.52  5149.1 1033.12
  5170.5 1043.15  5192.1 1054.58  5204.0 1060.20  5223.9 1068.75  5244.3 1074.98
#Mann=3,-1,0
  4769.6    0.14       0  4972.2    0.04       0  5031.2    0.14       0
Bank Sta=4972.2,5031.2
XS Rating Curve= 0
Exp/Cntr=0.3,0.1

Type RM Length L Ch R = 1,84013,550,550,550
BEGIN DESCRIPTION:
Fisher River 168.0
END DESCRIPTION:
XS GIS Cut Line= 3
      1500696.08       965754.54      1500512.17       965522.23
      1500306.44       965476.24
#Sta/Elev= 30
  4650.4 1031.23  4659.7 1028.98  4670.1 1028.56  4681.4 1026.57  4712.2 1020.14
  4723.1 1017.35  4729.9 1014.54  4737.6 1013.78  4743.9 1012.23  4760.7 1005.86
  4789.8  998.42  4797.4  998.69  4824.2  998.18  4883.9  999.55  4910.1  998.78
  4924.0  997.44  4948.3  997.23  4955.2  993.92  4962.3  981.70  4964.4  976.70
  5030.9  976.70  5031.7  981.70  5036.7  986.06  5058.5  997.33  5085.9 1012.28
  5093.3 1018.82  5099.9 1023.91  5118.3 1032.86  5142.7 1047.07  5157.5 1054.27
#Mann=3,-1,0
  4650.4    0.14       0  4962.3    0.04       0  5031.7    0.14       0
Bank Sta=4962.3,5031.7
XS Rating Curve= 0
Exp/Cntr=0.3,0.1

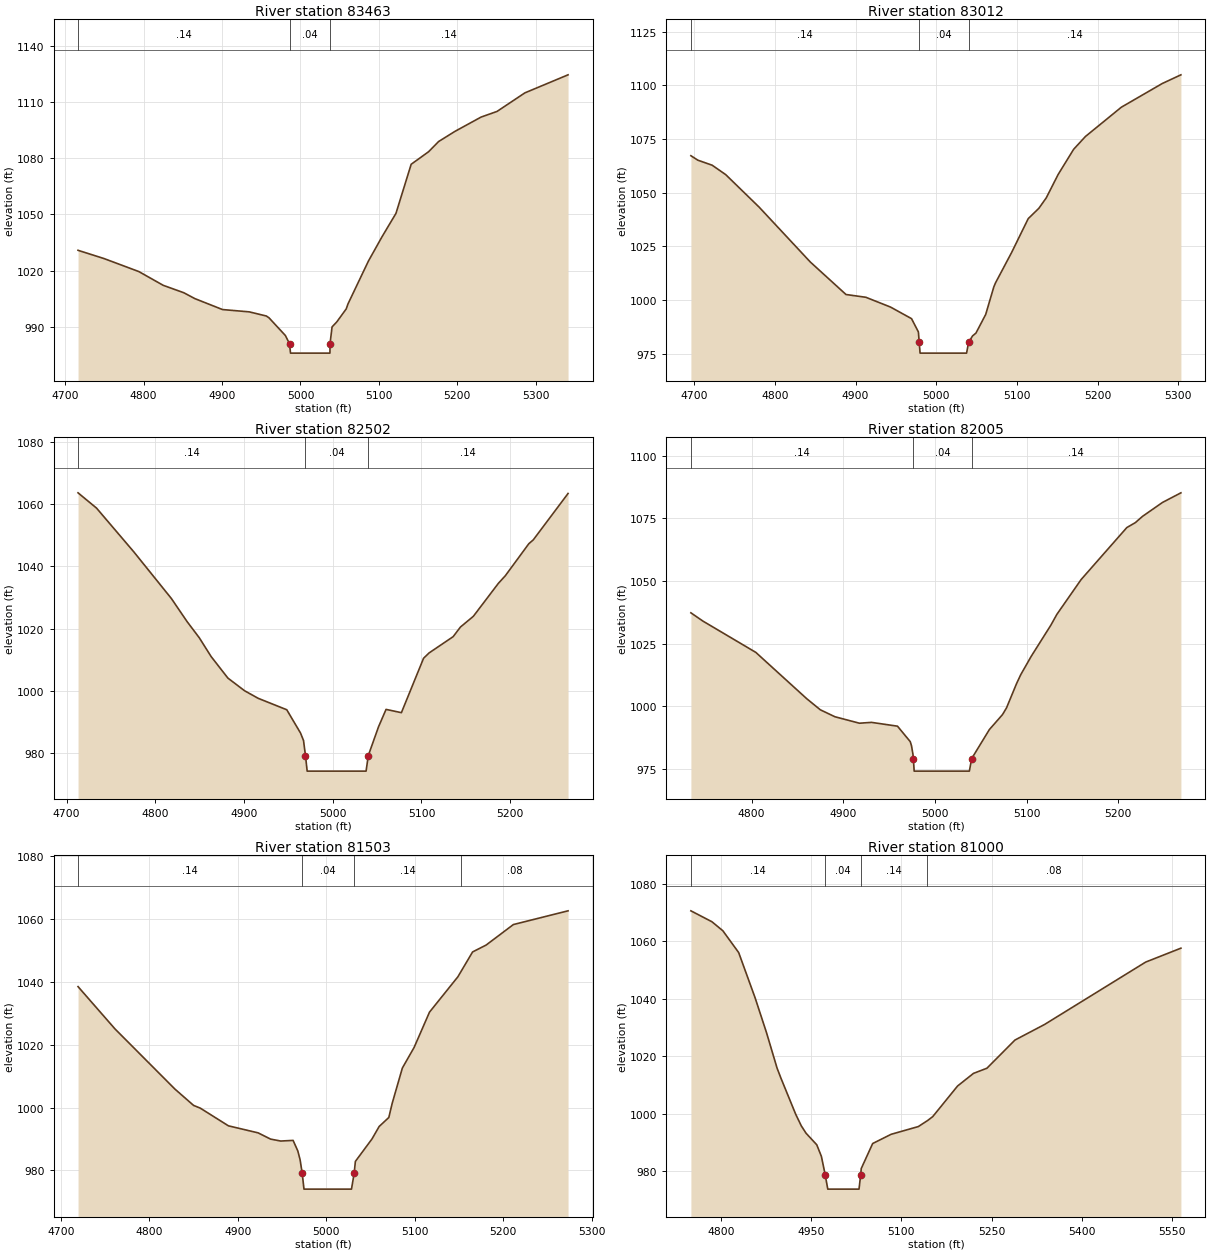
Type RM Length L Ch R = 1,83463,451,451,451
BEGIN DESCRIPTION:
Fisher River 167.0
END DESCRIPTION:
XS GIS Cut Line= 5
      1500722.73       965759.40      1500730.94       965738.99
      1500785.65       965573.06      1501015.58       965391.54
      1500991.37       965258.38
#Sta/Elev= 30
  4716.3 1030.82  4749.4 1026.42  4793.8 1019.47  4825.0 1012.10  4851.1 1008.17
  4865.3 1005.01  4900.6  999.16  4934.7  997.93  4956.5  995.71  4959.8  994.78
  4980.7  985.32  4986.1  980.88  4987.3  975.88  5037.6  975.88  5037.7  980.88
  5040.3  989.90  5046.3  992.55  5058.4  999.53  5060.5 1002.07  5086.7 1025.09
  5103.8 1037.90  5121.8 1050.56  5141.2 1076.79  5163.4 1083.49  5176.2 1088.94
  5196.9 1094.34  5230.3 1102.00  5250.7 1105.03  5286.2 1114.94  5341.3 1124.59
#Mann=3,-1,0
  4716.3    0.14       0  4986.1    0.04       0  5037.7    0.14       0
Bank Sta=4986.1,5037.7
XS Rating Curve= 0
Exp/Cntr=0.3,0.1

Type RM Length L Ch R = 1,83012,510,510,510
BEGIN DESCRIPTION:
Fisher River 166.0
END DESCRIPTION:
XS GIS Cut Line= 3
      1500826.78       966081.32      1500972.01       965955.46
      1501351.96       965788.47
#Sta/Elev= 30
  4696.0 1067.19  4704.6 1065.11  4722.3 1062.77  4739.1 1058.39  4780.5 1043.25
  4844.1 1017.60  4888.2 1002.50  4912.8 1001.21  4943.4  996.64  4969.4  991.25
  4977.9  985.06  4978.9  980.18  4980.0  975.18  5037.6  975.18  5040.1  980.18
  5045.0  983.19  5049.2  984.51  5061.3  993.21  5071.3 1005.98  5073.4 1007.89
  5093.4 1022.07  5114.0 1037.86  5127.2 1042.69  5136.3 1047.52  5151.1 1058.46
  5170.3 1070.19  5184.9 1076.15  5229.4 1089.80  5280.1 1100.84  5303.2 1104.89
#Mann=3,-1,0
  4696.0    0.14       0  4978.9    0.04       0  5040.1    0.14       0
Bank Sta=4978.9,5040.1
XS Rating Curve= 0
Exp/Cntr=0.3,0.1

Type RM Length L Ch R = 1,82502,497,497,497
BEGIN DESCRIPTION:
Fisher River 165.0
END DESCRIPTION:
XS GIS Cut Line= 3
      1500988.97       966468.54      1501364.09       966352.38
      1501511.68       966412.86
#Sta/Elev= 30
  4713.0 1063.64  4733.8 1058.75  4775.9 1044.68  4818.2 1029.72  4835.9 1022.31
  4849.6 1017.14  4863.0 1011.09  4881.9 1004.18  4900.7 1000.12  4915.9  997.71
  4948.2  994.03  4963.7  986.57  4967.1  984.15  4969.3  979.33  4971.2  974.33
  5037.6  974.33  5040.1  979.33  5051.6  988.54  5060.1  994.14  5077.4  993.09
  5102.4 1010.56  5108.6 1012.26  5135.7 1017.48  5143.9 1020.56  5158.5 1024.02
  5186.7 1034.60  5194.5 1037.03  5221.0 1047.31  5226.0 1048.54  5265.2 1063.43
#Mann=3,-1,0
  4713.0    0.14       0  4969.3    0.04       0  5040.1    0.14       0
Bank Sta=4969.3,5040.1
XS Rating Curve= 0
Exp/Cntr=0.3,0.1

Type RM Length L Ch R = 1,82005,502,502,502
BEGIN DESCRIPTION:
Fisher River 164.0
END DESCRIPTION:
XS GIS Cut Line= 3
      1501131.76       966857.97      1501330.21       966874.91
      1501656.93       966799.88
#Sta/Elev= 30
  4733.9 1037.34  4747.1 1034.02  4804.7 1021.55  4860.3 1003.04  4875.0  998.65
  4890.9  995.87  4917.7  993.28  4930.8  993.62  4959.2  992.10  4973.1  985.94
  4974.5  984.28  4976.1  980.81  4976.5  979.16  4977.4  974.16  5037.6  974.16
  5040.1  979.16  5059.4  990.74  5073.7  996.71  5078.1  999.40  5089.1 1009.12
  5093.7 1012.71  5105.0 1019.95  5126.6 1032.49  5132.9 1036.66  5159.5 1050.63
  5209.3 1071.36  5218.7 1073.36  5226.4 1075.83  5248.3 1081.41  5268.3 1085.23
#Mann=3,-1,0
  4733.9    0.14       0  4976.5    0.04       0  5040.1    0.14       0
Bank Sta=4976.5,5040.1
XS Rating Curve= 0
Exp/Cntr=0.3,0.1

Type RM Length L Ch R = 1,81503,503,503,503
BEGIN DESCRIPTION:
Fisher River 163.0
END DESCRIPTION:
XS GIS Cut Line= 4
      1501175.34       967354.12      1501393.13       967358.96
      1501557.71       967356.53      1501705.37       967269.39
#Sta/Elev= 30
  4719.5 1038.42  4761.2 1025.00  4829.0 1005.87  4850.1 1000.68  4857.7  999.81
  4889.5  994.19  4923.0  991.96  4937.2  989.97  4948.6  989.36  4962.6  989.56
  4967.9  986.23  4970.5  983.43  4972.9  979.08  4974.9  974.08  5028.6  974.08
  5031.6  979.08  5033.0  982.89  5051.7  989.99  5059.9  993.99  5070.8  996.84
  5074.6 1001.34  5086.1 1012.55  5099.4 1019.11  5116.8 1030.32  5148.8 1041.52
  5152.5 1043.27  5165.5 1049.44  5180.7 1051.61  5211.6 1058.14  5273.4 1062.50
#Mann=4,-1,0
  4719.5    0.14       0  4972.9    0.04       0  5031.6    0.14       0
  5152.5    0.08       0
Bank Sta=4972.9,5031.6
XS Rating Curve= 0
Exp/Cntr=0.3,0.1

Type RM Length L Ch R = 1,81000,500,500,500
BEGIN DESCRIPTION:
Fisher River 162.0
END DESCRIPTION:
XS GIS Cut Line= 4
      1501374.98       968025.02      1501543.21       967840.63
      1501634.26       967732.58      1501719.87       967317.82
#Sta/Elev= 30
  4750.4 1070.65  4785.3 1066.86  4803.5 1063.72  4829.8 1056.14  4857.2 1040.35
  4876.1 1028.26  4893.6 1015.96  4900.0 1012.48  4924.5  999.94  4933.9  995.87
  4941.8  993.30  4959.6  989.28  4967.3  985.24  4973.6  978.86  4977.9  973.86
  5029.8  973.86  5032.6  978.86  5033.5  981.01  5052.5  989.72  5083.1  992.92
  5128.4  995.62  5143.6  997.69  5152.3  999.07  5193.6 1009.72  5220.0 1014.11
  5242.4 1015.91  5289.0 1025.71  5338.0 1031.10  5506.2 1052.82  5564.8 1057.66
#Mann=4,-1,0
  4750.4    0.14       0  4973.6    0.04       0  5032.6    0.14       0
  5143.6    0.08       0
Bank Sta=4973.6,5032.6
XS Rating Curve= 0
Exp/Cntr=0.3,0.1

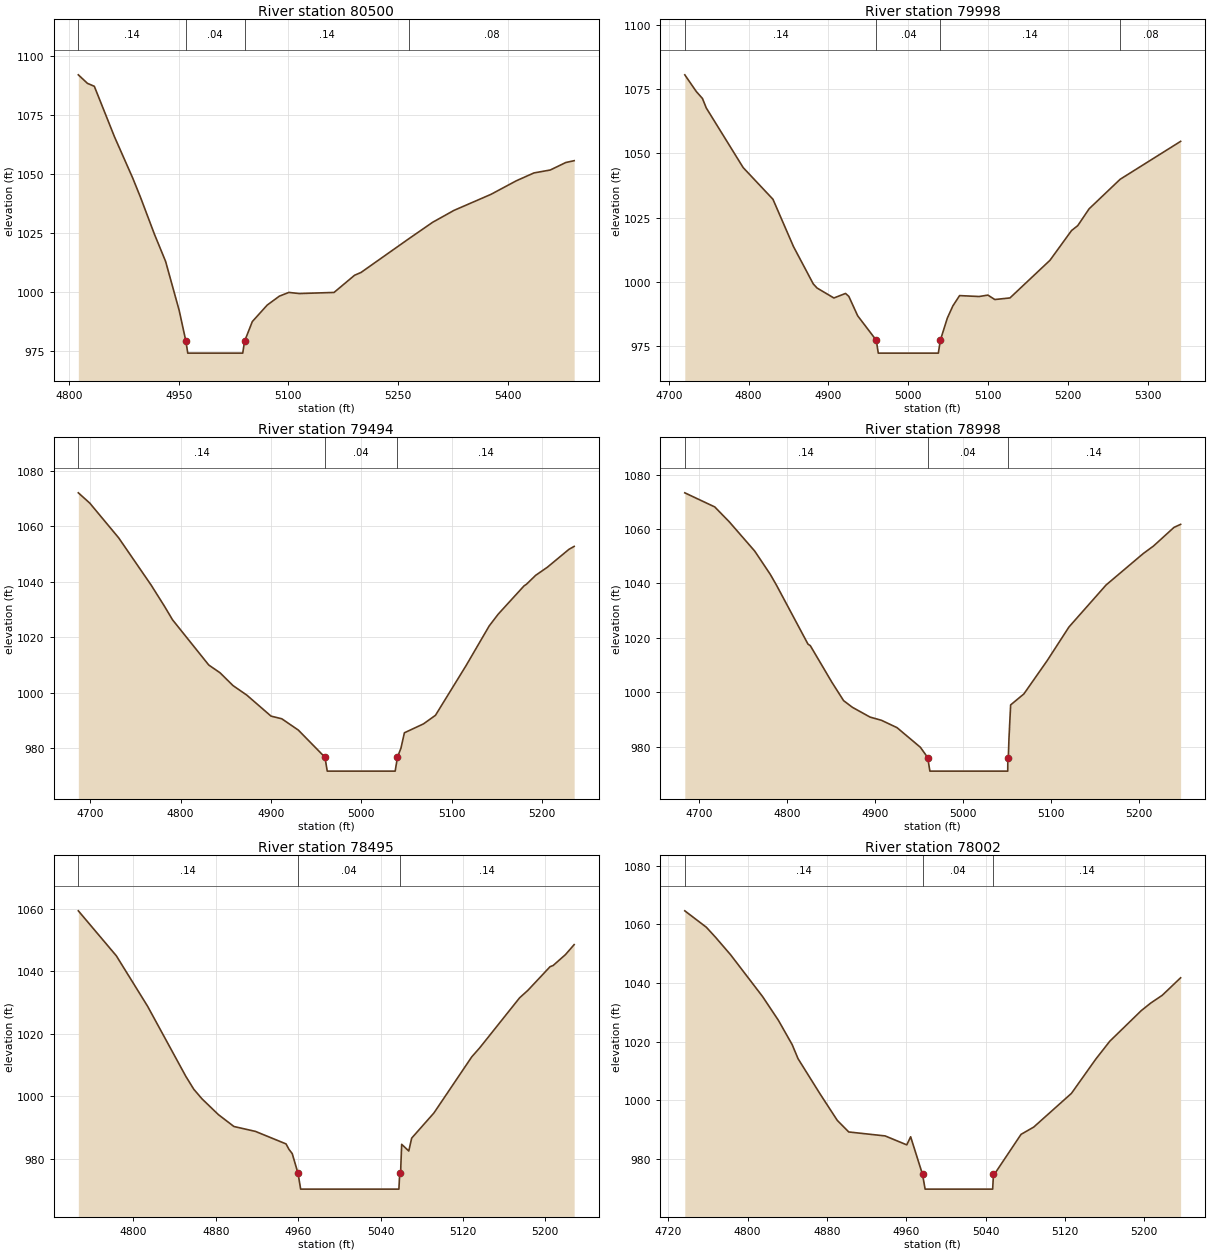
Type RM Length L Ch R = 1,80500,502,502,502
BEGIN DESCRIPTION:
Fisher River 161.0
END DESCRIPTION:
XS GIS Cut Line= 4
      1502124.98       967874.98      1501989.79       967745.33
      1501843.20       967593.81      1501756.17       967327.50
#Sta/Elev= 30
  4812.7 1092.09  4825.1 1088.49  4834.6 1087.21  4862.1 1065.82  4887.0 1048.33
  4897.6 1040.20  4917.0 1024.26  4932.1 1012.86  4950.7  992.01  4959.9  978.91
  4962.4  973.91  5037.6  973.91  5040.1  978.91  5050.7  987.31  5071.1  994.32
  5087.7  998.10  5100.7  999.69  5114.9  999.21  5162.5  999.68  5190.6 1006.98
  5199.4 1008.16  5265.6 1022.65  5297.4 1029.47  5326.5 1034.51  5377.3 1041.35
  5411.9 1047.10  5436.0 1050.43  5458.3 1051.67  5479.6 1054.86  5491.0 1055.63
#Mann=4,-1,0
  4812.7    0.14       0  4959.9    0.04       0  5040.1    0.14       0
  5265.6    0.08       0
Bank Sta=4959.9,5040.1
XS Rating Curve= 0
Exp/Cntr=0.3,0.1

Type RM Length L Ch R = 1,79998,504,504,504
BEGIN DESCRIPTION:
Fisher River 160.0
END DESCRIPTION:
XS GIS Cut Line= 3
      1502545.13       967383.15      1502201.50       967320.23
      1501983.68       967158.08
#Sta/Elev= 30
  4720.1 1080.50  4734.5 1074.01  4742.2 1071.31  4747.0 1067.61  4793.2 1044.43
  4830.5 1032.11  4856.2 1013.72  4881.0  999.19  4885.7  997.61  4906.8  993.73
  4921.4  995.50  4925.5  994.35  4936.6  986.81  4959.9  977.29  4962.4  972.29
  5037.6  972.29  5040.1  977.29  5048.9  985.94  5055.8  990.65  5064.2  994.66
  5088.6  994.30  5099.7  994.85  5108.3  993.13  5127.3  993.75  5177.4 1008.39
  5204.4 1019.95  5212.2 1021.87  5226.4 1028.40  5265.3 1039.89  5341.0 1054.63
#Mann=4,-1,0
  4720.1    0.14       0  4959.9    0.04       0  5040.1    0.14       0
  5265.3    0.08       0
Bank Sta=4959.9,5040.1
XS Rating Curve= 0
Exp/Cntr=0.3,0.1

Type RM Length L Ch R = 1,79494,496,496,496
BEGIN DESCRIPTION:
Fisher River 159.0
END DESCRIPTION:
XS GIS Cut Line= 3
      1502687.97       966942.67      1502484.67       966860.38
      1502160.35       966802.30
#Sta/Elev= 30
  4686.9 1072.14  4699.5 1068.45  4731.5 1055.90  4767.5 1038.81  4782.1 1031.24
  4791.2 1026.26  4831.3 1009.93  4843.7 1007.15  4858.1 1002.51  4873.4  999.06
  4900.2  991.48  4912.1  990.52  4930.4  986.44  4959.9  976.61  4962.4  971.61
  5037.6  971.61  5040.1  976.61  5044.0  979.91  5047.8  985.46  5068.9  988.67
  5082.2  991.78  5116.0 1009.69  5141.7 1024.07  5151.6 1028.30  5180.3 1038.55
  5182.9 1039.11  5193.1 1042.34  5206.1 1045.28  5229.9 1051.72  5235.7 1052.79
#Mann=3,-1,0
  4686.9    0.14       0  4959.9    0.04       0  5040.1    0.14       0
Bank Sta=4959.9,5040.1
XS Rating Curve= 0
Exp/Cntr=0.3,0.1

Type RM Length L Ch R = 1,78998,503,503,503
BEGIN DESCRIPTION:
Fisher River 158.0
END DESCRIPTION:
XS GIS Cut Line= 3
      1502796.85       966461.03      1502644.40       966386.02
      1502257.19       966318.25
#Sta/Elev= 30
  4684.1 1073.27  4718.1 1068.09  4734.5 1062.65  4763.5 1051.85  4781.2 1043.28
  4788.2 1039.33  4824.0 1017.64  4826.6 1017.09  4851.2 1003.59  4864.4  996.88
  4874.4  994.42  4894.5  990.82  4907.4  989.65  4925.1  986.94  4951.6  979.73
  4959.9  975.96  4962.4  970.96  5050.8  970.96  5050.9  975.96  5051.5  976.31
  5052.2  983.00  5054.1  995.31  5069.1  999.33  5095.7 1011.64  5120.3 1023.94
  5162.5 1039.40  5204.6 1050.93  5216.4 1053.74  5239.6 1060.57  5247.1 1061.68
#Mann=3,-1,0
  4684.1    0.14       0  4959.9    0.04       0  5050.9    0.14       0
Bank Sta=4959.9,5050.9
XS Rating Curve= 0
Exp/Cntr=0.3,0.1

Type RM Length L Ch R = 1,78495,493,493,493
BEGIN DESCRIPTION:
Fisher River 157.0
END DESCRIPTION:
XS GIS Cut Line= 4
      1502854.94       965914.55      1502717.01       965890.35
      1502443.52       965837.11      1502383.01       965820.16
#Sta/Elev= 30
  4746.5 1059.31  4783.4 1044.93  4813.8 1028.77  4850.9 1006.37  4858.7 1002.22
  4866.6  999.18  4882.5  994.14  4897.6  990.34  4918.5  988.77  4948.2  984.77
  4951.1  983.01  4954.2  981.68  4959.9  975.31  4962.4  970.31  5057.8  970.31
  5058.6  975.31  5059.5  975.31  5059.7  977.81  5060.5  984.64  5067.4  982.50
  5070.2  986.61  5091.8  994.66  5128.6 1012.63  5136.2 1015.46  5175.0 1031.48
  5183.0 1033.86  5204.6 1041.44  5207.6 1041.83  5219.5 1045.29  5228.0 1048.50
#Mann=3,-1,0
  4746.5    0.14       0  4959.9    0.04       0  5058.6    0.14       0
Bank Sta=4959.9,5058.6
XS Rating Curve= 0
Exp/Cntr=0.3,0.1

Type RM Length L Ch R = 1,78002,496,496,496
BEGIN DESCRIPTION:
Fisher River 156.0
END DESCRIPTION:
XS GIS Cut Line= 4
      1502988.04       965480.10      1502859.80       965426.87
      1502688.10       965381.59      1502508.90       965342.17
#Sta/Elev= 30
  4736.7 1064.64  4758.4 1059.05  4767.9 1055.54  4783.0 1049.60  4815.2 1035.36
  4831.0 1027.33  4845.0 1018.97  4850.9 1014.19  4873.1 1002.17  4890.5  993.13
  4902.0  989.20  4938.7  987.85  4960.5  984.80  4964.4  987.56  4976.4  974.70
  4979.0  969.70  5047.1  969.70  5047.9  974.70  5048.7  974.74  5048.8  975.14
  5050.0  975.37  5075.7  988.38  5088.5  990.87  5126.5 1002.36  5151.1 1014.07
  5165.2 1020.16  5197.0 1030.62  5206.4 1033.16  5218.1 1035.83  5236.6 1041.80
#Mann=3,-1,0
  4736.7    0.14       0  4976.4    0.04       0  5047.9    0.14       0
Bank Sta=4976.4,5047.9
XS Rating Curve= 0
Exp/Cntr=0.3,0.1