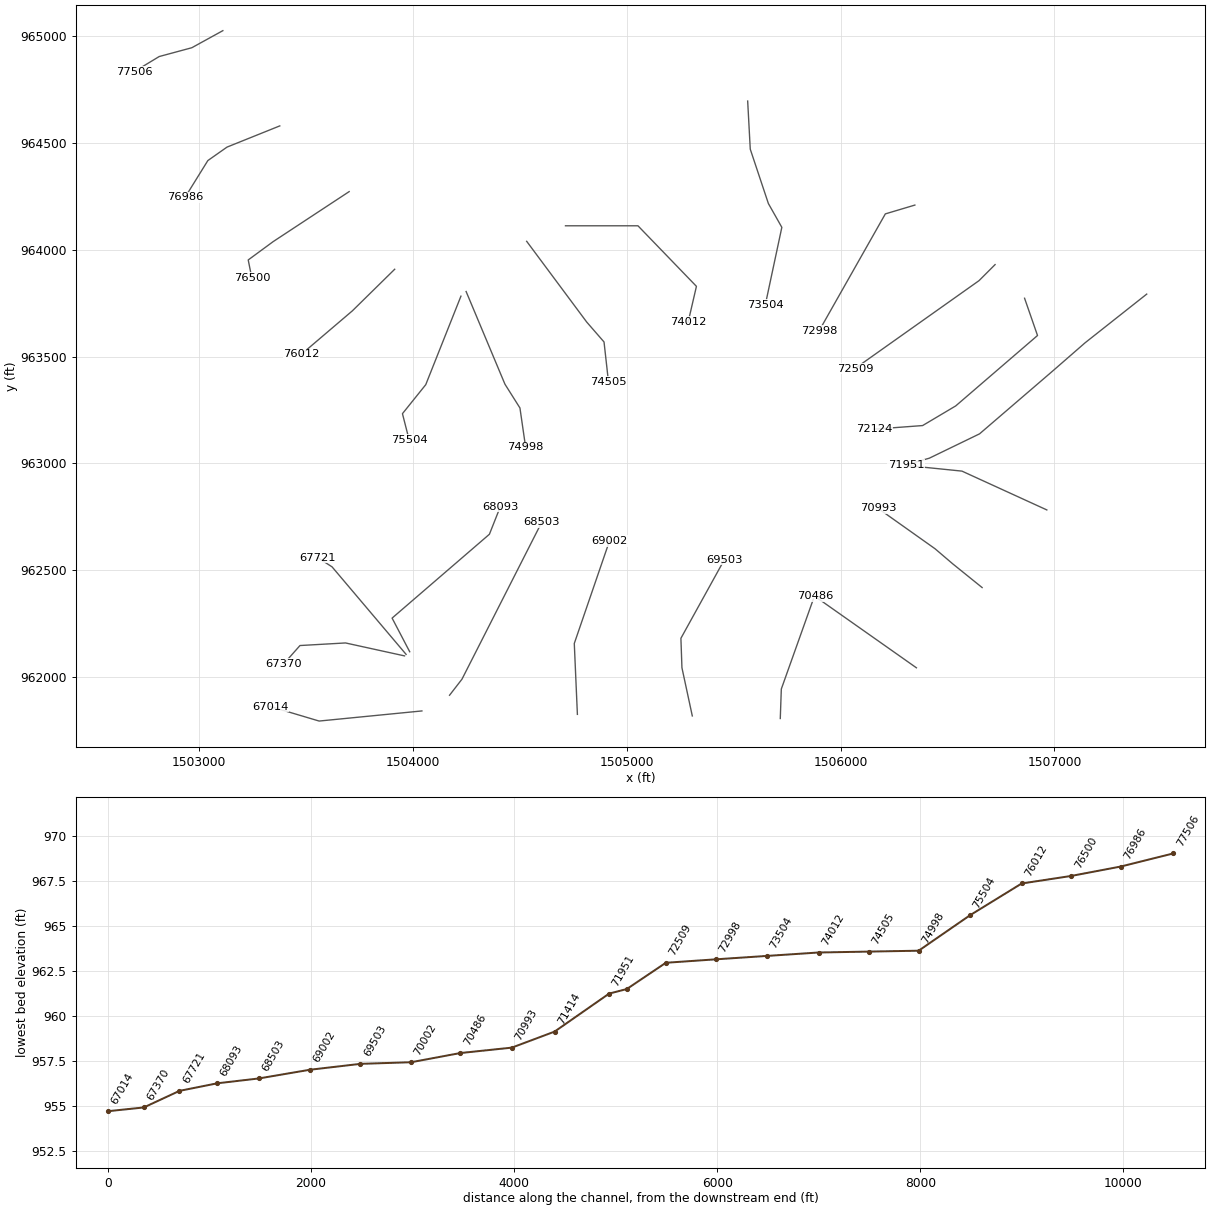
HEC-RAS study Fisher River.prj: Fisher River Limited Detail Study

--- Fisher River.g01 (geometry) --- (continued)

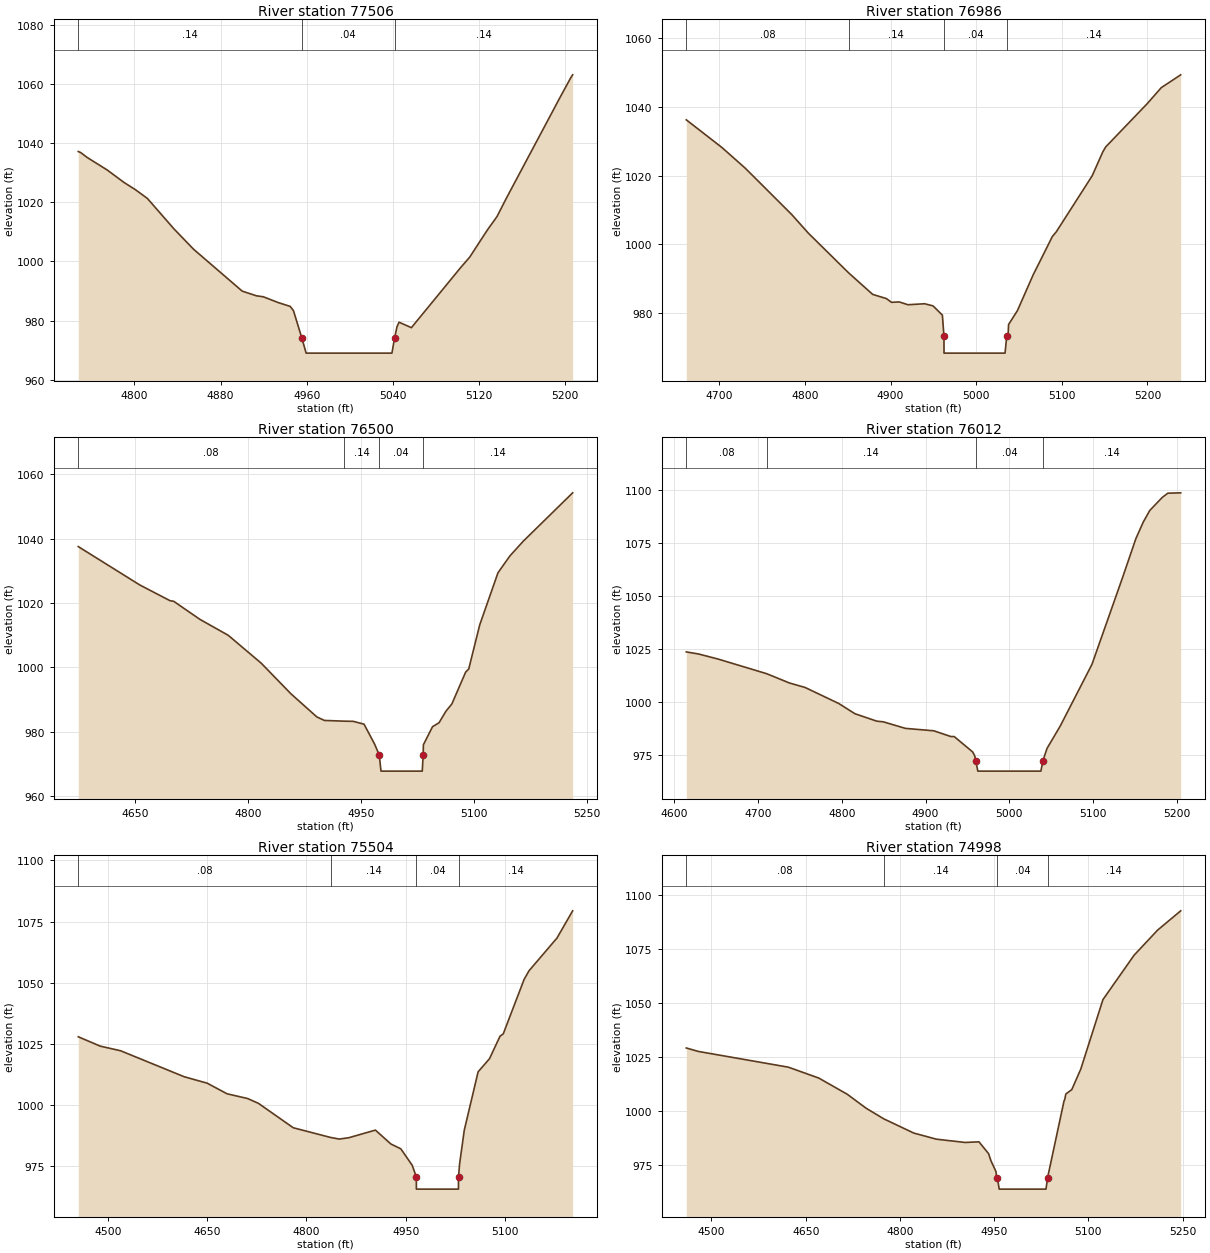
Type RM Length L Ch R = 1,77506,520,520,520
BEGIN DESCRIPTION:
Fisher River 155.0
END DESCRIPTION:
XS GIS Cut Line= 4
      1503111.48       965023.89      1502966.29       964944.03
      1502813.82       964902.89      1502697.69       964832.73
#Sta/Elev= 30
  4747.8 1037.11  4750.0 1036.78  4756.1 1035.10  4774.6 1030.90  4790.1 1026.72
  4801.1 1024.17  4812.0 1021.28  4836.7 1010.99  4854.9 1004.12  4900.1  989.97
  4913.3  988.39  4919.7  988.06  4933.9  986.06  4944.7  984.81  4947.7  983.40
  4955.6  974.03  4959.5  969.03  5039.2  969.03  5041.6  974.03  5043.9  977.92
  5045.8  979.47  5057.3  977.63  5102.5  997.68  5111.5 1001.47  5127.7 1010.52
  5136.8 1015.14  5145.3 1021.19  5195.8 1055.67  5205.4 1062.06  5207.1 1063.01
#Mann=3,-1,0
  4747.8    0.14       0  4955.6    0.04       0  5041.6    0.14       0
Bank Sta=4955.6,5041.6
XS Rating Curve= 0
Exp/Cntr=0.3,0.1

Type RM Length L Ch R = 1,76986,486,486,486
BEGIN DESCRIPTION:
Fisher River 154.0
END DESCRIPTION:
XS GIS Cut Line= 4
      1503377.72       964578.57      1503130.87       964479.35
      1503041.32       964416.42      1502934.86       964244.63
#Sta/Elev= 30
  4661.3 1036.24  4703.0 1028.16  4730.2 1022.15  4784.5 1008.65  4803.8 1003.26
  4850.8  991.71  4879.0  985.41  4895.1  984.18  4901.0  983.09  4910.1  983.21
  4920.2  982.39  4939.8  982.68  4949.6  982.05  4960.5  979.36  4962.3  973.30
  4962.4  968.30  5033.7  968.30  5035.7  973.30  5037.2  973.30  5037.8  976.62
  5048.2  980.70  5066.5  991.07  5089.0 1002.27  5093.5 1003.60  5135.5 1019.94
  5147.9 1026.90  5151.3 1028.35  5199.7 1040.92  5216.2 1045.60  5238.9 1049.34
#Mann=4,-1,0
  4661.3    0.08       0  4850.8    0.14       0  4962.3    0.04       0
  5035.7    0.14       0
Bank Sta=4962.3,5035.7
XS Rating Curve= 0
Exp/Cntr=0.3,0.1

Type RM Length L Ch R = 1,76500,488,488,488
BEGIN DESCRIPTION:
Fisher River 153.0
END DESCRIPTION:
XS GIS Cut Line= 4
      1503702.07       964271.22      1503346.78       964037.45
      1503230.10       963951.73      1503247.05       963866.99
#Sta/Elev= 30
  4574.7 1037.49  4656.6 1025.55  4696.5 1020.70  4701.4 1020.51  4736.3 1014.89
  4773.8 1009.96  4817.7 1001.28  4857.1  991.79  4891.5  984.61  4901.5  983.52
  4927.5  983.29  4939.8  983.24  4954.2  982.35  4968.0  976.27  4974.4  972.78
  4976.7  967.78  5031.5  967.78  5032.7  972.78  5033.0  975.97  5045.1  981.56
  5053.8  982.81  5062.9  986.37  5070.8  988.63  5089.1  998.52  5093.2  999.48
  5107.8 1013.19  5132.0 1029.34  5147.8 1034.57  5165.3 1039.09  5231.2 1054.18
#Mann=4,-1,0
  4574.7    0.08       0  4927.5    0.14       0  4974.4    0.04       0
  5032.7    0.14       0
Bank Sta=4974.4,5032.7
XS Rating Curve= 0
Exp/Cntr=0.3,0.1

Type RM Length L Ch R = 1,76012,508,508,508
BEGIN DESCRIPTION:
Fisher River 152.0
END DESCRIPTION:
XS GIS Cut Line= 3
      1503915.06       963908.20      1503717.14       963713.75
      1503479.36       963511.22
#Sta/Elev= 30
  4614.6 1023.62  4629.6 1022.60  4652.9 1020.20  4710.6 1013.32  4737.6 1008.96
  4756.3 1006.84  4796.5  999.27  4815.7  994.46  4841.7  990.95  4849.7  990.62
  4876.0  987.53  4909.9  986.39  4930.1  983.70  4934.2  983.67  4956.3  976.39
  4958.8  974.43  4959.9  972.36  4962.4  967.36  5037.6  967.36  5040.1  972.36
  5045.0  978.13  5060.6  988.56  5098.6 1017.79  5134.7 1058.32  5151.0 1077.14
  5159.7 1084.84  5167.5 1090.36  5182.5 1096.54  5189.1 1098.51  5204.4 1098.68
#Mann=4,-1,0
  4614.6    0.08       0  4710.6    0.14       0  4959.9    0.04       0
  5040.1    0.14       0
Bank Sta=4959.9,5040.1
XS Rating Curve= 0
Exp/Cntr=0.3,0.1

Type RM Length L Ch R = 1,75504,506,506,506
BEGIN DESCRIPTION:
Fisher River 151.0
END DESCRIPTION:
XS GIS Cut Line= 4
      1504224.84       963782.36      1504060.24       963368.46
      1503951.33       963232.92      1503982.80       963109.47
#Sta/Elev= 30
  4455.3 1027.91  4488.4 1024.08  4519.3 1022.18  4615.4 1011.55  4650.0 1008.93
  4680.0 1004.59  4711.1 1002.65  4727.4 1000.69  4780.0  990.70  4836.3  986.74
  4849.5  986.07  4864.2  986.64  4904.1  989.74  4927.5  984.05  4942.5  982.08
  4959.7  975.34  4965.9  970.60  4966.0  965.60  5029.5  965.60  5029.6  970.60
  5031.3  976.01  5038.3  989.68  5059.2 1013.56  5076.4 1018.94  5092.3 1028.12
  5097.2 1029.11  5128.7 1051.38  5136.1 1054.90  5178.3 1068.27  5202.0 1079.41
#Mann=4,-1,0
  4455.3    0.08       0  4836.3    0.14       0  4965.9    0.04       0
  5029.6    0.14       0
Bank Sta=4965.9,5029.6
XS Rating Curve= 0
Exp/Cntr=0.3,0.1

Type RM Length L Ch R = 1,74998,493,493,493
BEGIN DESCRIPTION:
Fisher River 150.0
END DESCRIPTION:
XS GIS Cut Line= 4
      1504249.02       963804.10      1504430.54       963370.88
      1504500.73       963259.54      1504527.36       963075.58
#Sta/Elev= 30
  4459.9 1029.06  4478.8 1027.47  4622.4 1020.16  4670.8 1015.12  4716.0 1007.64
  4746.4 1001.10  4774.4  996.20  4822.1  989.62  4858.0  986.79  4904.0  985.26
  4925.9  985.56  4941.2  980.08  4945.0  976.78  4952.9  971.82  4954.3  968.63
  4955.4  968.63  4958.1  963.63  5032.6  963.63  5035.1  968.63  5035.7  968.64
  5036.1  970.21  5061.2 1004.32  5062.5 1005.23  5064.2 1007.73  5073.7 1009.76
  5088.0 1019.26  5123.3 1051.48  5172.9 1072.05  5210.3 1083.68  5247.1 1092.63
#Mann=4,-1,0
  4459.9    0.08       0  4774.4    0.14       0  4955.4    0.04       0
  5035.1    0.14       0
Bank Sta=4955.4,5035.1
XS Rating Curve= 0
Exp/Cntr=0.3,0.1

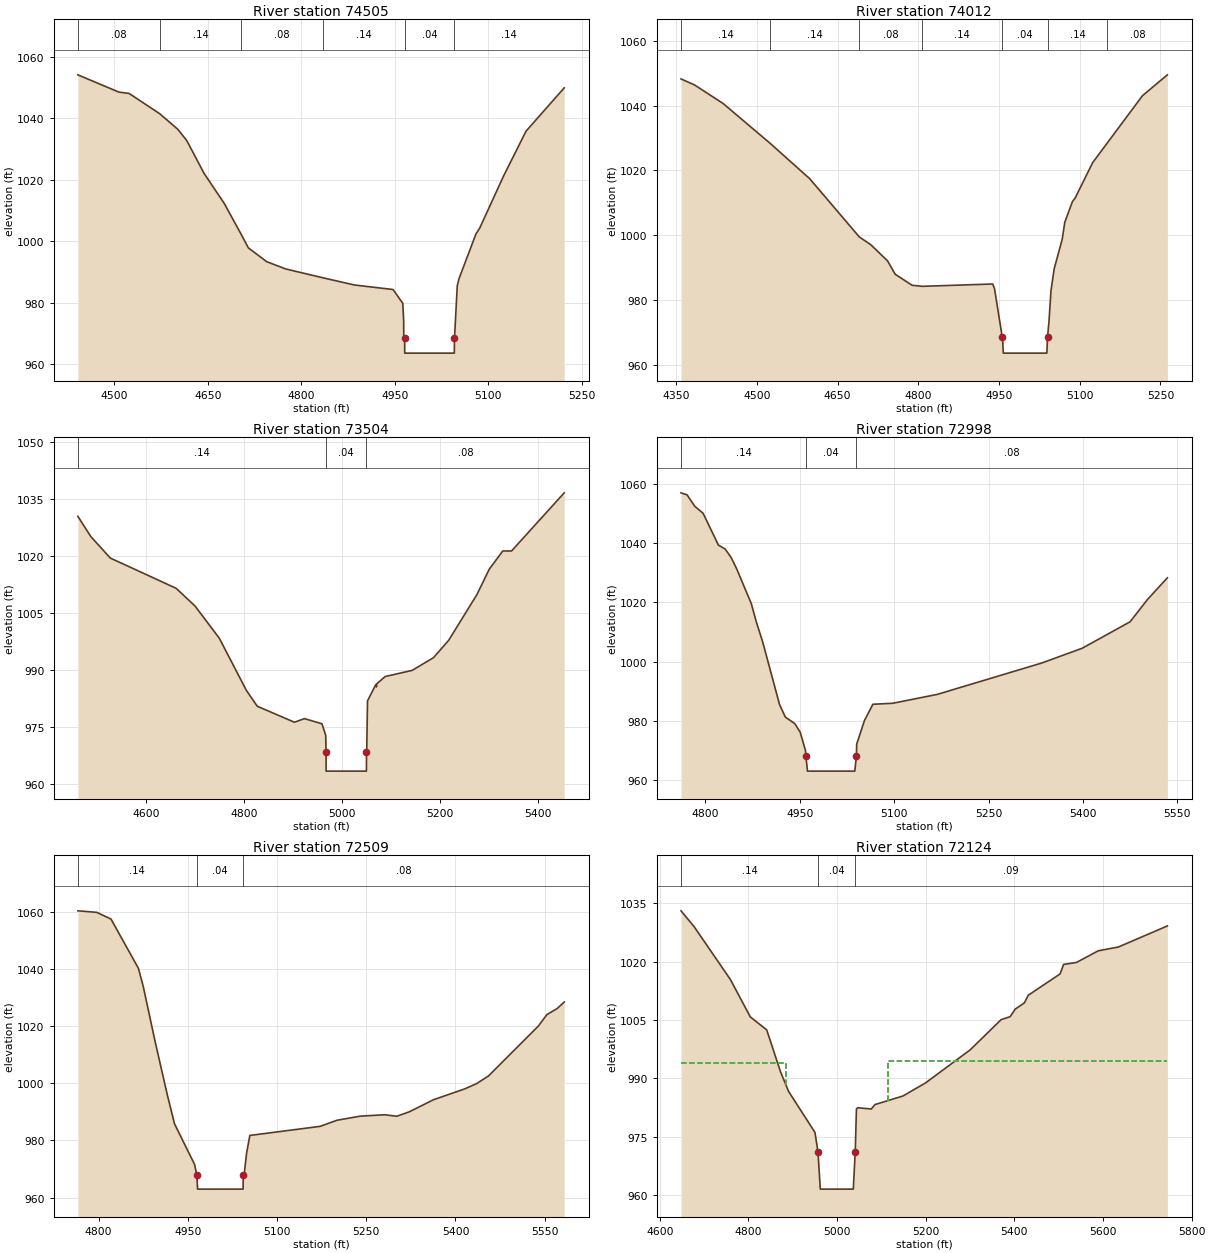
Type RM Length L Ch R = 1,74505,493,493,493
BEGIN DESCRIPTION:
Fisher River 149.0
END DESCRIPTION:
XS GIS Cut Line= 4
      1504532.21       964038.85      1504812.94       963661.30
      1504893.93       963568.20      1504914.60       963382.93
#Sta/Elev= 30
  4441.3 1054.07  4507.2 1048.45  4523.5 1048.02  4572.4 1041.46  4601.6 1036.38
  4616.0 1032.70  4643.9 1021.99  4676.0 1012.31  4703.5 1002.14  4714.8  997.81
  4744.3  993.31  4775.0  990.94  4834.6  988.07  4884.8  985.74  4947.0  984.26
  4962.6  979.77  4964.0  974.20  4964.2  968.58  4965.6  968.58  4965.7  963.58
  5045.3  963.58  5045.4  968.58  5045.6  968.59  5050.0  985.48  5052.9  987.85
  5080.0 1002.33  5086.1 1004.27  5124.4 1021.22  5160.4 1035.77  5221.6 1049.84
#Mann=6,-1,0
  4441.3    0.08       0  4572.4    0.14       0  4703.5    0.08       0
  4834.6    0.14       0  4965.6    0.04       0  5045.4    0.14       0
Bank Sta=4965.6,5045.4
XS Rating Curve= 0
Exp/Cntr=0.3,0.1

Type RM Length L Ch R = 1,74012,508,508,508
BEGIN DESCRIPTION:
Fisher River 148.0
END DESCRIPTION:
XS GIS Cut Line= 4
      1504713.67       964111.47      1505052.55       964111.47
      1505326.03       963828.30      1505287.30       963661.29
#Sta/Elev= 30
  4358.8 1048.29  4383.6 1046.47  4437.0 1040.71  4524.5 1028.38  4598.0 1017.45
  4690.2  999.45  4711.3  997.08  4742.6  992.07  4757.0  987.91  4788.3  984.51
  4807.0  984.18  4938.0  984.90  4941.5  983.49  4954.4  970.06  4955.3  968.55
  4956.3  968.53  4957.9  963.53  5038.8  963.53  5040.1  968.53  5042.8  973.41
  5046.5  982.89  5052.5  989.65  5067.4  998.77  5072.1 1003.96  5086.2 1010.32
  5091.4 1011.48  5123.9 1022.40  5151.5 1028.58  5216.5 1043.11  5262.8 1049.56
#Mann=7,-1,0
  4358.8    0.14       0  4524.5    0.14       0  4690.2    0.08       0
  4807.0    0.14       0  4956.3    0.04       0  5040.1    0.14       0
  5151.5    0.08       0
Bank Sta=4956.3,5040.1
XS Rating Curve= 0
Exp/Cntr=0.3,0.1

Type RM Length L Ch R = 1,73504,506,506,506
BEGIN DESCRIPTION:
Fisher River 147.0
END DESCRIPTION:
XS GIS Cut Line= 5
      1505565.64       964694.78      1505577.74       964469.67
      1505662.45       964215.54      1505725.37       964104.21
      1505647.93       963741.18
#Sta/Elev= 30
  4461.0 1030.41  4487.5 1025.08  4527.2 1019.43  4661.6 1011.46  4700.0 1006.82
  4749.6  998.33  4804.7  984.63  4827.1  980.42  4902.9  976.21  4923.3  977.16
  4959.1  975.81  4966.8  972.72  4967.4  968.34  4967.5  963.34  5049.8  963.34
  5049.9  968.34  5050.4  968.34  5052.0  981.83  5069.0  986.14  5070.2  985.51
  5071.1  986.34  5087.8  988.23  5143.1  989.86  5186.9  993.23  5217.8  997.81
  5275.4 1009.85  5300.4 1016.49  5328.0 1021.30  5345.9 1021.29  5453.4 1036.60
#Mann=3,-1,0
  4461.0    0.14       0  4967.4    0.04       0  5049.9    0.08       0
Bank Sta=4967.4,5049.9
XS Rating Curve= 0
Exp/Cntr=0.3,0.1

Type RM Length L Ch R = 1,72998,489,489,489
BEGIN DESCRIPTION:
Fisher River 146.0
END DESCRIPTION:
XS GIS Cut Line= 3
      1506347.42       964208.29      1506209.42       964167.14
      1505899.64       963620.18
#Sta/Elev= 30
  4761.5 1056.94  4771.1 1056.26  4783.4 1052.40  4796.6 1050.05  4820.9 1039.33
  4831.7 1037.99  4841.1 1035.15  4849.9 1031.36  4873.3 1019.52  4880.8 1013.68
  4891.4 1006.59  4918.0  985.62  4927.2  981.37  4942.3  979.15  4950.8  976.29
  4959.3  970.08  4959.9  968.15  4962.4  963.15  5037.6  963.15  5040.1  968.15
  5040.6  972.26  5052.9  980.19  5066.3  985.68  5097.9  986.02  5168.4  989.00
  5334.5  999.58  5398.8 1004.56  5474.9 1013.48  5502.7 1021.04  5534.1 1028.30
#Mann=3,-1,0
  4761.5    0.14       0  4959.9    0.04       0  5040.1    0.08       0
Bank Sta=4959.9,5040.1
XS Rating Curve= 0
Exp/Cntr=0.3,0.1

Type RM Length L Ch R = 1,72509,385,385,385
BEGIN DESCRIPTION:
Fisher River 145.0
END DESCRIPTION:
XS GIS Cut Line= 3
      1506722.51       963929.95      1506647.49       963854.92
      1506066.64       963443.49
#Sta/Elev= 30
  4765.0 1060.48  4796.8 1059.95  4820.7 1057.60  4866.8 1040.35  4875.0 1033.97
  4895.2 1014.39  4915.7  995.77  4927.5  985.86  4961.2  971.65  4965.0  967.96
  4966.4  962.96  5042.9  962.96  5043.0  967.84  5044.6  967.96  5048.7  975.48
  5054.2  981.77  5172.5  984.96  5200.7  987.09  5240.5  988.55  5281.0  989.02
  5301.3  988.50  5322.1  990.03  5363.0  994.28  5415.4  998.07  5435.5  999.92
  5455.5 1002.61  5539.4 1020.11  5553.8 1024.13  5570.9 1026.22  5582.9 1028.52
#Mann=3,-1,0
  4765.0    0.14       0  4965.0    0.04       0  5043.0    0.08       0
Bank Sta=4965,5043
XS Rating Curve= 0
Exp/Cntr=0.5,0.3

Type RM Length L Ch R = 1,72124,173,173,173
BEGIN DESCRIPTION:
Turkey Ford Rd - US
END DESCRIPTION:
XS GIS Cut Line= 5
      1506860.47       963772.64      1506920.97       963598.38
      1506538.58       963269.23      1506383.68       963177.26
      1506156.17       963160.31
#Sta/Elev= 30
  4647.9 1033.11  4677.2 1029.08  4759.1 1015.48  4804.3 1005.81  4841.3 1002.47
  4872.4  991.69  4890.6  986.64  4950.1  976.11  4956.9  971.10  4962.2  961.50
  5036.6  961.50  5041.0  971.10  5043.7  982.11  5046.3  982.44  5077.3  982.12
  5085.5  983.26  5148.8  985.47  5200.0  988.86  5300.0  997.31  5370.1 1005.11
  5390.5 1005.87  5401.8 1007.81  5422.5 1009.42  5431.3 1011.39  5503.2 1016.88
  5511.1 1019.32  5540.2 1019.83  5589.2 1022.82  5634.6 1023.80  5745.2 1029.22
#Mann=3,-1,0
  4647.9    0.14       0  4956.9    0.04       0  5041.0    0.09       0
#XS Ineff=2,0
    0.00 4885.00  994.00 5115.00    0.00  994.50
Permanent Ineff=
       F       F
Bank Sta=4956.9,5041
XS Rating Curve= 0
Exp/Cntr=0.5,0.3

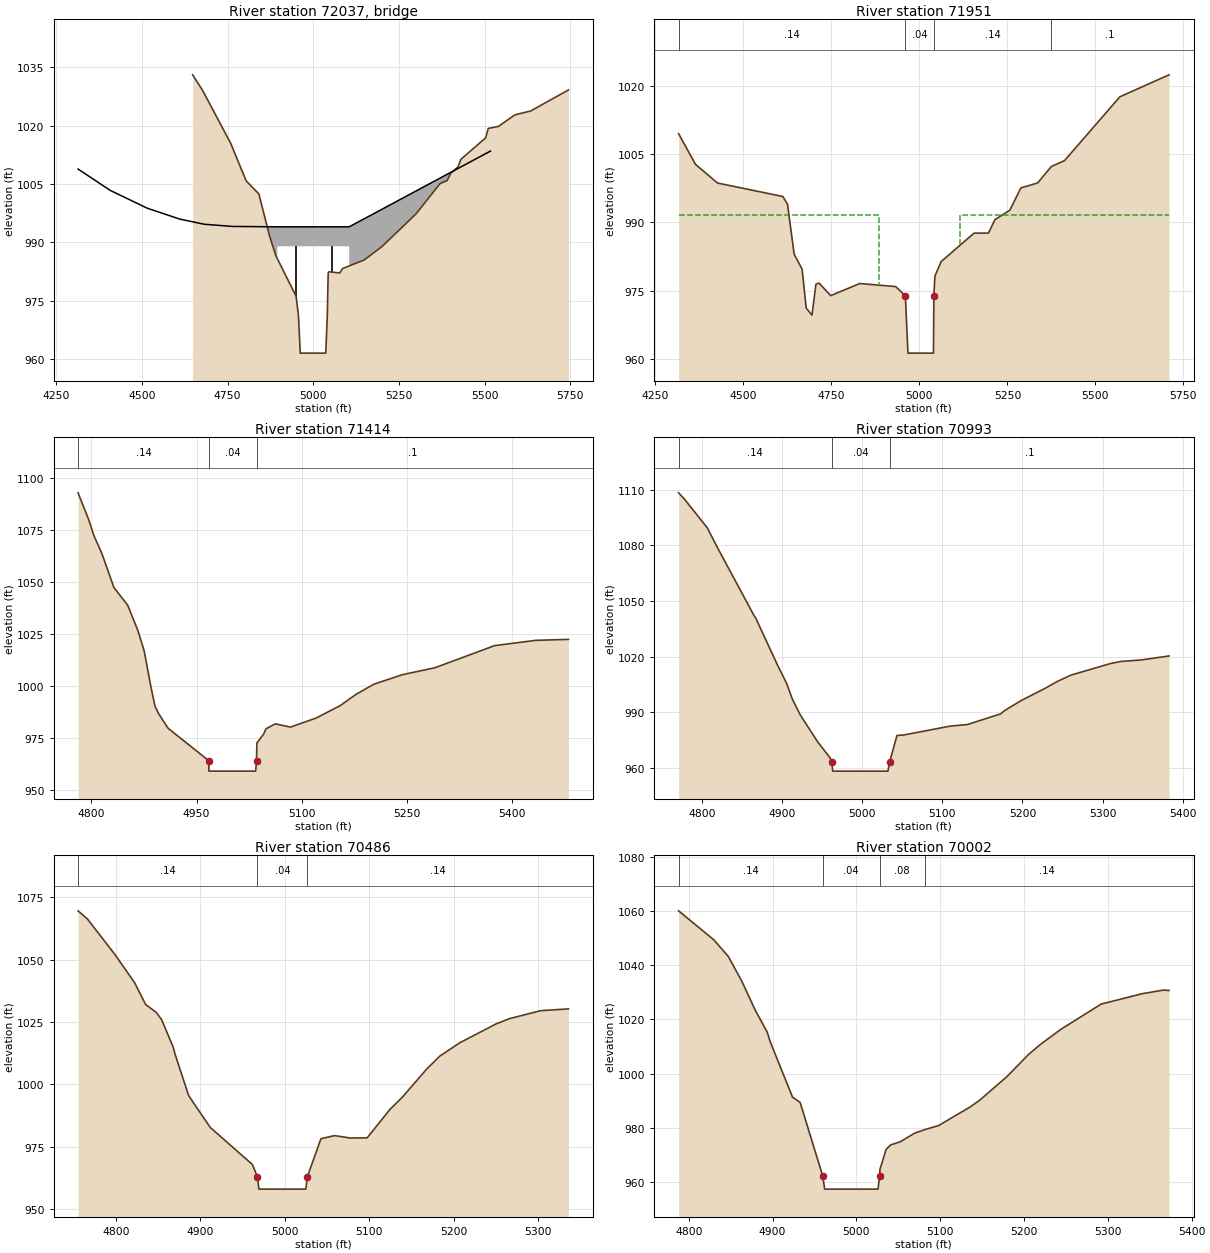
Type RM Length L Ch R =3,72037,,,
BEGIN DESCRIPTION:
Turkey Ford Rd - TOR
Structure ID: LDS_FR_06
Approximate Survey Structure
END DESCRIPTION:
Bridge Culvert--1,0,-1,-1,0
Deck Dist Width WeirC Skew NumUp NumDn MinLoCord MaxHiCord MaxSubmerge Is_Ogee
71,32,3,,11,11,,,0.95,0,1,1,,,
  4313.5  4407.1  4515.7  4610.4  4682.0  4764.3  4895.0  4895.0  5105.0  5105.0
  5517.4
 1008.87 1003.39  998.78  995.99  994.66  994.10  994.00  994.00  994.00  994.00
 1013.49
  941.50  941.50  941.50  941.50  941.50  941.50  941.50  989.00  989.00  941.50
  941.50
  4313.5  4407.1  4515.7  4610.4  4682.0  4764.3  4895.0  4895.0  5105.0  5105.0
  5517.4
 1008.87 1003.39  998.78  995.99  994.66  994.10  994.00  994.00  994.00  994.00
 1013.49
  941.50  941.50  941.50  941.50  941.50  941.50  941.50  989.00  989.00  941.50
  941.50
Pier Skew, UpSta & Num, DnSta & Num=,4947.5,2,4947.5,2,0,0,0,0,0
       3       3
  977.28  989.00
       3       3
  980.02  989.00
Pier Skew, UpSta & Num, DnSta & Num=,5052.5,2,5052.5,2,0,0,0,0,0
       3       3
  982.55  989.00
       3       3
  979.56  989.00
Abutment Skew #Up #Dn=,2,2
  4895.0  4915.0
  989.00  981.80
  4895.0  4915.0
  989.00  975.75
Abutment Skew #Up #Dn=,2,2
  5085.0  5105.0
  983.19  989.00
  5085.0  5105.0
  982.97  989.00
BR Coef=1,1,0,1.25,0,,,0.8,0,2,0,
WSPro=,,,, 1 ,,,, 0 ,,,, 0 ,,,,-1 ,-1 ,-1 , 0 , 0 , 0 , 0 , 0
BC Design=,,0,,0,,,,,,

Type RM Length L Ch R = 1,71951,537,537,537
BEGIN DESCRIPTION:
Turkey Ford Rd - DS
END DESCRIPTION:
XS GIS Cut Line= 6
      1507431.64       963792.00      1507143.64       963564.49
      1506993.58       963433.80      1506649.91       963138.53
      1506415.14       963024.78      1506306.27       962993.33
#Sta/Elev= 30
  4315.8 1009.47  4363.8 1002.72  4426.3  998.62  4612.0  995.66  4625.2  993.96
  4644.2  982.96  4666.7  979.71  4678.3  971.16  4694.7  969.59  4706.0  976.40
  4715.0  976.63  4747.8  973.88  4830.5  976.54  4932.5  975.87  4960.0  973.85
  4967.4  961.25  5039.9  961.25  5041.0  973.85  5044.0  978.16  5061.6  981.36
  5155.3  987.61  5196.1  987.62  5214.4  990.57  5257.0  992.66  5288.2  997.55
  5335.8  998.63  5374.6 1002.24  5412.3 1003.55  5569.4 1017.56  5709.1 1022.39
#Mann=4,-1,0
  4315.8    0.14       0  4960.0    0.04       0  5041.0    0.14       0
  5374.6     0.1       0
#XS Ineff=2,0
    0.00 4885.00  991.50 5115.00    0.00  991.50
Permanent Ineff=
       F       F
Bank Sta=4960,5041
XS Rating Curve= 0
Exp/Cntr=0.5,0.3

Type RM Length L Ch R = 1,71414,421,421,421
BEGIN DESCRIPTION:
Fisher River 143.0
END DESCRIPTION:
XS GIS Cut Line= 3
      1506964.52       962782.77      1506567.62       962964.27
      1506306.20       962990.90
#Sta/Elev= 30
  4781.0 1092.93  4795.6 1080.56  4803.7 1072.29  4815.0 1063.74  4832.1 1047.44
  4851.8 1038.89  4866.4 1026.63  4875.2 1017.00  4885.1  999.28  4890.7  990.36
  4895.6  986.92  4909.3  979.77  4967.4  964.14  4967.5  959.14  5034.2  959.14
  5035.4  964.14  5036.0  972.69  5045.7  977.03  5048.9  979.48  5062.2  981.87
  5083.7  980.30  5120.0  984.60  5155.0  990.69  5177.2  996.03  5202.6 1000.90
  5243.4 1005.50  5289.6 1008.82  5374.8 1019.47  5433.3 1022.00  5480.2 1022.48
#Mann=3,-1,0
  4781.0    0.14       0  4967.4    0.04       0  5035.4     0.1       0
Bank Sta=4967.4,5035.4
XS Rating Curve= 0
Exp/Cntr=0.3,0.1

Type RM Length L Ch R = 1,70993,507,507,507
BEGIN DESCRIPTION:
Fisher River 142.0
END DESCRIPTION:
XS GIS Cut Line= 4
      1506662.00       962419.73      1506524.05       962531.05
      1506441.77       962601.24      1506175.52       962790.03
#Sta/Elev= 30
  4771.1 1108.29  4777.8 1105.19  4806.8 1089.50  4821.0 1077.61  4865.0 1042.28
  4867.0 1041.06  4895.2 1014.79  4905.8 1005.63  4912.9  997.18  4922.8  988.60
  4944.8  973.89  4959.8  965.58  4962.1  963.25  4963.4  958.25  5032.2  958.25
  5034.4  963.25  5043.5  977.47  5051.8  977.73  5110.2  982.54  5131.5  983.38
  5172.6  989.08  5178.2  991.01  5197.5  996.09  5228.5 1002.93  5242.8 1006.44
  5260.6 1010.02  5310.0 1016.27  5323.2 1017.38  5349.0 1018.23  5382.9 1020.34
#Mann=3,-1,0
  4771.1    0.14       0  4962.1    0.04       0  5034.4     0.1       0
Bank Sta=4962.1,5034.4
XS Rating Curve= 0
Exp/Cntr=0.3,0.1

Type RM Length L Ch R = 1,70486,484,484,484
BEGIN DESCRIPTION:
Fisher River 141.0
END DESCRIPTION:
XS GIS Cut Line= 3
      1506354.65       962044.57      1506248.15       962119.61
      1505880.24       962378.59
#Sta/Elev= 30
  4755.4 1069.63  4766.6 1066.32  4799.3 1051.99  4822.3 1040.78  4835.3 1032.08
  4847.9 1028.87  4854.2 1026.00  4868.1 1014.80  4870.0 1012.27  4886.1  995.62
  4891.4  992.86  4911.8  982.70  4961.7  967.81  4967.5  962.95  4969.4  957.95
  5024.8  957.95  5026.7  962.95  5042.7  978.17  5058.8  979.43  5077.4  978.46
  5097.4  978.53  5124.6  990.02  5139.0  994.84  5167.7 1006.07  5183.4 1011.34
  5207.1 1016.71  5250.1 1024.28  5265.8 1026.36  5302.7 1029.57  5335.6 1030.27
#Mann=3,-1,0
  4755.4    0.14       0  4967.5    0.04       0  5026.7    0.14       0
Bank Sta=4967.5,5026.7
XS Rating Curve= 0
Exp/Cntr=0.3,0.1

Type RM Length L Ch R = 1,70002,499,499,499
BEGIN DESCRIPTION:
Fisher River 140.0
END DESCRIPTION:
XS GIS Cut Line= 3
      1505718.11       961807.42      1505722.95       961945.35
      1505873.02       962366.50
#Sta/Elev= 30
  4787.9 1060.02  4829.9 1049.34  4847.2 1043.21  4863.4 1034.03  4879.7 1023.18
  4893.6 1015.33  4897.3 1011.71  4923.8  991.36  4932.9  989.41  4959.7  962.44
  4962.2  957.44  5025.8  957.44  5027.8  962.44  5028.1  964.73  5035.5  972.12
  5041.1  973.76  5052.3  974.89  5069.3  978.03  5081.5  979.36  5098.2  980.88
  5135.1  987.62  5146.7  990.10  5180.0  999.03  5205.2 1007.02  5219.6 1010.79
  5243.9 1016.33  5291.9 1025.63  5341.4 1029.50  5365.8 1030.78  5373.0 1030.70
#Mann=4,-1,0
  4787.9    0.14       0  4959.7    0.04       0  5027.8    0.08       0
  5081.5    0.14       0
Bank Sta=4959.7,5027.8
XS Rating Curve= 0
Exp/Cntr=0.3,0.1

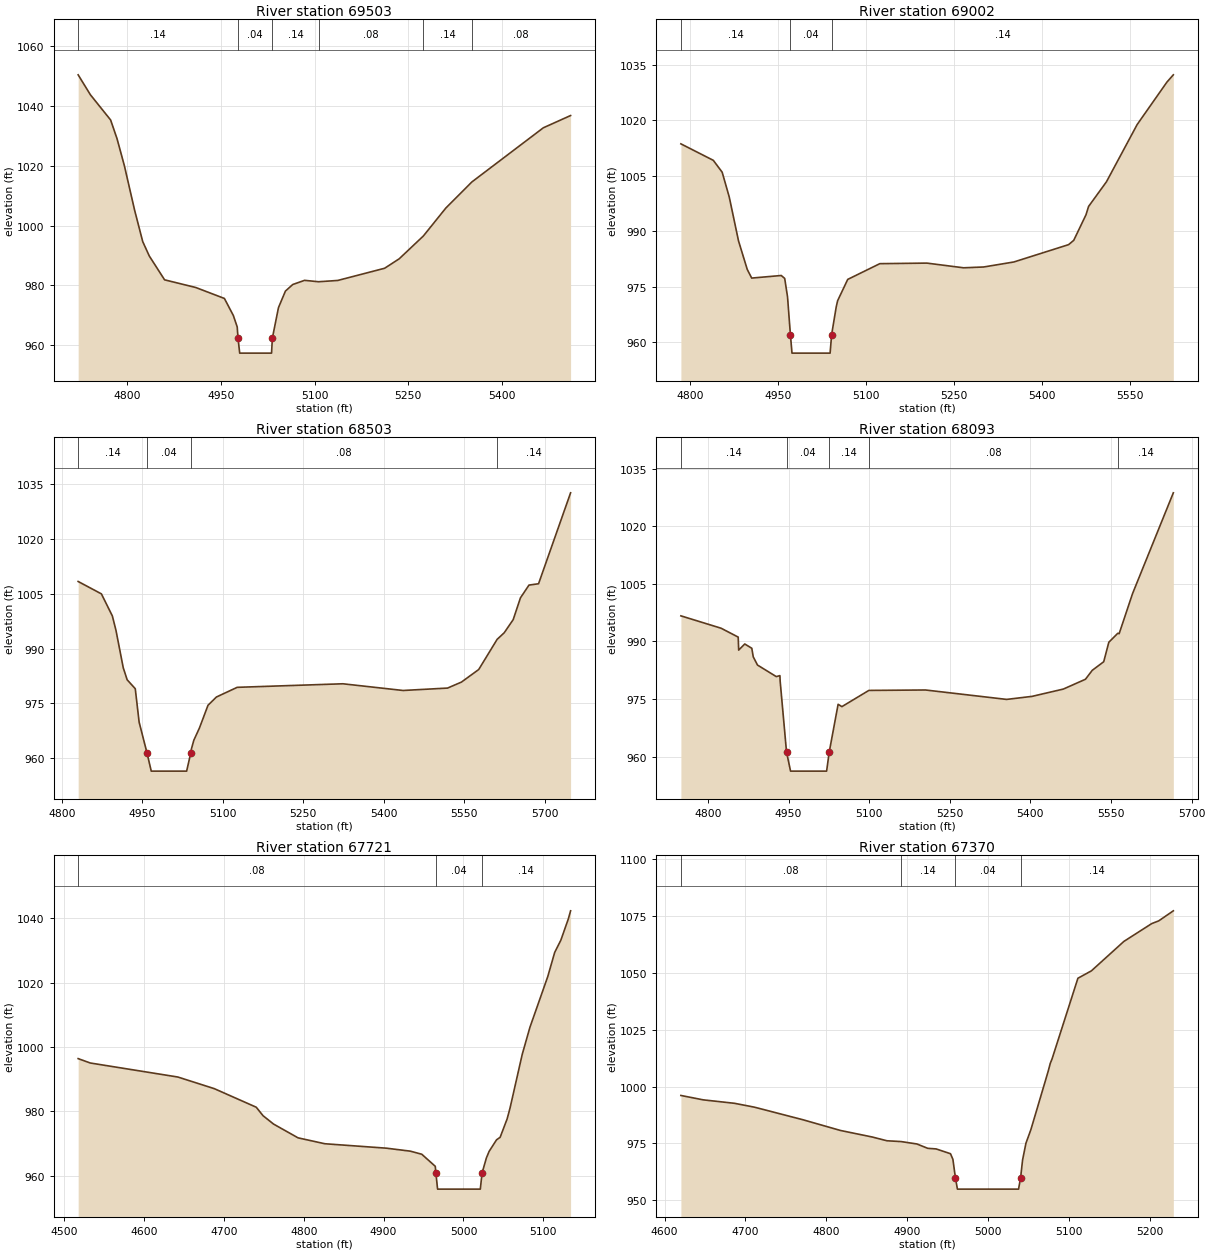
Type RM Length L Ch R = 1,69503,501,501,501
BEGIN DESCRIPTION:
Fisher River 139.0
END DESCRIPTION:
XS GIS Cut Line= 4
      1505306.68       961819.46      1505258.27       962044.58
      1505253.43       962182.54      1505456.71       962550.39
#Sta/Elev= 30
  4721.3 1050.45  4740.8 1043.81  4773.3 1035.34  4783.5 1029.12  4795.3 1020.06
  4811.8 1005.09  4824.7  994.66  4835.2  989.85  4859.7  981.87  4909.7  979.30
  4955.5  975.64  4969.8  969.94  4976.0  966.12  4977.3  962.35  4980.0  957.35
  5031.0  957.35  5032.3  962.35  5042.1  972.57  5053.2  978.10  5065.0  980.31
  5083.9  981.70  5106.2  981.23  5137.0  981.66  5212.1  985.74  5235.4  988.90
  5274.1  996.53  5310.1 1005.88  5351.9 1014.63  5466.3 1032.74  5509.9 1036.83
#Mann=6,-1,0
  4721.3    0.14       0  4977.3    0.04       0  5032.3    0.14       0
  5106.2    0.08       0  5274.1    0.14       0  5351.9    0.08       0
Bank Sta=4977.3,5032.3
XS Rating Curve= 0
Exp/Cntr=0.3,0.1

Type RM Length L Ch R = 1,69002,499,499,499
BEGIN DESCRIPTION:
Fisher River 138.0
END DESCRIPTION:
XS GIS Cut Line= 3
      1504769.38       961826.74      1504754.86       962158.33
      1504919.44       962637.55
#Sta/Elev= 30
  4785.0 1013.63  4840.2 1009.17  4855.3 1005.96  4867.4  999.22  4883.1  987.40
  4898.0  979.66  4905.6  977.32  4955.9  978.02  4961.8  977.22  4966.6  972.24
  4971.5  962.02  4974.2  957.02  5039.1  957.02  5041.7  962.02  5049.5  969.51
  5051.9  971.19  5069.1  976.96  5123.8  981.22  5203.9  981.37  5266.4  980.10
  5300.6  980.32  5351.9  981.67  5445.2  986.36  5454.0  987.53  5474.9  994.45
  5479.3  996.70  5509.7 1003.36  5562.0 1018.85  5612.7 1030.33  5623.6 1032.30
#Mann=3,-1,0
  4785.0    0.14       0  4971.5    0.04       0  5041.7    0.14       0
Bank Sta=4971.5,5041.7
XS Rating Curve= 0
Exp/Cntr=0.3,0.1

Type RM Length L Ch R = 1,68503,410,410,410
BEGIN DESCRIPTION:
Fisher River 137.0
END DESCRIPTION:
XS GIS Cut Line= 3
      1504171.55       961916.28      1504229.66       961991.34
      1504602.36       962724.63
#Sta/Elev= 30
  4830.4 1008.30  4873.7 1004.92  4894.1  998.90  4900.9  994.93  4914.4  984.76
  4921.7  981.47  4936.8  979.03  4944.0  969.91  4958.6  961.54  4966.6  956.54
  5032.5  956.54  5040.3  961.54  5041.2  962.49  5045.9  964.96  5056.5  968.36
  5072.3  974.51  5088.0  976.77  5126.7  979.41  5323.6  980.38  5435.8  978.55
  5518.7  979.21  5544.5  980.84  5576.7  984.27  5611.0  992.50  5624.2  994.30
  5641.0  997.90  5654.5 1003.84  5670.4 1007.32  5688.2 1007.68  5747.9 1032.50
#Mann=4,-1,0
  4830.4    0.14       0  4958.6    0.04       0  5040.3    0.08       0
  5611.0    0.14       0
Bank Sta=4958.6,5040.3
XS Rating Curve= 0
Exp/Cntr=0.3,0.1

Type RM Length L Ch R = 1,68093,372,372,372
BEGIN DESCRIPTION:
Fisher River 136.0
END DESCRIPTION:
XS GIS Cut Line= 4
      1503985.20       962119.65      1503902.93       962276.92
      1504357.94       962669.00      1504408.76       962797.28
#Sta/Elev= 30
  4749.8  996.67  4824.6  993.45  4856.4  991.14  4857.3  987.76  4868.6  989.35
  4881.7  988.24  4884.4  986.01  4892.3  983.87  4927.3  980.86  4934.0  981.12
  4934.5  979.64  4946.3  961.27  4953.8  956.27  5020.9  956.27  5025.8  961.27
  5042.3  973.66  5049.3  973.05  5099.5  977.27  5204.8  977.38  5355.8  974.93
  5403.1  975.72  5461.3  977.62  5502.4  980.17  5515.1  982.50  5536.4  984.73
  5545.9  989.80  5562.6  992.14  5565.1  992.03  5590.1 1002.48  5665.9 1028.68
#Mann=5,-1,0
  4749.8    0.14       0  4946.3    0.04       0  5025.8    0.14       0
  5099.5    0.08       0  5562.6    0.14       0
Bank Sta=4946.3,5025.8
XS Rating Curve= 0
Exp/Cntr=0.3,0.1

Type RM Length L Ch R = 1,67721,351,351,351
BEGIN DESCRIPTION:
Fisher River 135.5
END DESCRIPTION:
XS GIS Cut Line= 3
      1503968.30       962107.47      1503622.18       962516.53
      1503554.42       962560.09
#Sta/Elev= 30
  4517.7  996.43  4532.8  995.07  4642.6  990.70  4688.1  987.09  4740.6  981.32
  4749.2  978.66  4762.4  976.06  4793.0  971.79  4826.5  969.96  4903.6  968.58
  4933.4  967.66  4947.8  966.70  4964.7  962.95  4965.5  960.85  4967.6  955.85
  5021.1  955.85  5023.3  960.85  5028.7  965.55  5032.1  967.58  5041.4  971.18
  5045.9  971.96  5054.7  977.71  5058.3  981.06  5073.6  997.79  5083.2 1006.17
  5105.5 1021.92  5114.2 1029.45  5121.9 1033.25  5131.3 1039.89  5134.1 1042.38
#Mann=3,-1,0
  4517.7    0.08       0  4965.5    0.04       0  5023.3    0.14       0
Bank Sta=4965.5,5023.3
XS Rating Curve= 0
Exp/Cntr=0.3,0.1

Type RM Length L Ch R = 1,67370,356,356,356
BEGIN DESCRIPTION:
Fisher River 135.0
END DESCRIPTION:
XS GIS Cut Line= 4
      1503961.04       962100.24      1503685.11       962160.75
      1503472.13       962148.65      1503397.08       962063.93
#Sta/Elev= 30
  4620.2  996.09  4647.8  994.16  4686.5  992.64  4711.3  990.93  4771.4  985.39
  4817.6  980.70  4857.0  977.82  4875.0  976.18  4892.6  975.82  4912.1  974.77
  4925.5  972.86  4935.8  972.60  4953.6  970.50  4956.6  968.02  4959.7  959.93
  4962.2  954.93  5037.8  954.93  5040.3  959.93  5042.8  967.81  5046.9  975.07
  5053.1  981.14  5074.4 1006.67  5077.0 1010.18  5079.3 1012.23  5111.2 1047.59
  5127.9 1050.85  5168.1 1063.79  5202.5 1071.61  5211.2 1072.82  5229.2 1077.22
#Mann=4,-1,0
  4620.2    0.08       0  4892.6    0.14       0  4959.7    0.04       0
  5040.3    0.14       0
Bank Sta=4959.7,5040.3
XS Rating Curve= 0
Exp/Cntr=0.3,0.1

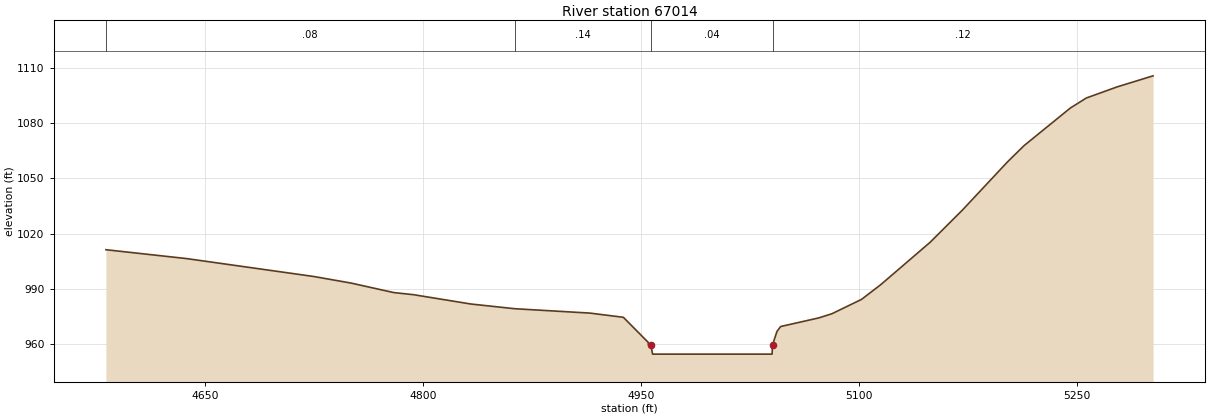
Type RM Length L Ch R = 1,67014,511,511,511
BEGIN DESCRIPTION:
Fisher River 134.0
END DESCRIPTION:
XS GIS Cut Line= 3
      1504042.36       961842.83      1503561.67       961795.54
      1503334.16       961863.31
#Sta/Elev= 30
  4581.7 1011.35  4637.2 1006.54  4724.6  996.84  4750.3  993.27  4779.7  988.11
  4793.4  986.95  4832.8  981.90  4862.9  979.35  4914.8  976.97  4937.7  974.69
  4954.8  961.09  4954.9  959.73  4956.6  959.72  4957.8  954.72  5040.0  954.72
  5040.3  959.72  5043.4  967.07  5045.9  969.69  5072.1  974.36  5081.2  976.64
  5101.5  984.39  5114.7  992.35  5148.7 1015.36  5170.9 1032.81  5202.0 1059.02
  5213.4 1067.84  5245.2 1088.21  5256.2 1093.64  5277.4 1099.67  5302.1 1105.67
#Mann=4,-1,0
  4581.7    0.08       0  4862.9    0.14       0  4956.6    0.04       0
  5040.3    0.12       0
Bank Sta=4956.6,5040.3
XS Rating Curve= 0
Exp/Cntr=0.3,0.1