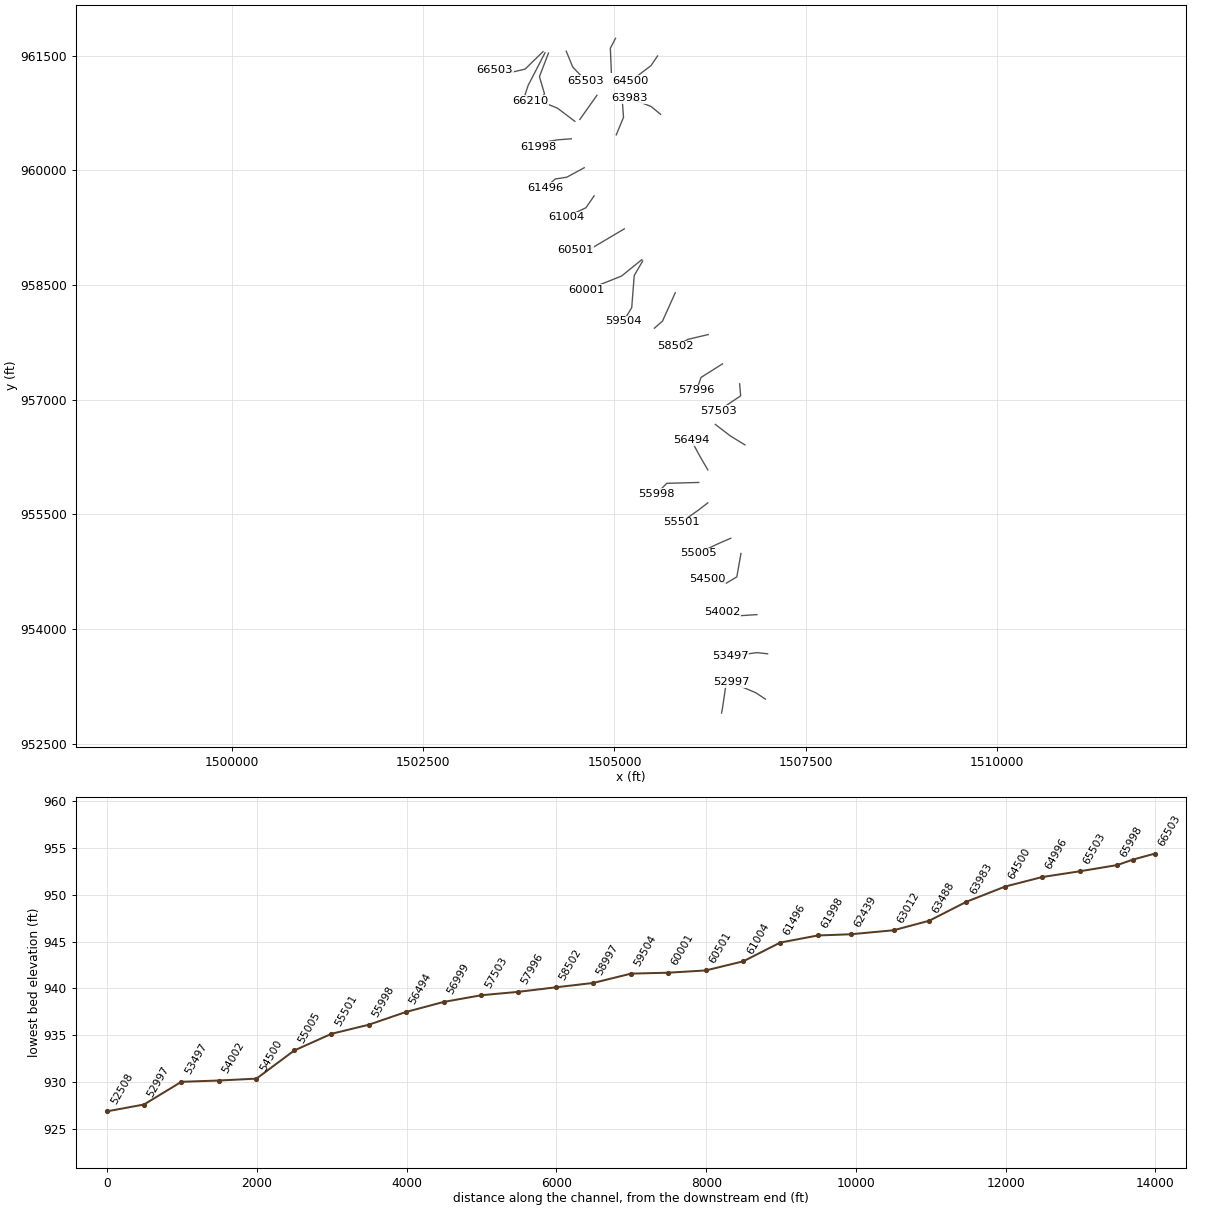
HEC-RAS study Fisher River.prj: Fisher River Limited Detail Study

--- Fisher River.g01 (geometry) --- (continued)

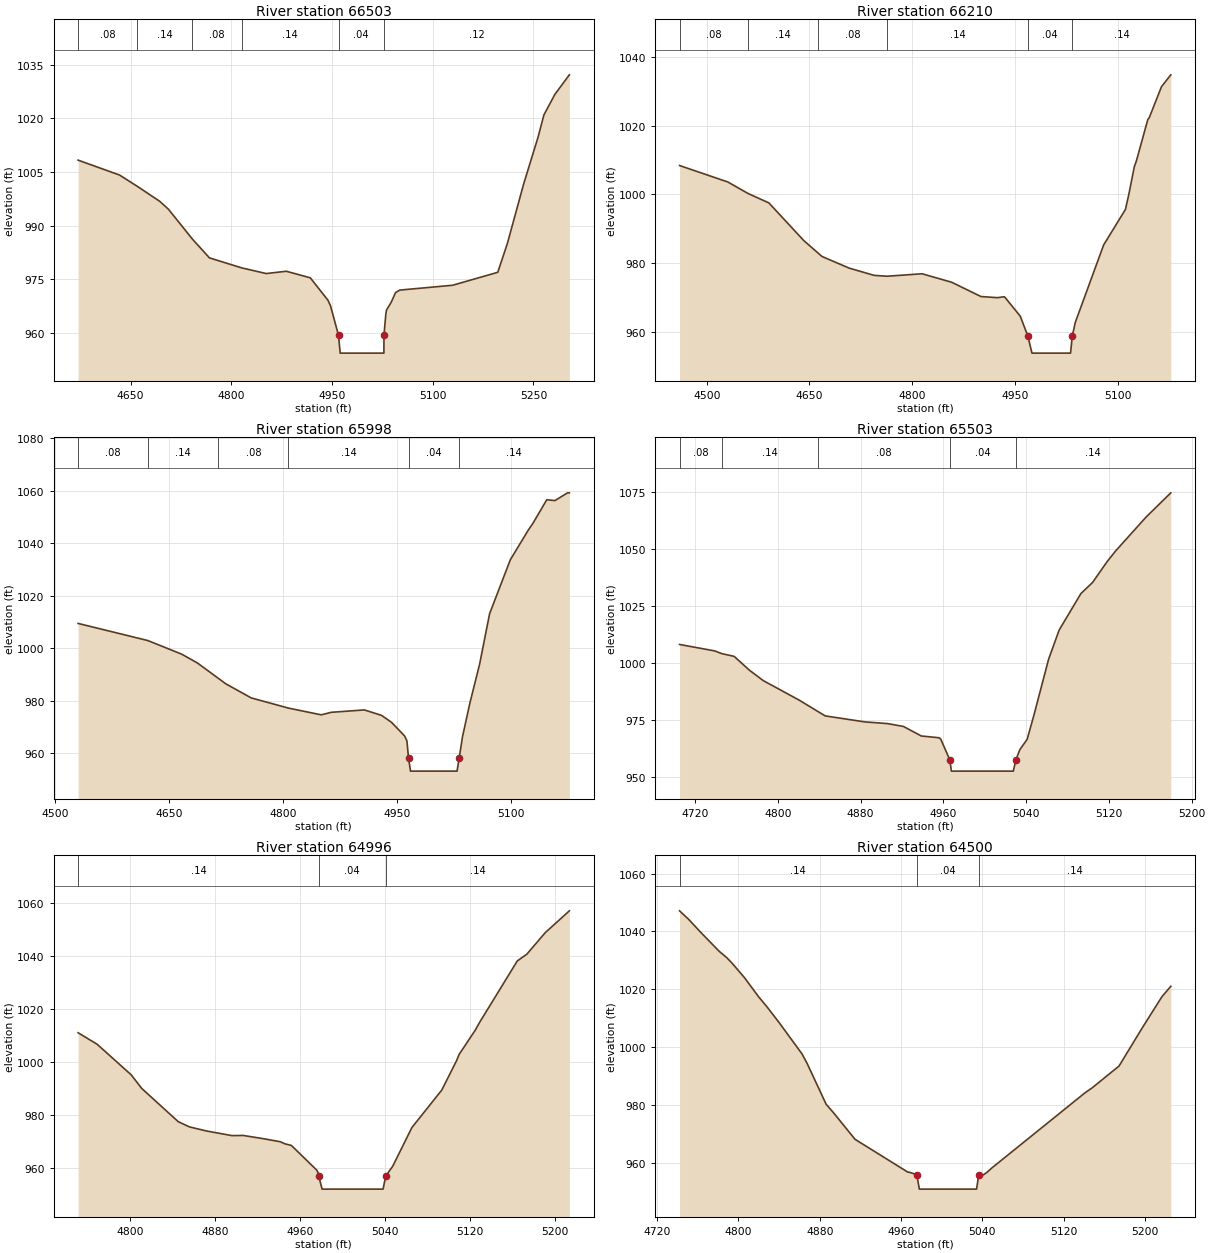
Type RM Length L Ch R = 1,66503,293,293,293
BEGIN DESCRIPTION:
Fisher River 133.0
END DESCRIPTION:
XS GIS Cut Line= 4
      1504065.57       961554.34      1503831.29       961325.87
      1503651.22       961283.27      1503434.38       961316.18
#Sta/Elev= 30
  4571.9 1008.30  4633.8 1004.12  4659.9 1001.00  4693.5  996.80  4706.4  994.60
  4742.1  986.26  4767.5  981.01  4815.6  978.21  4852.1  976.63  4882.0  977.27
  4917.7  975.44  4944.0  969.18  4947.8  967.61  4959.7  959.41  4962.2  954.41
  5027.3  954.41  5027.4  959.41  5030.2  965.39  5031.3  966.49  5038.0  968.54
  5044.7  971.33  5050.9  972.01  5129.6  973.36  5196.9  976.98  5211.3  985.10
  5235.5 1001.70  5256.9 1014.73  5265.6 1020.93  5281.9 1026.66  5303.5 1032.12
#Mann=6,-1,0
  4571.9    0.08       0  4659.9    0.14       0  4742.1    0.08       0
  4815.6    0.14       0  4959.7    0.04       0  5027.4    0.12       0
Bank Sta=4959.7,5027.4
XS Rating Curve= 0
Exp/Cntr=0.3,0.1

Type RM Length L Ch R = 1,66210,212,212,212
BEGIN DESCRIPTION:
Fisher River 132.5
END DESCRIPTION:
XS GIS Cut Line= 4
      1504091.72       961539.01      1503871.47       961113.03
      1503830.32       960989.60      1503905.84       960912.48
#Sta/Elev= 30
  4460.2 1008.40  4530.8 1003.60  4560.2 1000.26  4590.7  997.51  4641.8  986.52
  4663.0  982.83  4668.2  981.92  4708.0  978.52  4744.5  976.41  4763.3  976.16
  4814.5  976.88  4857.7  974.41  4900.5  970.25  4924.4  969.92  4934.8  970.19
  4957.9  964.53  4968.9  958.77  4975.0  953.77  5031.3  953.77  5033.9  958.77
  5038.3  962.74  5079.7  985.27  5111.5  995.61  5116.3  999.85  5124.5 1008.05
  5127.6 1009.79  5144.2 1021.80  5146.3 1022.33  5164.2 1031.37  5177.8 1034.81
#Mann=6,-1,0
  4460.2    0.08       0  4560.2    0.14       0  4663.0    0.08       0
  4763.3    0.14       0  4968.9    0.04       0  5033.9    0.14       0
Bank Sta=4968.9,5033.9
XS Rating Curve= 0
Exp/Cntr=0.3,0.1

Type RM Length L Ch R = 1,65998,495,495,495
BEGIN DESCRIPTION:
Fisher River 132.0
END DESCRIPTION:
XS GIS Cut Line= 4
      1504137.22       961535.01      1504019.10       961227.12
      1504084.93       961004.46      1504044.28       960930.90
#Sta/Elev= 30
  4530.5 1009.41  4622.2 1002.89  4666.8  997.70  4687.2  994.39  4715.1  988.47
  4724.9  986.39  4758.1  981.06  4807.0  977.18  4850.2  974.61  4863.4  975.57
  4906.9  976.48  4929.6  974.40  4942.6  971.77  4959.8  966.59  4962.9  964.67
  4965.0  958.18  4967.6  953.18  5028.8  953.18  5031.6  958.18  5036.0  966.33
  5045.8  979.24  5058.5  993.93  5071.6 1013.09  5098.9 1033.67  5122.3 1044.85
  5128.5 1047.47  5146.8 1056.50  5157.5 1056.17  5174.0 1059.11  5176.5 1059.13
#Mann=6,-1,0
  4530.5    0.08       0  4622.2    0.14       0  4715.1    0.08       0
  4807.0    0.14       0  4965.0    0.04       0  5031.6    0.14       0
Bank Sta=4965,5031.6
XS Rating Curve= 0
Exp/Cntr=0.3,0.1

Type RM Length L Ch R = 1,65503,507,507,507
BEGIN DESCRIPTION:
Fisher River 131.0
END DESCRIPTION:
XS GIS Cut Line= 3
      1504369.55       961560.15      1504454.74       961352.97
      1504627.10       961170.94
#Sta/Elev= 30
  4705.1 1008.19  4739.1 1005.36  4746.0 1004.15  4757.9 1002.95  4772.6  996.88
  4785.9  992.33  4820.8  983.70  4838.5  978.81  4845.8  976.80  4884.1  974.16
  4906.0  973.42  4921.5  972.15  4938.7  967.97  4956.1  967.17  4957.6  966.48
  4966.2  957.52  4967.8  952.52  5027.6  952.52  5030.1  957.52  5033.9  961.94
  5041.0  966.52  5047.4  976.92  5061.7 1001.69  5071.9 1014.52  5092.9 1030.55
  5104.2 1035.45  5118.1 1044.50  5126.4 1049.26  5155.9 1064.19  5179.8 1074.84
#Mann=5,-1,0
  4705.1    0.08       0  4746.0    0.14       0  4838.5    0.08       0
  4966.2    0.04       0  5030.1    0.14       0
Bank Sta=4966.2,5030.1
XS Rating Curve= 0
Exp/Cntr=0.3,0.1

Type RM Length L Ch R = 1,64996,496,496,496
BEGIN DESCRIPTION:
Fisher River 130.0
END DESCRIPTION:
XS GIS Cut Line= 3
      1505014.32       961728.62      1504946.54       961598.87
      1504960.09       961283.25
#Sta/Elev= 30
  4751.1 1011.01  4769.1 1006.63  4801.1  995.09  4811.0  989.95  4845.3  977.41
  4855.9  975.42  4872.2  973.85  4895.9  972.13  4906.5  972.19  4926.6  970.89
  4941.4  969.81  4945.4  969.06  4951.8  968.41  4975.6  959.12  4977.2  957.92
  4977.5  956.90  4980.7  951.90  5038.1  951.90  5040.6  956.90  5047.1  960.50
  5065.2  975.17  5093.3  989.33  5107.2 1000.41  5109.7 1002.84  5124.8 1011.96
  5128.9 1014.90  5164.4 1038.15  5173.4 1040.71  5190.7 1048.84  5213.4 1057.09
#Mann=3,-1,0
  4751.1    0.14       0  4977.5    0.04       0  5040.6    0.14       0
Bank Sta=4977.5,5040.6
XS Rating Curve= 0
Exp/Cntr=0.3,0.1

Type RM Length L Ch R = 1,64500,517,517,517
BEGIN DESCRIPTION:
Fisher River 129.0
END DESCRIPTION:
XS GIS Cut Line= 3
      1505564.18       961498.18      1505478.99       961372.33
      1505215.64       961170.95
#Sta/Elev= 30
  4742.0 1047.12  4750.9 1044.20  4762.1 1039.96  4780.9 1033.16  4788.3 1030.98
  4793.8 1028.98  4806.0 1023.97  4819.8 1017.40  4827.9 1013.99  4839.8 1008.57
  4862.5  997.65  4867.5  994.39  4886.3  980.22  4894.0  977.10  4914.7  968.11
  4966.8  956.73  4968.0  956.74  4975.5  955.88  4978.0  950.88  5034.3  950.88
  5036.5  955.88  5041.3  955.88  5044.8  956.75  5049.5  958.24  5141.1  984.20
  5148.3  985.97  5174.5  993.43  5197.5 1006.70  5216.8 1017.45  5225.5 1021.03
#Mann=3,-1,0
  4742.0    0.14       0  4975.5    0.04       0  5036.5    0.14       0
Bank Sta=4975.5,5036.5
XS Rating Curve= 0
Exp/Cntr=0.3,0.1

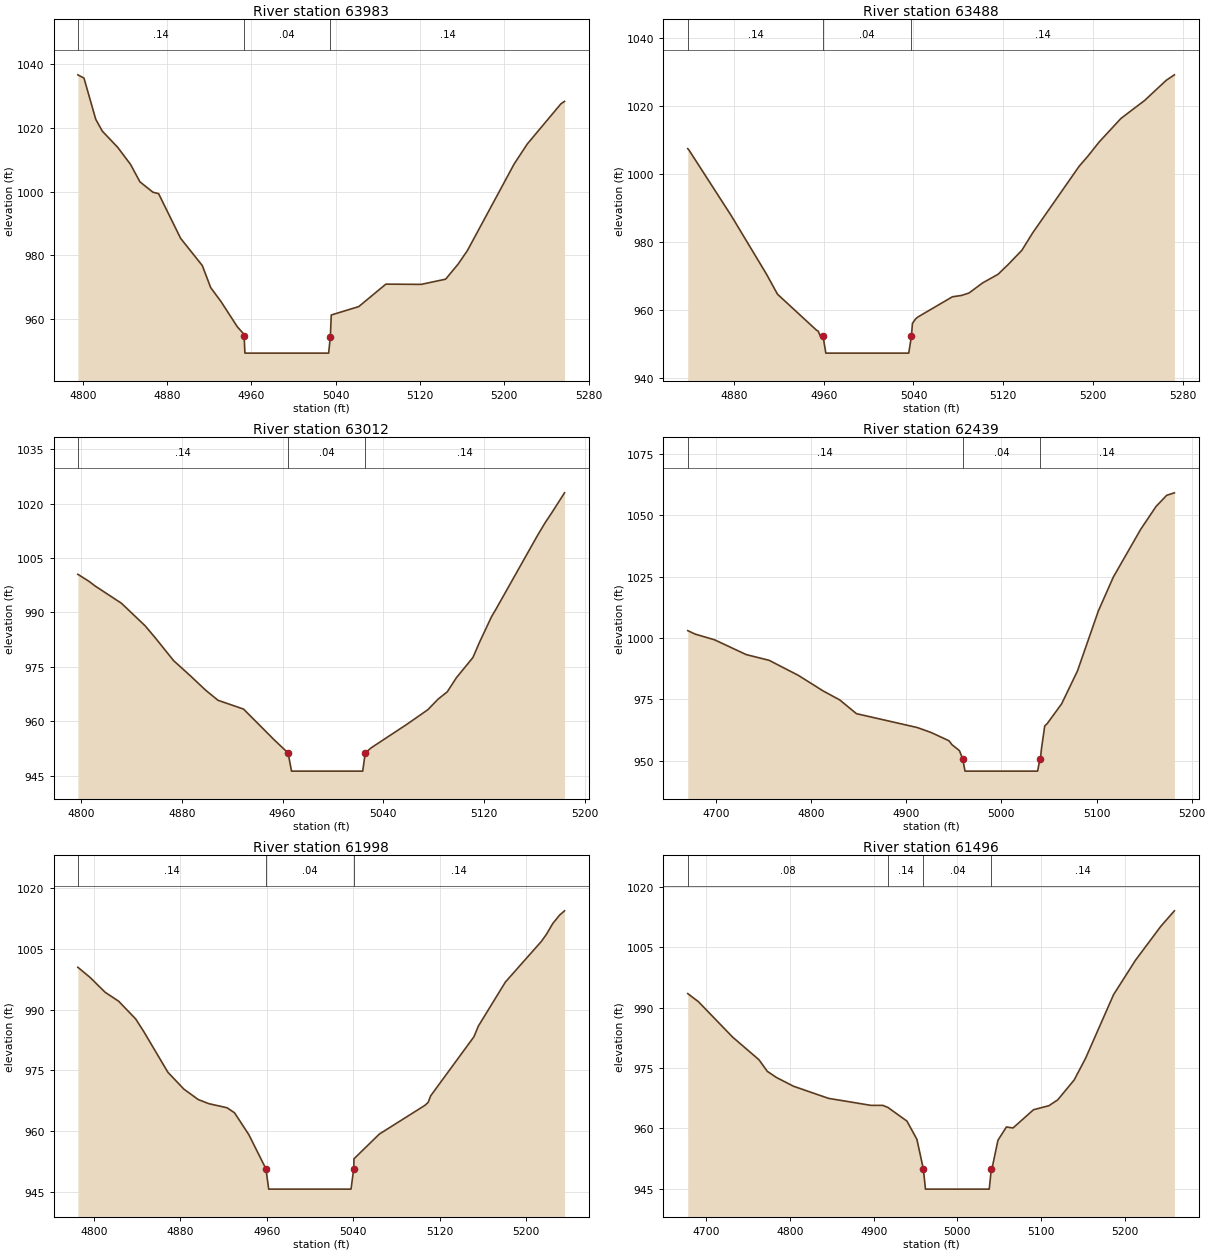
Type RM Length L Ch R = 1,63983,495,495,495
BEGIN DESCRIPTION:
Fisher River 128.0
END DESCRIPTION:
XS GIS Cut Line= 4
      1505602.95       960735.29      1505480.93       960836.01
      1505397.67       960868.92      1505198.22       960946.38
#Sta/Elev= 30
  4795.4 1036.67  4801.2 1035.64  4812.4 1022.67  4818.6 1018.98  4833.1 1013.93
  4845.4 1008.52  4854.3 1003.04  4866.7  999.78  4872.0  999.35  4892.9  985.30
  4913.5  976.74  4921.4  969.84  4931.1  965.50  4946.7  957.52  4951.9  955.58
  4953.1  954.56  4953.9  949.25  5033.3  949.25  5034.9  954.25  5035.8  961.23
  5061.9  963.87  5087.6  970.92  5121.2  970.85  5144.3  972.48  5156.2  977.23
  5165.0  981.49  5209.4 1008.72  5221.9 1015.00  5253.7 1027.57  5257.1 1028.33
#Mann=3,-1,0
  4795.4    0.14       0  4953.1    0.04       0  5034.9    0.14       0
Bank Sta=4953.1,5034.9
XS Rating Curve= 0
Exp/Cntr=0.3,0.1

Type RM Length L Ch R = 1,63488,476,476,476
BEGIN DESCRIPTION:
Fisher River 127.0
END DESCRIPTION:
XS GIS Cut Line= 3
      1505023.98       960466.17      1505118.86       960694.67
      1505105.31       960880.56
#Sta/Elev= 30
  4838.8 1007.45  4840.1 1006.93  4877.6  987.71  4908.9  970.55  4918.8  964.59
  4953.7  953.95  4955.1  953.71  4957.0  952.23  4959.4  952.23  4961.9  947.23
  5035.8  947.23  5038.2  952.23  5039.1  956.00  5042.0  957.34  5044.1  957.90
  5074.7  963.82  5082.8  964.22  5089.5  964.93  5101.7  967.92  5115.3  970.42
  5124.3  973.28  5136.7  977.54  5146.1  982.56  5187.8 1002.31  5195.6 1005.27
  5205.4 1009.36  5225.0 1016.36  5246.0 1021.62  5265.3 1027.57  5272.6 1029.19
#Mann=3,-1,0
  4838.8    0.14       0  4959.4    0.04       0  5038.2    0.14       0
Bank Sta=4959.4,5038.2
XS Rating Curve= 0
Exp/Cntr=0.3,0.1

Type RM Length L Ch R = 1,63012,573,573,573
BEGIN DESCRIPTION:
Fisher River 126.0
END DESCRIPTION:
XS GIS Cut Line= 2
      1504547.66       960667.53      1504771.29       960983.13
#Sta/Elev= 30
  4797.3 1000.53  4806.2  998.58  4810.7  997.38  4831.9  992.55  4850.7  986.34
  4859.0  982.93  4873.4  976.70  4886.9  972.46  4899.0  968.50  4908.7  965.76
  4929.0  963.33  4952.9  955.00  4964.4  951.21  4967.1  946.21  5023.7  946.21
  5025.7  951.21  5030.5  952.66  5058.5  959.06  5075.5  963.17  5083.5  966.05
  5090.9  968.10  5098.2  972.01  5111.3  977.57  5116.7  981.90  5126.1  988.84
  5129.1  990.60  5162.7 1011.30  5168.6 1014.73  5173.5 1017.26  5184.1 1023.02
#Mann=3,-1,0
  4797.3    0.14       0  4964.4    0.04       0  5025.7    0.14       0
Bank Sta=4964.4,5025.7
XS Rating Curve= 0
Exp/Cntr=0.3,0.1

Type RM Length L Ch R = 1,62439,441,441,441
BEGIN DESCRIPTION:
Fisher River 125.0
END DESCRIPTION:
XS GIS Cut Line= 3
      1504482.84       960642.37      1504255.32       960814.71
      1504046.23       960899.89
#Sta/Elev= 30
  4670.6 1003.00  4678.6 1001.57  4698.7  999.29  4732.0  993.26  4756.1  990.92
  4786.7  984.81  4812.9  978.43  4830.3  974.78  4847.8  969.19  4911.6  963.55
  4926.4  961.50  4945.1  958.13  4948.1  956.58  4956.0  954.12  4959.4  950.78
  4961.9  945.78  5038.1  945.78  5040.6  950.78  5041.1  950.78  5042.1  954.72
  5045.6  964.20  5048.1  965.09  5063.4  973.23  5080.0  986.60  5101.9 1011.00
  5117.6 1024.79  5146.3 1044.22  5162.5 1053.58  5173.7 1058.14  5181.8 1059.15
#Mann=3,-1,0
  4670.6    0.14       0  4959.4    0.04       0  5040.6    0.14       0
Bank Sta=4959.4,5040.6
XS Rating Curve= 0
Exp/Cntr=0.3,0.1

Type RM Length L Ch R = 1,61998,502,502,502
BEGIN DESCRIPTION:
Fisher River 124.0
END DESCRIPTION:
XS GIS Cut Line= 4
      1504436.35       960414.30      1504258.22       960400.75
      1504143.99       960381.39      1504006.54       960307.83
#Sta/Elev= 30
  4785.3 1000.50  4796.6  998.00  4810.5  994.33  4823.0  992.12  4838.8  987.73
  4846.1  984.69  4868.6  974.55  4883.4  970.38  4896.7  967.80  4906.6  966.77
  4923.4  965.77  4930.3  964.52  4943.5  959.13  4959.4  950.65  4961.9  945.65
  5038.1  945.65  5040.6  950.65  5040.8  953.14  5064.3  959.26  5106.4  966.35
  5109.5  967.09  5111.8  968.71  5151.9  983.34  5155.9  985.94  5181.0  996.86
  5214.3 1006.91  5218.9 1008.63  5224.9 1011.35  5231.1 1013.39  5235.7 1014.46
#Mann=3,-1,0
  4785.3    0.14       0  4959.4    0.04       0  5040.6    0.14       0
Bank Sta=4959.4,5040.6
XS Rating Curve= 0
Exp/Cntr=0.3,0.1

Type RM Length L Ch R = 1,61496,492,492,492
BEGIN DESCRIPTION:
Fisher River 123.0
END DESCRIPTION:
XS GIS Cut Line= 4
      1504604.81       960035.59      1504376.33       959911.67
      1504225.31       959888.43      1504099.45       959776.13
#Sta/Elev= 30
  4677.9  993.47  4690.6  991.48  4731.5  982.67  4763.0  977.04  4773.0  974.15
  4783.9  972.63  4804.2  970.46  4846.0  967.45  4896.8  965.70  4911.0  965.70
  4917.1  965.18  4939.8  961.79  4951.7  957.25  4959.4  949.89  4961.9  944.89
  5038.1  944.89  5040.6  949.89  5041.3  949.89  5048.5  957.03  5058.6  960.33
  5066.5  960.09  5091.0  964.62  5109.4  965.62  5119.9  967.07  5139.6  972.02
  5153.3  977.45  5186.7  993.24  5213.0 1001.82  5243.1 1010.20  5259.3 1014.04
#Mann=4,-1,0
  4677.9    0.08       0  4917.1    0.14       0  4959.4    0.04       0
  5040.6    0.14       0
Bank Sta=4959.4,5040.6
XS Rating Curve= 0
Exp/Cntr=0.3,0.1

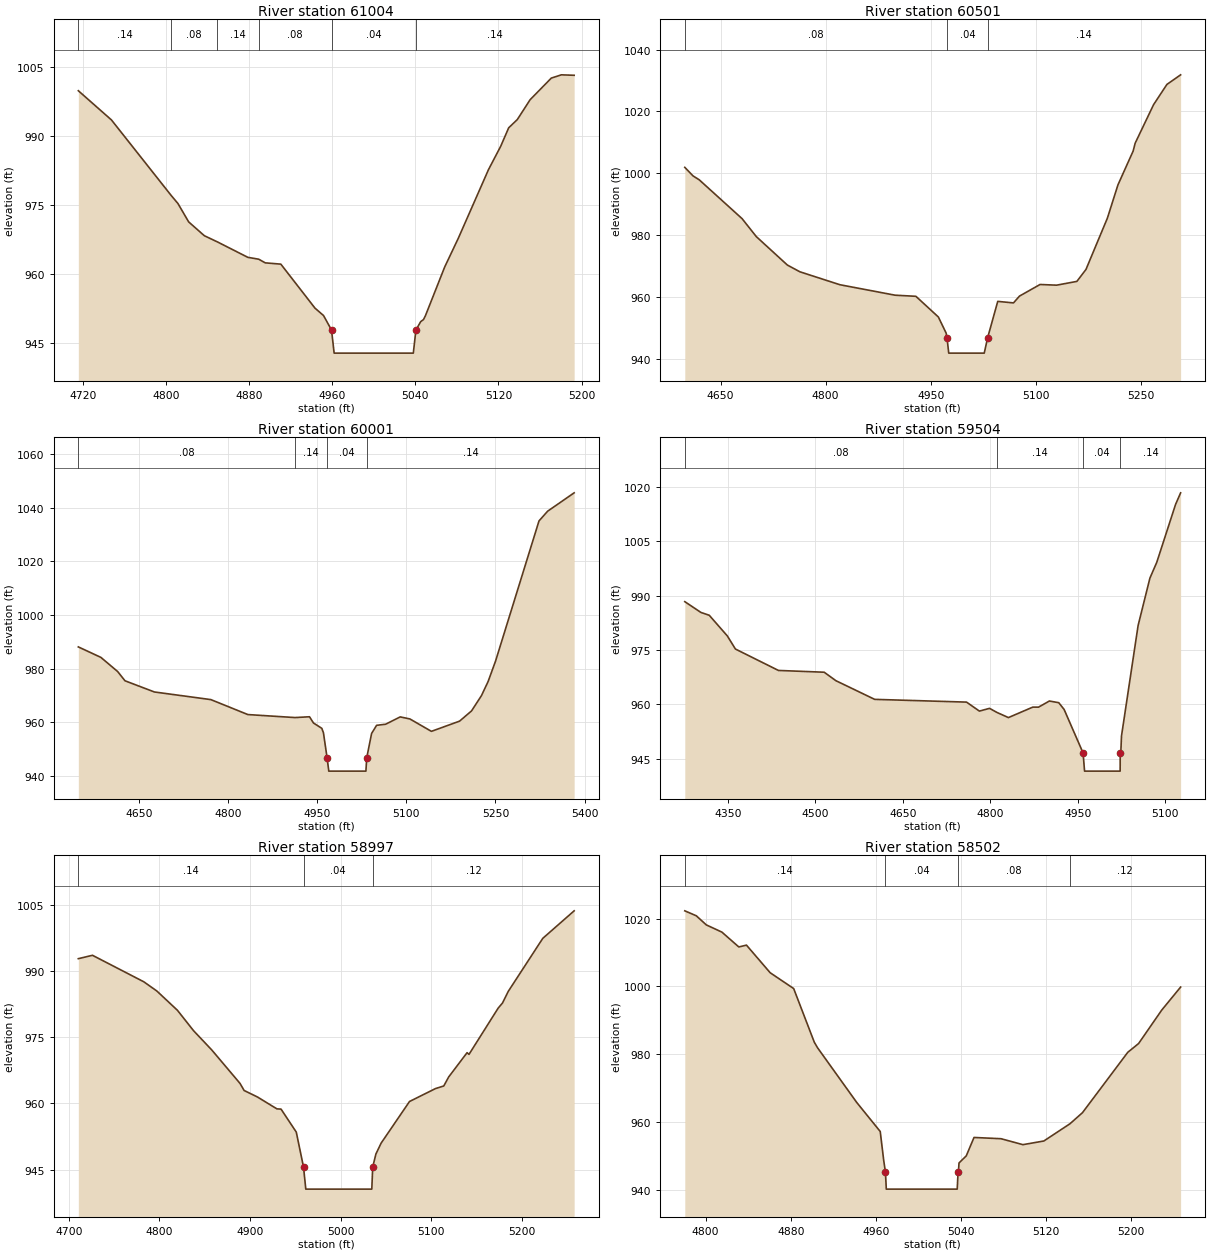
Type RM Length L Ch R = 1,61004,503,503,503
BEGIN DESCRIPTION:
Fisher River 122.0
END DESCRIPTION:
XS GIS Cut Line= 3
      1504734.53       959667.71      1504628.03       959512.81
      1504366.69       959388.91
#Sta/Elev= 30
  4715.7  999.80  4747.6  993.46  4804.8  977.16  4811.6  975.33  4821.9  971.35
  4837.0  968.35  4849.5  967.02  4878.8  963.67  4889.3  963.26  4895.6  962.47
  4910.6  962.19  4943.5  952.64  4951.7  951.04  4959.4  947.89  4961.9  942.89
  5038.1  942.89  5040.6  947.89  5045.2  949.72  5047.9  950.17  5049.7  950.97
  5068.3  961.57  5081.4  967.80  5110.5  982.71  5122.2  987.75  5129.9  991.76
  5138.2  993.55  5150.5  997.85  5170.9 1002.54  5180.6 1003.25  5192.9 1003.15
#Mann=6,-1,0
  4715.7    0.14       0  4804.8    0.08       0  4849.5    0.14       0
  4889.3    0.08       0  4959.4    0.04       0  5040.6    0.14       0
Bank Sta=4959.4,5040.6
XS Rating Curve= 0
Exp/Cntr=0.3,0.1

Type RM Length L Ch R = 1,60501,500,500,500
BEGIN DESCRIPTION:
Fisher River 121.0
END DESCRIPTION:
XS GIS Cut Line= 3
      1505129.49       959235.93      1504693.87       958978.42
      1504492.46       958960.99
#Sta/Elev= 30
  4598.8 1001.94  4610.6  999.17  4619.3  997.94  4680.6  985.37  4701.0  979.55
  4745.3  970.37  4763.1  968.20  4820.4  964.01  4899.2  960.63  4928.9  960.27
  4961.0  953.58  4972.1  948.36  4973.3  946.91  4975.8  941.91  5026.5  941.91
  5031.4  946.91  5045.8  958.63  5068.3  958.14  5076.8  960.33  5106.2  964.09
  5129.8  963.87  5158.8  965.09  5171.8  968.94  5202.4  985.53  5217.5  996.29
  5239.2 1007.21  5242.1 1009.76  5268.4 1022.21  5287.4 1028.73  5307.0 1031.84
#Mann=3,-1,0
  4598.8    0.08       0  4973.3    0.04       0  5031.4    0.14       0
Bank Sta=4973.3,5031.4
XS Rating Curve= 0
Exp/Cntr=0.3,0.1

Type RM Length L Ch R = 1,60001,497,497,497
BEGIN DESCRIPTION:
Fisher River 120.0
END DESCRIPTION:
XS GIS Cut Line= 3
      1505357.97       958833.20      1505092.72       958618.29
      1504633.87       958436.30
#Sta/Elev= 30
  4547.5  988.08  4585.5  984.16  4613.7  978.88  4626.1  975.42  4675.6  971.24
  4770.7  968.39  4833.0  962.80  4912.4  961.68  4936.8  961.98  4943.5  959.65
  4957.5  957.66  4960.3  956.00  4966.4  946.67  4969.3  941.67  5031.8  941.67
  5033.2  946.67  5041.4  955.75  5049.8  958.78  5065.0  959.19  5089.6  961.93
  5105.9  961.16  5142.1  956.53  5189.5  960.34  5209.7  964.17  5226.4  969.88
  5237.5  975.10  5250.1  982.76  5323.3 1035.14  5337.8 1038.77  5382.5 1045.64
#Mann=4,-1,0
  4547.5    0.08       0  4912.4    0.14       0  4966.4    0.04       0
  5033.2    0.14       0
Bank Sta=4966.4,5033.2
XS Rating Curve= 0
Exp/Cntr=0.3,0.1

Type RM Length L Ch R = 1,59504,507,507,507
BEGIN DESCRIPTION:
Fisher River 119.0
END DESCRIPTION:
XS GIS Cut Line= 4
      1505369.60       958815.78      1505259.23       958626.03
      1505226.32       958205.88      1505117.91       958025.85
#Sta/Elev= 30
  4275.7  988.35  4303.4  985.37  4317.7  984.59  4348.8  978.87  4362.6  975.27
  4436.5  969.36  4515.0  968.87  4535.0  966.54  4601.6  961.38  4759.3  960.62
  4781.4  958.14  4798.8  958.90  4811.4  957.78  4831.2  956.35  4873.1  959.24
  4882.9  959.23  4901.5  960.92  4917.6  960.46  4926.8  958.60  4959.4  946.57
  4961.9  941.57  5023.0  941.57  5023.1  946.57  5024.1  946.57  5025.3  951.26
  5053.8  981.75  5074.1  994.85  5085.9  999.23  5118.1 1015.18  5126.8 1018.39
#Mann=4,-1,0
  4275.7    0.08       0  4811.4    0.14       0  4959.4    0.04       0
  5023.1    0.14       0
Bank Sta=4959.4,5023.1
XS Rating Curve= 0
Exp/Cntr=0.3,0.1

Type RM Length L Ch R = 1,58997,495,495,495
BEGIN DESCRIPTION:
Fisher River 118.0
END DESCRIPTION:
XS GIS Cut Line= 3
      1505795.57       958399.52      1505629.05       958029.68
      1505522.59       957936.77
#Sta/Elev= 30
  4710.6  992.82  4726.2  993.59  4782.9  987.57  4797.2  985.49  4819.9  981.12
  4837.7  976.49  4857.8  972.12  4888.9  964.55  4893.5  962.93  4908.1  961.47
  4929.6  958.77  4934.2  958.71  4951.0  953.50  4959.0  945.57  4961.5  940.57
  5034.3  940.57  5035.3  945.57  5038.8  948.51  5044.5  950.97  5075.9  960.44
  5104.5  963.36  5113.7  963.96  5119.1  966.00  5139.4  971.51  5141.5  971.12
  5173.7  981.61  5178.5  982.78  5184.8  985.40  5222.9  997.43  5257.5 1003.67
#Mann=3,-1,0
  4710.6    0.14       0  4959.0    0.04       0  5035.3    0.12       0
Bank Sta=4959,5035.3
XS Rating Curve= 0
Exp/Cntr=0.3,0.1

Type RM Length L Ch R = 1,58502,506,506,506
BEGIN DESCRIPTION:
Fisher River 117.0
END DESCRIPTION:
XS GIS Cut Line= 3
      1506227.34       957853.49      1505964.01       957791.53
      1505791.69       957698.60
#Sta/Elev= 30
  4780.4 1022.31  4791.2 1020.85  4800.6 1018.16  4815.3 1016.02  4831.2 1011.64
  4838.4 1012.18  4860.7 1004.02  4882.8  999.35  4902.2  983.50  4905.3  981.84
  4942.1  965.71  4964.2  957.13  4967.5  948.53  4969.1  945.11  4969.9  940.11
  5036.6  940.11  5037.4  945.11  5037.7  945.12  5038.3  947.84  5045.1  949.93
  5052.4  955.37  5077.8  955.00  5098.4  953.24  5118.1  954.33  5142.7  959.43
  5154.4  962.69  5197.0  980.52  5207.2  983.12  5228.9  992.98  5246.7  999.79
#Mann=4,-1,0
  4780.4    0.14       0  4969.1    0.04       0  5037.4    0.08       0
  5142.7    0.12       0
Bank Sta=4969.1,5037.4
XS Rating Curve= 0
Exp/Cntr=0.3,0.1

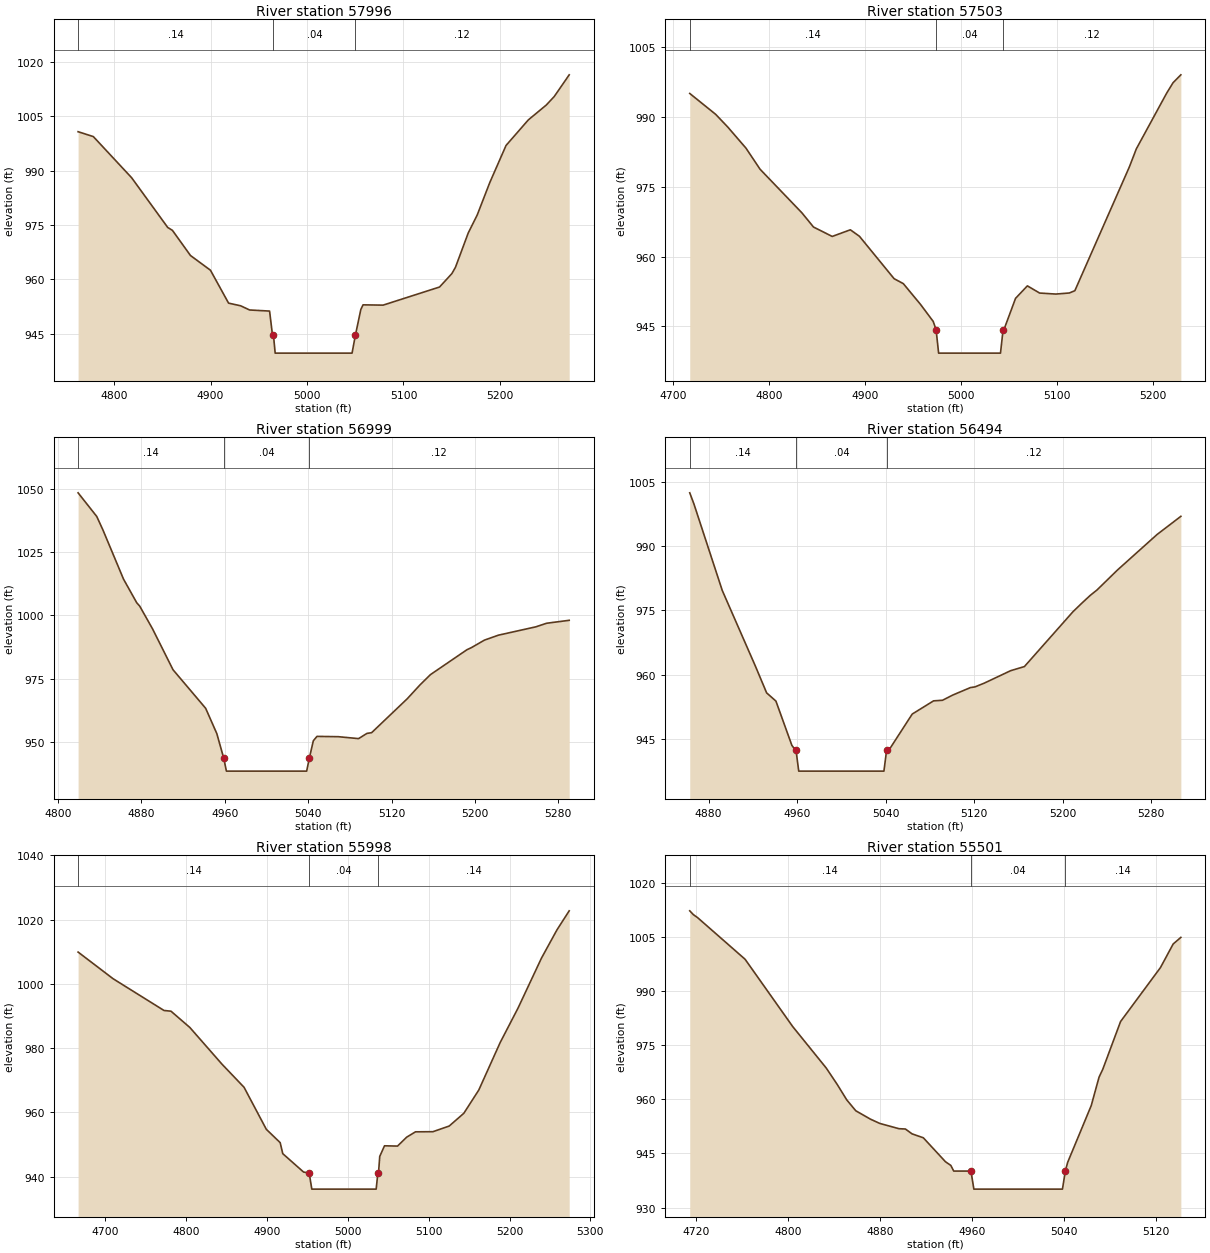
Type RM Length L Ch R = 1,57996,493,493,493
BEGIN DESCRIPTION:
Fisher River 116.0
END DESCRIPTION:
XS GIS Cut Line= 3
      1506413.24       957470.14      1506132.46       957291.99
      1506075.01       957125.03
#Sta/Elev= 30
  4762.7 1000.75  4778.5  999.40  4818.2  988.04  4855.6  974.32  4860.5  973.51
  4879.2  966.57  4899.9  962.51  4918.7  953.42  4931.2  952.69  4940.5  951.53
  4961.2  951.23  4964.2  944.65  4965.2  944.62  4967.0  939.62  5046.7  939.62
  5050.2  944.62  5055.8  951.67  5058.1  952.95  5078.9  952.87  5137.4  957.87
  5150.1  961.55  5153.9  963.32  5167.2  972.83  5176.5  977.79  5189.4  986.66
  5206.3  996.94  5229.4 1004.00  5248.0 1008.10  5256.3 1010.46  5271.8 1016.45
#Mann=3,-1,0
  4762.7    0.14       0  4965.2    0.04       0  5050.2    0.12       0
Bank Sta=4965.2,5050.2
XS Rating Curve= 0
Exp/Cntr=0.3,0.1

Type RM Length L Ch R = 1,57503,504,504,504
BEGIN DESCRIPTION:
Fisher River 115.0
END DESCRIPTION:
XS GIS Cut Line= 3
      1506637.80       957208.78      1506651.36       957051.91
      1506357.04       956854.40
#Sta/Elev= 30
  4717.3  995.01  4744.3  990.53  4756.8  987.83  4775.9  983.27  4790.6  978.74
  4834.2  969.38  4846.3  966.33  4865.8  964.31  4884.7  965.74  4894.2  964.34
  4930.3  955.24  4939.9  954.18  4957.8  949.73  4971.1  946.06  4974.1  944.26
  4976.7  939.26  5041.2  939.26  5043.9  944.26  5044.7  944.26  5056.9  951.02
  5069.2  953.70  5082.0  952.16  5098.8  951.94  5112.9  952.17  5118.7  952.66
  5175.6  979.27  5182.8  983.12  5214.5  995.11  5221.1  997.32  5229.2  999.01
#Mann=3,-1,0
  4717.3    0.14       0  4974.1    0.04       0  5043.9    0.12       0
Bank Sta=4974.1,5043.9
XS Rating Curve= 0
Exp/Cntr=0.3,0.1

Type RM Length L Ch R = 1,56999,505,505,505
BEGIN DESCRIPTION:
Fisher River 114.0
END DESCRIPTION:
XS GIS Cut Line= 3
      1506707.53       956410.62      1506519.70       956524.87
      1506320.26       956677.84
#Sta/Elev= 30
  4819.2 1048.30  4837.1 1038.98  4843.0 1033.69  4862.8 1014.25  4875.5 1004.92
  4878.3 1003.63  4890.7  994.60  4910.3  978.51  4941.6  963.32  4952.3  953.34
  4959.0  943.54  4961.5  938.54  5038.5  938.54  5041.0  943.54  5044.9  950.51
  5048.4  952.24  5068.9  952.12  5088.3  951.36  5096.4  953.43  5100.8  953.69
  5135.0  967.08  5147.3  972.57  5157.3  976.61  5192.4  986.45  5196.4  987.21
  5209.1  990.21  5222.4  992.15  5258.4  995.45  5268.7  996.86  5290.4  998.02
#Mann=3,-1,0
  4819.2    0.14       0  4959.0    0.04       0  5041.0    0.12       0
Bank Sta=4959,5041
XS Rating Curve= 0
Exp/Cntr=0.3,0.1

Type RM Length L Ch R = 1,56494,496,496,496
BEGIN DESCRIPTION:
Fisher River 113.0
END DESCRIPTION:
XS GIS Cut Line= 3
      1506221.52       956083.43      1506115.03       956267.36
      1506004.65       956470.70
#Sta/Elev= 30
  4863.0 1002.45  4866.8  999.83  4892.4  979.64  4922.2  962.06  4932.5  955.73
  4940.9  953.81  4955.3  943.48  4957.1  942.85  4957.4  942.47  4959.0  942.46
  4961.5  937.46  5038.5  937.46  5041.0  942.46  5043.4  942.52  5064.1  950.79
  5083.4  953.87  5091.5  954.01  5100.6  955.21  5116.7  956.97  5120.8  957.13
  5129.3  958.02  5153.1  960.92  5165.5  961.88  5209.3  974.66  5216.9  976.56
  5224.9  978.48  5231.1  979.76  5249.5  984.40  5285.4  992.72  5306.9  996.96
#Mann=3,-1,0
  4863.0    0.14       0  4959.0    0.04       0  5041.0    0.12       0
Bank Sta=4959,5041
XS Rating Curve= 0
Exp/Cntr=0.3,0.1

Type RM Length L Ch R = 1,55998,497,497,497
BEGIN DESCRIPTION:
Fisher River 112.0
END DESCRIPTION:
XS GIS Cut Line= 4
      1506103.40       955918.84      1505812.99       955911.10
      1505685.20       955907.23      1505551.60       955773.63
#Sta/Elev= 30
  4666.5 1009.90  4709.9 1001.58  4772.7  991.72  4781.4  991.49  4804.7  986.42
  4844.3  975.04  4871.7  967.81  4899.3  954.71  4916.4  950.57  4919.6  947.14
  4945.3  941.42  4952.3  941.10  4955.5  936.10  5035.1  936.10  5037.2  941.10
  5038.0  941.10  5039.5  946.27  5045.4  949.59  5061.5  949.50  5072.8  952.27
  5083.7  953.94  5105.3  953.98  5125.4  955.74  5143.5  959.71  5162.0  966.95
  5188.4  981.71  5210.5  992.45  5239.6 1008.06  5258.6 1016.78  5273.8 1022.74
#Mann=3,-1,0
  4666.5    0.14       0  4952.3    0.04       0  5037.2    0.14       0
Bank Sta=4952.3,5037.2
XS Rating Curve= 0
Exp/Cntr=0.3,0.1

Type RM Length L Ch R = 1,55501,496,496,496
BEGIN DESCRIPTION:
Fisher River 111.0
END DESCRIPTION:
XS GIS Cut Line= 3
      1506221.51       955651.64      1506089.86       955550.97
      1505876.90       955399.95
#Sta/Elev= 30
  4714.6 1012.17  4717.7 1011.13  4721.4 1010.29  4762.7  998.76  4804.1  980.12
  4833.2  968.66  4842.8  964.09  4851.1  959.81  4858.9  956.82  4871.7  954.49
  4879.7  953.32  4896.4  951.86  4902.0  951.77  4907.8  950.43  4917.6  949.34
  4936.8  942.72  4941.5  941.69  4944.0  940.13  4959.0  940.13  4961.5  935.13
  5038.5  935.13  5041.0  940.13  5043.0  942.52  5063.5  958.24  5070.3  966.12
  5073.6  968.35  5089.0  981.52  5123.7  996.47  5134.7 1002.98  5141.4 1004.82
#Mann=3,-1,0
  4714.6    0.14       0  4959.0    0.04       0  5041.0    0.14       0
Bank Sta=4959,5041
XS Rating Curve= 0
Exp/Cntr=0.3,0.1

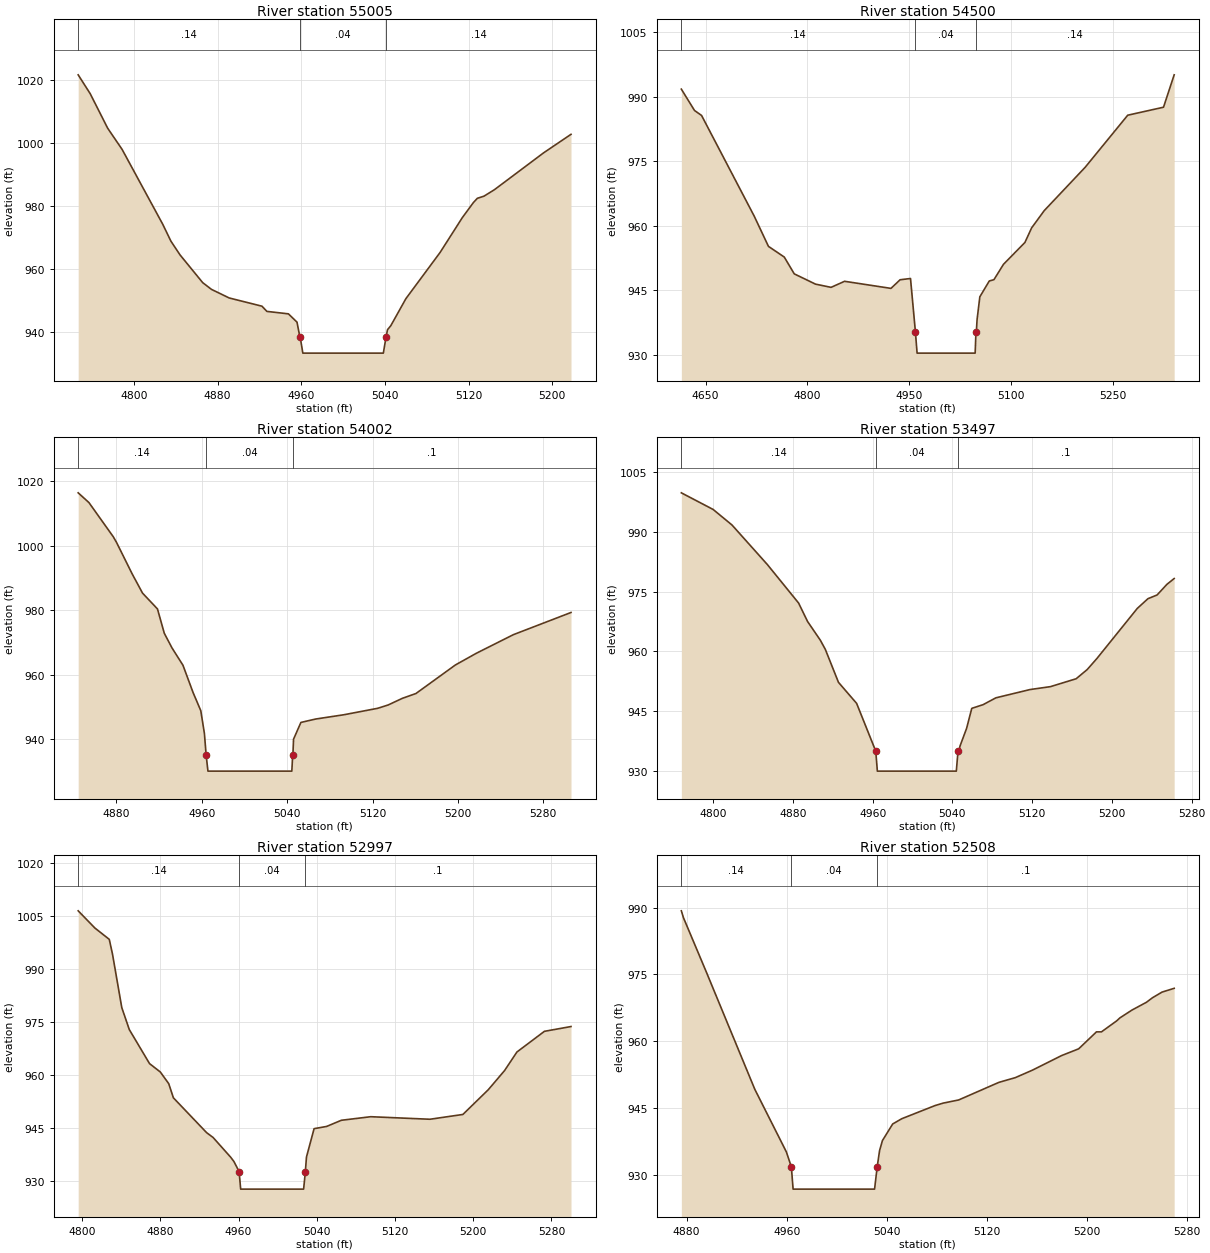
Type RM Length L Ch R = 1,55005,505,505,505
BEGIN DESCRIPTION:
Fisher River 110.0
END DESCRIPTION:
XS GIS Cut Line= 3
      1506521.63       955188.89      1506347.38       955113.39
      1506093.69       954991.39
#Sta/Elev= 30
  4746.6 1021.71  4758.1 1015.72  4774.8 1004.77  4788.6  998.04  4827.5  974.26
  4835.3  968.90  4844.0  964.55  4865.7  955.73  4874.1  953.59  4891.0  950.87
  4922.4  948.25  4927.1  946.60  4947.7  945.82  4955.9  943.19  4958.7  938.41
  4959.0  938.35  4961.5  933.35  5038.5  933.35  5041.0  938.35  5042.5  940.80
  5045.6  942.04  5060.1  950.66  5092.8  965.32  5114.1  976.40  5124.7  981.18
  5128.4  982.50  5134.8  983.19  5144.8  985.25  5191.8  996.94  5218.0 1002.82
#Mann=3,-1,0
  4746.6    0.14       0  4959.0    0.04       0  5041.0    0.14       0
Bank Sta=4959,5041
XS Rating Curve= 0
Exp/Cntr=0.3,0.1

Type RM Length L Ch R = 1,54500,498,498,498
BEGIN DESCRIPTION:
Fisher River 109.0
END DESCRIPTION:
XS GIS Cut Line= 4
      1506655.23       954989.46      1506601.02       954683.55
      1506457.74       954598.36      1506217.66       954662.25
#Sta/Elev= 30
  4614.3  991.79  4633.7  986.82  4644.1  985.66  4721.7  962.20  4742.6  955.19
  4765.9  952.70  4780.6  948.79  4811.9  946.40  4834.8  945.65  4854.7  947.06
  4923.0  945.41  4936.5  947.42  4951.8  947.71  4959.0  935.34  4961.5  930.34
  5047.0  930.34  5048.2  935.34  5048.8  935.34  5049.8  938.10  5053.9  943.45
  5067.8  947.13  5074.7  947.44  5088.7  951.01  5120.3  956.10  5130.2  959.50
  5148.8  963.52  5209.1  973.61  5271.7  985.72  5324.4  987.58  5340.1  995.12
#Mann=3,-1,0
  4614.3    0.14       0  4959.0    0.04       0  5048.2    0.14       0
Bank Sta=4959,5048.2
XS Rating Curve= 0
Exp/Cntr=0.3,0.1

Type RM Length L Ch R = 1,54002,505,505,505
BEGIN DESCRIPTION:
Fisher River 108.0
END DESCRIPTION:
XS GIS Cut Line= 3
      1506864.39       954189.82      1506649.42       954176.27
      1506407.44       954222.73
#Sta/Elev= 30
  4844.1 1016.45  4854.2 1013.42  4877.0 1002.82  4880.1 1001.03  4894.8  991.24
  4904.4  985.35  4918.4  980.44  4924.8  972.89  4932.0  968.36  4942.3  962.97
  4951.7  954.57  4959.0  948.88  4962.4  941.78  4964.0  935.14  4965.7  930.14
  5044.3  930.14  5045.1  935.14  5045.3  935.15  5045.9  940.04  5052.8  945.24
  5066.5  946.29  5093.0  947.62  5124.7  949.62  5134.6  950.66  5147.9  952.72
  5160.6  954.21  5197.6  963.07  5217.3  966.71  5251.9  972.46  5305.9  979.34
#Mann=3,-1,0
  4844.1    0.14       0  4964.0    0.04       0  5045.1     0.1       0
Bank Sta=4964,5045.1
XS Rating Curve= 0
Exp/Cntr=0.3,0.1

Type RM Length L Ch R = 1,53497,500,500,500
BEGIN DESCRIPTION:
Fisher River 107.0
END DESCRIPTION:
XS GIS Cut Line= 3
      1507003.73       953677.51      1506862.40       953692.99
      1506513.89       953642.65
#Sta/Elev= 30
  4768.1  999.74  4800.0  995.57  4818.9  991.68  4854.4  981.76  4885.7  972.12
  4894.7  967.50  4907.5  962.81  4912.5  960.52  4925.7  952.25  4943.9  946.98
  4963.1  935.00  4964.7  930.00  5043.9  930.00  5045.6  935.00  5046.5  935.01
  5047.6  936.28  5054.2  940.71  5059.4  945.73  5070.7  946.65  5083.6  948.37
  5117.8  950.44  5138.3  951.17  5164.1  953.15  5175.2  955.46  5185.0  958.25
  5225.4  970.77  5236.1  973.21  5245.3  974.15  5255.1  976.80  5262.4  978.26
#Mann=3,-1,0
  4768.1    0.14       0  4963.1    0.04       0  5045.6     0.1       0
Bank Sta=4963.1,5045.6
XS Rating Curve= 0
Exp/Cntr=0.3,0.1

Type RM Length L Ch R = 1,52997,489,489,489
BEGIN DESCRIPTION:
Fisher River 106.0
END DESCRIPTION:
XS GIS Cut Line= 3
      1506974.73       953085.01      1506848.85       953168.28
      1506523.54       953305.77
#Sta/Elev= 30
  4795.9 1006.51  4813.0 1001.63  4827.7  998.42  4831.0  994.24  4840.5  979.06
  4848.2  972.82  4868.9  963.17  4879.9  960.80  4888.5  957.50  4893.3  953.47
  4927.2  943.61  4933.9  942.22  4951.9  936.62  4955.2  935.40  4960.5  932.57
  4962.1  927.57  5026.5  927.57  5028.3  932.57  5029.4  936.66  5037.2  944.72
  5050.0  945.35  5065.1  947.10  5095.2  948.11  5155.7  947.39  5189.4  948.75
  5215.4  955.77  5232.1  961.22  5244.7  966.47  5272.8  972.33  5300.0  973.69
#Mann=3,-1,0
  4795.9    0.14       0  4960.5    0.04       0  5028.3     0.1       0
Bank Sta=4960.5,5028.3
XS Rating Curve= 0
Exp/Cntr=0.3,0.1

Type RM Length L Ch R = 1,52508,488,488,488
BEGIN DESCRIPTION:
Fisher River 105.0
END DESCRIPTION:
XS GIS Cut Line= 3
      1506401.59       952903.00      1506415.14       952976.60
      1506461.61       953292.16
#Sta/Elev= 30
  4875.8  989.27  4877.5  987.72  4896.1  975.32  4934.5  949.24  4959.7  935.21
  4963.7  931.85  4965.1  926.85  5030.2  926.85  5032.3  931.85  5034.2  935.49
  5036.5  937.75  5044.7  941.47  5052.0  942.65  5078.5  945.59  5085.0  946.14
  5097.4  946.85  5129.5  950.79  5142.7  951.86  5156.3  953.53  5179.6  956.80
  5193.3  958.32  5207.5  962.12  5211.5  962.12  5223.8  964.62  5226.2  965.25
  5235.8  967.00  5247.4  968.75  5252.3  969.78  5259.9  971.04  5269.6  971.89
#Mann=3,-1,0
  4875.8    0.14       0  4963.7    0.04       0  5032.3     0.1       0
Bank Sta=4963.7,5032.3
XS Rating Curve= 0
Exp/Cntr=0.3,0.1