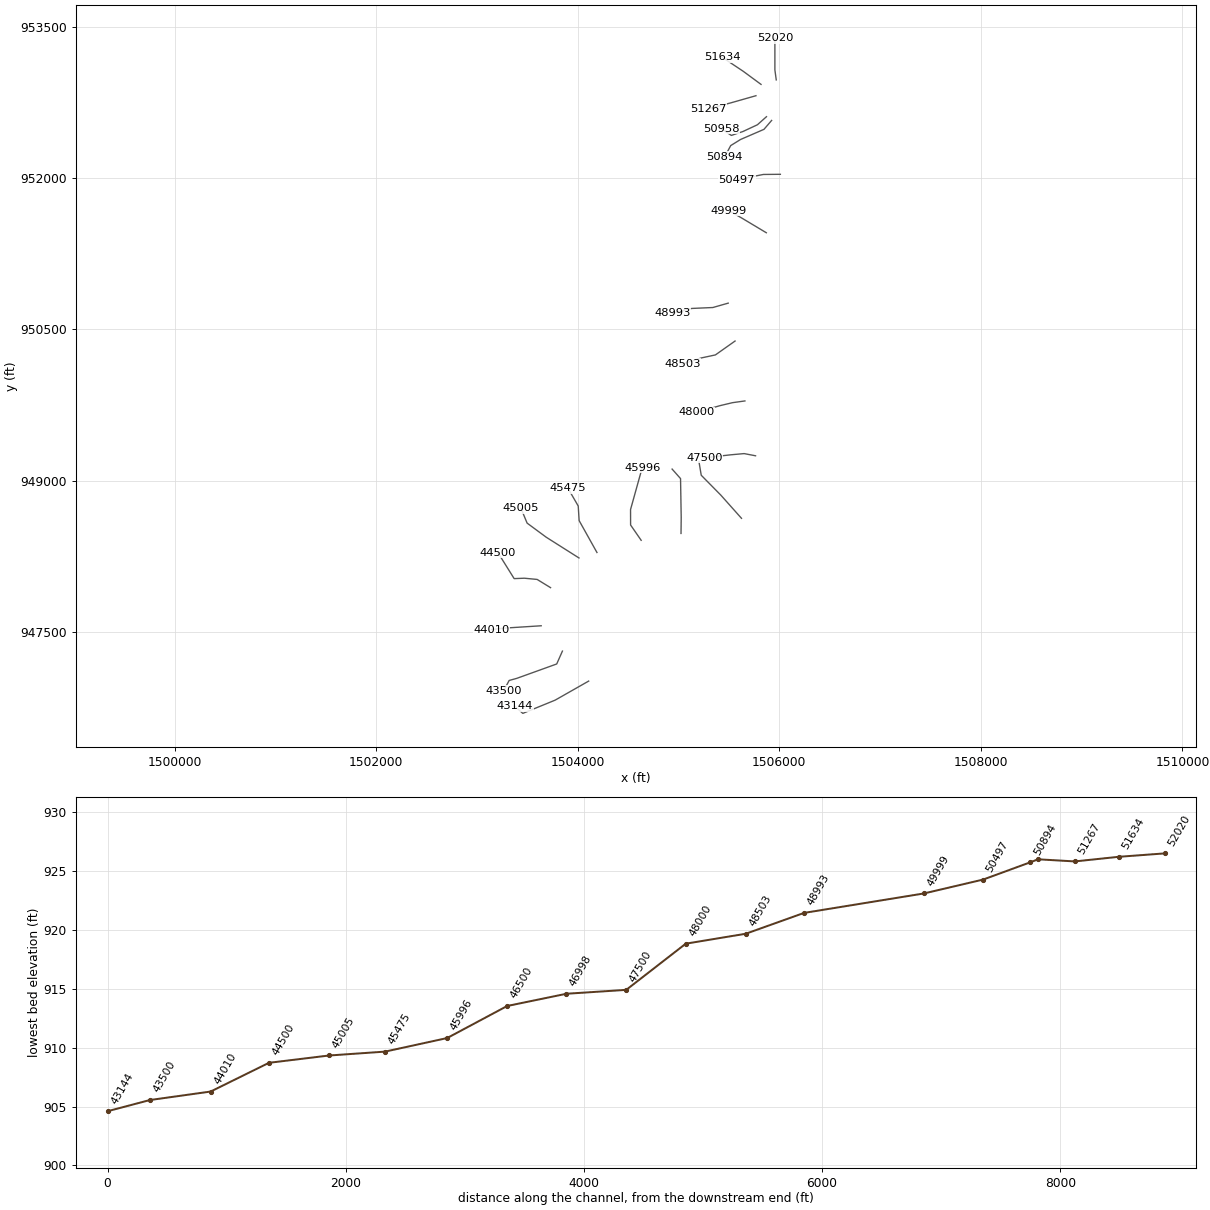
HEC-RAS study Fisher River.prj: Fisher River Limited Detail Study

--- Fisher River.g01 (geometry) --- (continued)

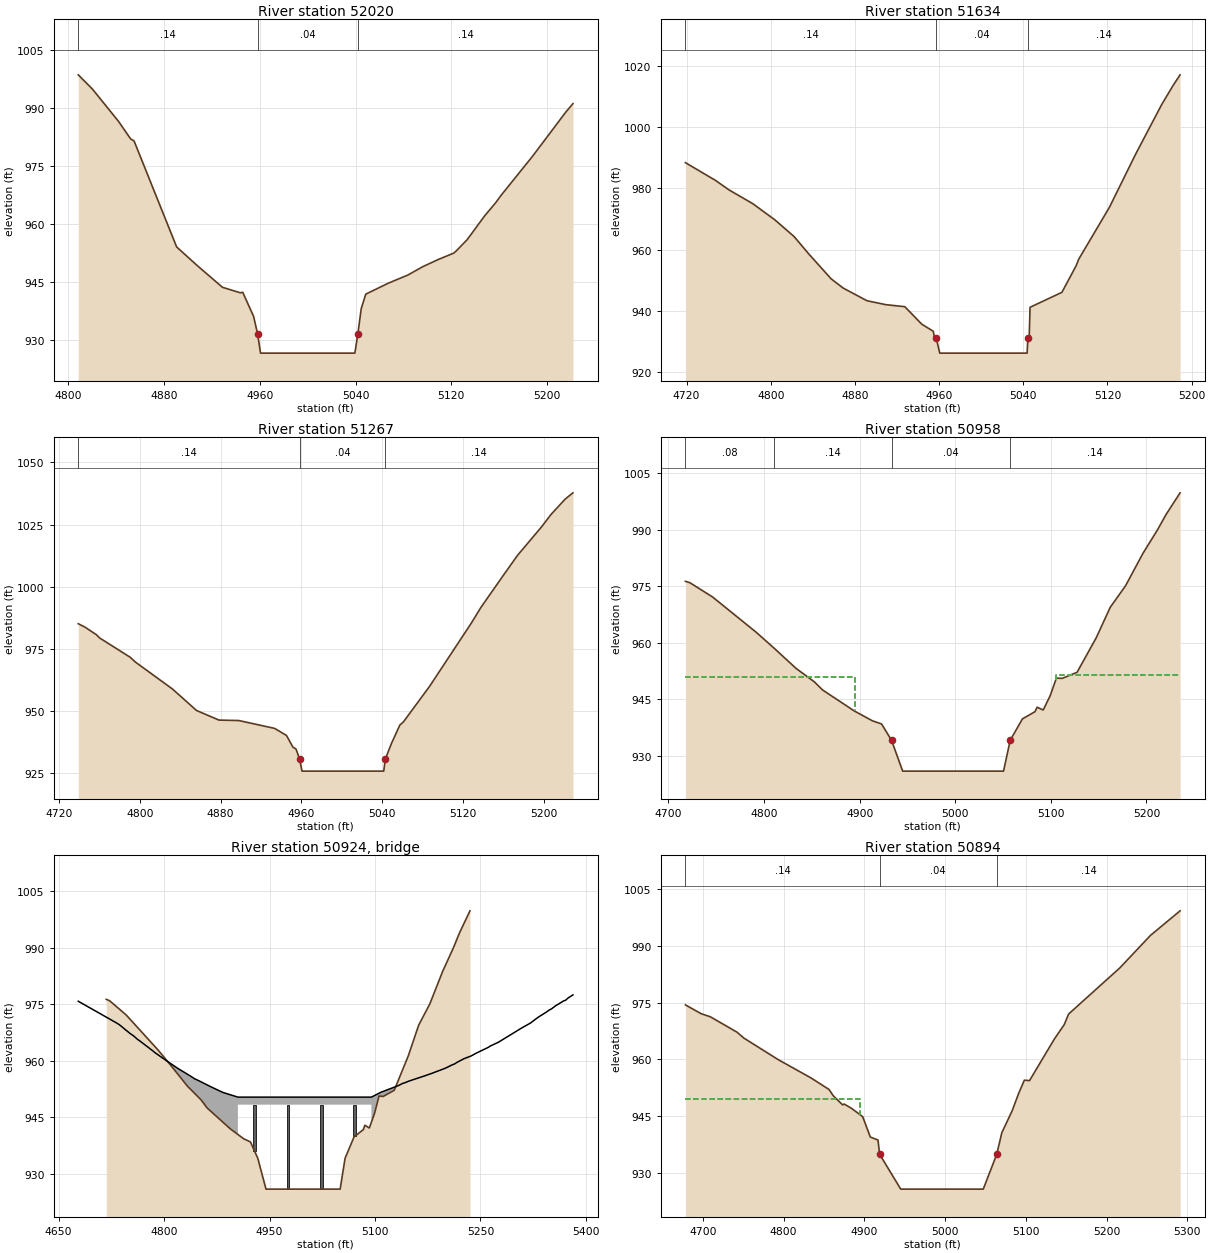
Type RM Length L Ch R = 1,52020,386,386,386
BEGIN DESCRIPTION:
Fisher River 104.0
END DESCRIPTION:
XS GIS Cut Line= 3
      1505969.81       952974.70      1505956.27       953073.41
      1505956.27       953387.08
#Sta/Elev= 30
  4808.3  998.62  4820.2  994.90  4841.8  986.61  4852.1  981.99  4854.9  981.49
  4890.5  954.00  4907.9  949.12  4928.8  943.54  4943.7  942.12  4945.7  942.25
  4954.8  935.99  4958.1  931.48  4960.6  926.48  5039.4  926.48  5041.9  931.48
  5044.7  938.00  5048.5  941.77  5067.3  944.60  5083.6  946.71  5096.0  948.87
  5108.7  950.70  5122.1  952.42  5124.2  953.01  5133.2  955.88  5147.9  962.09
  5157.3  965.56  5161.3  967.28  5188.2  977.65  5215.4  988.87  5221.6  991.16
#Mann=3,-1,0
  4808.3    0.14       0  4958.1    0.04       0  5041.9    0.14       0
Bank Sta=4958.1,5041.9
XS Rating Curve= 0
Exp/Cntr=0.3,0.1

Type RM Length L Ch R = 1,51634,367,367,367
BEGIN DESCRIPTION:
Fisher River 103.0
END DESCRIPTION:
XS GIS Cut Line= 3
      1505818.79       952930.13      1505642.60       953059.86
      1505433.50       953199.25
#Sta/Elev= 30
  4718.9  988.34  4747.5  982.54  4760.4  979.43  4782.9  974.96  4803.8  969.71
  4822.2  964.22  4836.4  958.45  4857.4  950.43  4868.8  947.42  4891.4  943.29
  4909.4  942.00  4927.4  941.34  4943.6  935.61  4954.5  933.32  4955.6  931.19
  4957.2  931.19  4960.6  926.19  5043.6  926.19  5044.4  931.19  5045.6  931.20
  5046.4  941.04  5046.5  941.16  5076.7  946.03  5090.2  954.69  5092.7  956.85
  5122.0  973.87  5146.7  991.07  5171.5 1007.28  5181.9 1013.27  5189.0 1016.99
#Mann=3,-1,0
  4718.9    0.14       0  4957.2    0.04       0  5044.4    0.14       0
Bank Sta=4957.2,5044.4
XS Rating Curve= 0
Exp/Cntr=0.3,0.1

Type RM Length L Ch R = 1,51267,309,309,309
BEGIN DESCRIPTION:
Fisher River 102.0
END DESCRIPTION:
XS GIS Cut Line= 3
      1505768.43       952817.83      1505521.39       952747.56
      1505296.04       952688.11
#Sta/Elev= 30
  4739.0  985.11  4745.5  983.76  4757.0  980.68  4760.1  979.39  4790.3  971.64
  4795.7  969.64  4832.3  958.83  4856.1  950.20  4878.4  946.33  4898.0  946.15
  4933.4  943.00  4945.2  940.16  4951.6  935.43  4954.6  934.71  4958.1  930.80
  4960.6  925.80  5041.5  925.80  5043.2  930.80  5049.2  936.96  5057.5  944.35
  5061.0  945.60  5086.8  959.84  5128.2  985.31  5137.8  991.69  5160.0 1004.57
  5174.0 1012.60  5197.9 1024.11  5207.1 1029.02  5221.4 1035.31  5228.9 1037.76
#Mann=3,-1,0
  4739.0    0.14       0  4958.1    0.04       0  5043.2    0.14       0
Bank Sta=4958.1,5043.2
XS Rating Curve= 0
Exp/Cntr=0.5,0.3

Type RM Length L Ch R = 1,50958,64,64,64
BEGIN DESCRIPTION:
Hamlin Ford Road - US
END DESCRIPTION:
XS GIS Cut Line= 5
      1505872.82       952609.69      1505782.89       952529.56
      1505638.92       952462.54      1505524.30       952423.82
      1505426.73       952488.86
#Sta/Elev= 30
  4717.7  976.35  4722.4  975.99  4746.2  972.18  4791.6  962.87  4809.9  958.75
  4833.3  953.28  4852.7  949.65  4861.1  947.54  4894.3  941.96  4913.3  939.34
  4922.9  938.50  4933.3  934.18  4945.0  925.98  5050.5  925.98  5057.5  934.18
  5070.3  939.85  5083.4  941.76  5085.6  942.93  5092.0  942.21  5099.3  946.00
  5105.8  950.67  5111.8  950.59  5127.4  952.20  5147.4  961.33  5162.2  969.49
  5178.1  975.15  5196.4  983.80  5211.6  990.02  5220.5  994.07  5235.2  999.84
#Mann=4,-1,0
  4717.7    0.08       0  4809.9    0.14       0  4933.3    0.04       0
  5057.5    0.14       0
#XS Ineff=2,0
    0.00 4895.00  951.00 5105.00    0.00  951.42
Permanent Ineff=
       F       F
Bank Sta=4933.3,5057.5
XS Rating Curve= 0
Exp/Cntr=0.5,0.3

Type RM Length L Ch R =3,50924,,,
BEGIN DESCRIPTION:
HamlinFord Road - TOR
Structure ID: LDS_FR_05
Approximate Survey Structure
END DESCRIPTION:
Bridge Culvert--1,0,-1,-1,0
Deck Dist Width WeirC Skew NumUp NumDn MinLoCord MaxHiCord MaxSubmerge Is_Ogee
29,10,3,,59,59,,,0.95,0,1,1,,,
  4677.9  4731.8  4736.0  4738.3  4750.8  4757.1  4761.9  4765.4  4785.3  4786.0
  4795.6  4797.1  4807.8  4819.6  4838.3  4843.2  4850.4  4866.8  4883.4  4905.0
  4905.0  5095.0  5095.0  5109.8  5110.6  5110.8  5111.1  5133.5  5140.4  5142.5
  5148.4  5170.8  5178.1  5179.0  5179.2  5198.8  5203.3  5209.5  5213.0  5216.5
  5226.7  5236.7  5243.9  5261.5  5263.9  5275.7  5308.7  5321.5  5330.2  5331.1
  5332.7  5343.3  5347.7  5351.3  5357.4  5368.6  5371.2  5374.7  5381.7
  975.84  970.14  969.66  969.32  967.40  966.57  965.77  965.32  962.48  962.34
  961.07  960.87  959.50  958.01  955.90  955.29  954.66  953.12  951.66  950.40
  950.40  950.40  950.40  951.81  951.84  951.85  951.87  953.47  954.12  954.20
  954.66  956.04  956.53  956.57  956.59  957.97  958.35  958.93  959.17  959.60
  960.60  961.31  962.05  963.63  963.94  964.97  968.74  970.09  971.32  971.42
  971.66  972.89  973.47  973.84  974.68  975.95  976.10  976.70  977.53
  905.98  905.98  905.98  905.98  905.98  905.98  905.98  905.98  905.98  905.98
  905.98  905.98  905.98  905.98  905.98  905.98  905.98  905.98  905.98  905.98
  948.40  948.40  905.98  905.98  905.98  905.98  905.98  905.98  905.98  905.98
  905.98  905.98  905.98  905.98  905.98  905.98  905.98  905.98  905.98  905.98
  905.98  905.98  905.98  905.98  905.98  905.98  905.98  905.98  905.98  905.98
  905.98  905.98  905.98  905.98  905.98  905.98  905.98  905.98  905.98
  4677.9  4731.8  4736.0  4738.3  4750.8  4757.1  4761.9  4765.4  4785.3  4786.0
  4795.6  4797.1  4807.8  4819.6  4838.3  4843.2  4850.4  4866.8  4883.4  4905.0
  4905.0  5095.0  5095.0  5109.8  5110.6  5110.8  5111.1  5133.5  5140.4  5142.5
  5148.4  5170.8  5178.1  5179.0  5179.2  5198.8  5203.3  5209.5  5213.0  5216.5
  5226.7  5236.7  5243.9  5261.5  5263.9  5275.7  5308.7  5321.5  5330.2  5331.1
  5332.7  5343.3  5347.7  5351.3  5357.4  5368.6  5371.2  5374.7  5381.7
  975.84  970.14  969.66  969.32  967.40  966.57  965.77  965.32  962.48  962.34
  961.07  960.87  959.50  958.01  955.90  955.29  954.66  953.12  951.66  950.40
  950.40  950.40  950.40  951.81  951.84  951.85  951.87  953.47  954.12  954.20
  954.66  956.04  956.53  956.57  956.59  957.97  958.35  958.93  959.17  959.60
  960.60  961.31  962.05  963.63  963.94  964.97  968.74  970.09  971.32  971.42
  971.66  972.89  973.47  973.84  974.68  975.95  976.10  976.70  977.53
  905.98  905.98  905.98  905.98  905.98  905.98  905.98  905.98  905.98  905.98
  905.98  905.98  905.98  905.98  905.98  905.98  905.98  905.98  905.98  905.98
  948.40  948.40  905.98  905.98  905.98  905.98  905.98  905.98  905.98  905.98
  905.98  905.98  905.98  905.98  905.98  905.98  905.98  905.98  905.98  905.98
  905.98  905.98  905.98  905.98  905.98  905.98  905.98  905.98  905.98  905.98
  905.98  905.98  905.98  905.98  905.98  905.98  905.98  905.98  905.98
Pier Skew, UpSta & Num, DnSta & Num=,4928.8,2,4928.8,2,0,0,0,0,0
       4       4
  943.49  948.40
       4       4
  941.79  948.40
Pier Skew, UpSta & Num, DnSta & Num=,4976.3,2,4976.3,2,0,0,0,0,0
       4       4
  930.30  948.40
       4       4
  930.05  948.40
Pier Skew, UpSta & Num, DnSta & Num=,5023.8,2,5023.8,2,0,0,0,0,0
       4       4
  930.30  948.40
       4       4
  930.05  948.40
Pier Skew, UpSta & Num, DnSta & Num=,5071.3,2,5071.3,2,0,0,0,0,0
       4       4
  939.92  948.40
       4       4
  941.13  948.40
BR Coef=1,1,0,1.25,0,,,0.8,0,2,0,
WSPro=,,,, 1 ,,,, 0 ,,,, 0 ,,,,-1 ,-1 ,-1 , 0 , 0 , 0 , 0 , 0
BC Design=,,0,,0,,,,,,

Type RM Length L Ch R = 1,50894,397,397,397
BEGIN DESCRIPTION:
HamlinFord Road - DS
END DESCRIPTION:
XS GIS Cut Line= 5
      1505923.96       952572.55      1505848.03       952484.23
      1505615.69       952383.54      1505518.10       952323.13
      1505457.68       952210.03
#Sta/Elev= 30
  4678.3  974.44  4697.9  972.09  4709.1  971.30  4742.3  967.21  4750.7  965.66
  4793.1  959.98  4834.0  955.11  4856.2  952.07  4861.4  950.42  4873.1  947.99
  4874.9  948.23  4884.1  947.08  4897.9  944.88  4907.3  939.50  4916.8  938.71
  4918.9  934.93  4945.0  925.73  5047.2  925.73  5063.9  934.93  5070.2  940.63
  5083.1  946.49  5091.2  951.10  5098.1  954.53  5104.5  954.41  5135.3  965.42
  5147.4  969.18  5153.0  972.03  5216.3  984.20  5254.3  992.80  5291.0  999.30
#Mann=3,-1,0
  4678.3    0.14       0  4918.9    0.04       0  5063.9    0.14       0
#XS Ineff=2,0
    0.00 4895.00  949.50 5105.00    0.00  949.50
Permanent Ineff=
       F       F
Bank Sta=4918.9,5063.9
XS Rating Curve= 0
Exp/Cntr=0.5,0.3

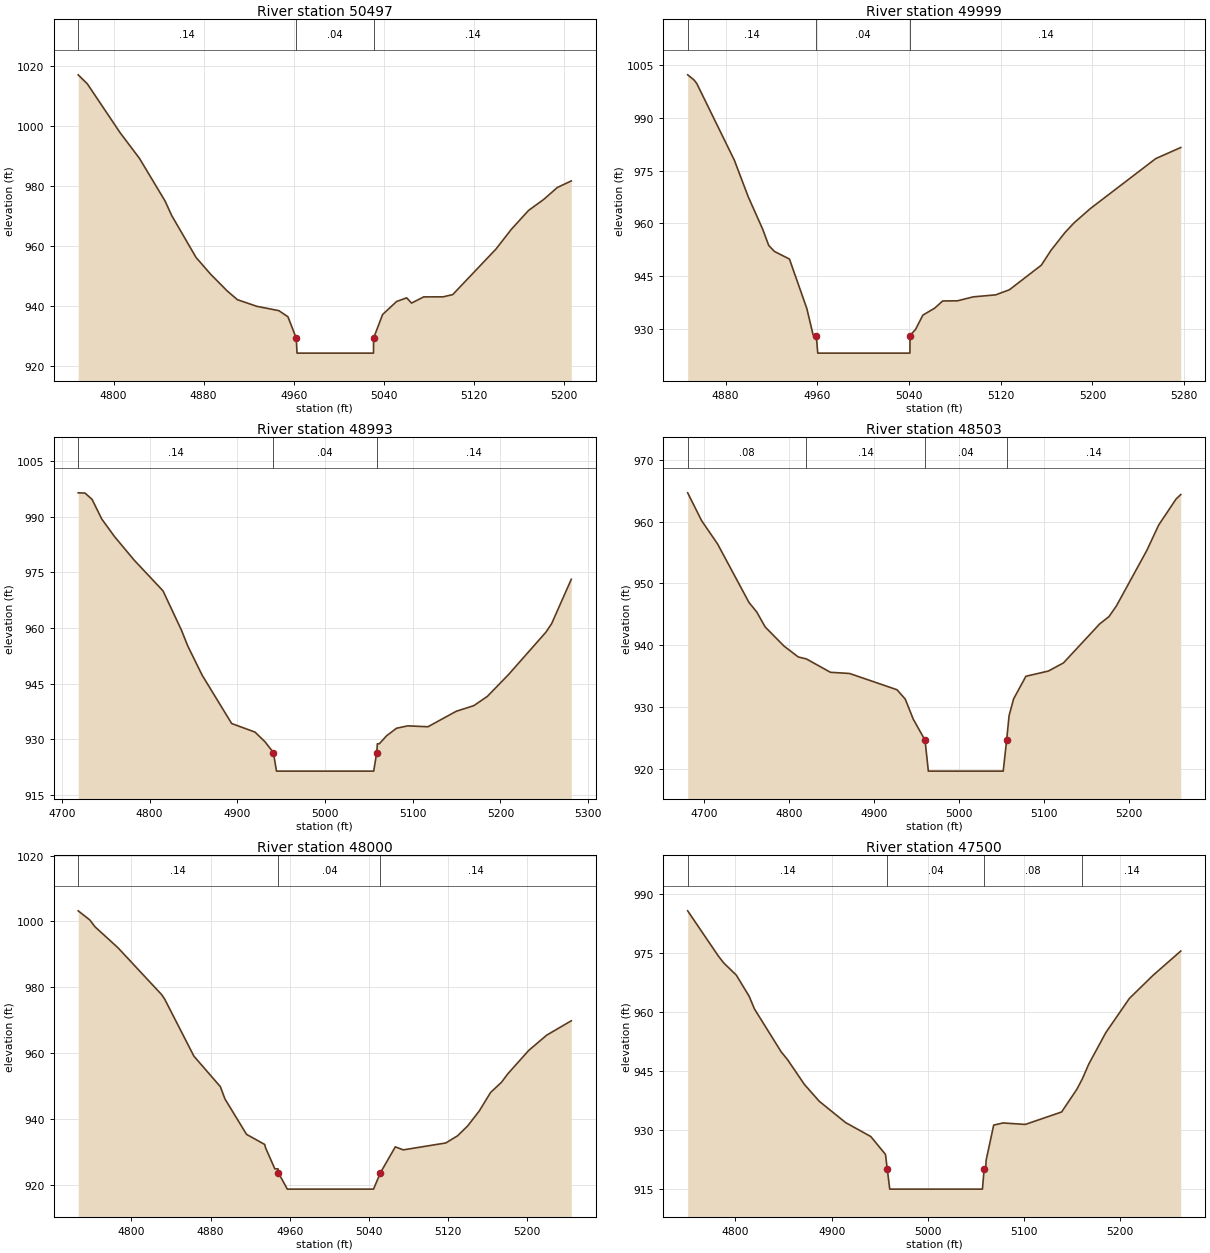
Type RM Length L Ch R = 1,50497,498,498,498
BEGIN DESCRIPTION:
Fisher River 101.0
END DESCRIPTION:
XS GIS Cut Line= 4
      1506010.64       952038.13      1505841.84       952036.58
      1505731.86       952014.89      1505578.51       951980.81
#Sta/Elev= 30
  4768.6 1017.14  4776.7 1014.14  4805.9  997.79  4823.0  989.28  4845.8  975.01
  4851.7  970.16  4873.3  956.19  4886.2  950.62  4900.8  945.07  4910.0  942.10
  4927.2  939.89  4946.8  938.44  4954.9  936.40  4962.3  929.26  4963.0  924.26
  5030.9  924.26  5031.0  929.26  5039.0  937.15  5051.5  941.51  5060.4  942.71
  5064.7  940.96  5075.5  943.03  5092.8  943.05  5101.3  943.80  5139.7  958.99
  5153.4  965.60  5168.7  971.90  5182.1  975.55  5194.2  979.54  5206.6  981.73
#Mann=3,-1,0
  4768.6    0.14       0  4962.3    0.04       0  5031.0    0.14       0
Bank Sta=4962.3,5031
XS Rating Curve= 0
Exp/Cntr=0.3,0.1

Type RM Length L Ch R = 1,49999,1006,1006,1006
BEGIN DESCRIPTION:
Fisher River 100.0
END DESCRIPTION:
XS GIS Cut Line= 3
      1505871.29       951458.26      1505627.92       951603.97
      1505500.78       951676.85
#Sta/Elev= 30
  4846.9 1002.23  4852.5 1000.76  4854.9  999.72  4887.6  977.97  4899.8  967.50
  4912.5  958.21  4917.6  953.71  4922.6  952.00  4935.7  949.83  4950.9  935.73
  4956.3  928.30  4959.1  928.08  4960.4  923.08  5040.8  923.08  5040.9  928.08
  5045.7  929.82  5052.1  933.89  5062.3  935.85  5069.4  937.91  5082.3  937.96
  5096.0  939.08  5115.6  939.65  5127.6  941.10  5155.5  948.11  5163.8  952.28
  5176.2  957.42  5183.9  960.10  5198.1  964.16  5255.3  978.41  5277.1  981.56
#Mann=3,-1,0
  4846.9    0.14       0  4959.1    0.04       0  5040.9    0.14       0
Bank Sta=4959.1,5040.9
XS Rating Curve= 0
Exp/Cntr=0.3,0.1

Type RM Length L Ch R = 1,48993,490,490,490
BEGIN DESCRIPTION:
Fisher River 98.0
END DESCRIPTION:
XS GIS Cut Line= 4
      1505493.06       950759.94      1505341.15       950716.53
      1505131.89       950707.23      1504942.78       950660.73
#Sta/Elev= 30
  4718.5  996.44  4726.3  996.37  4734.3  994.68  4745.4  989.37  4759.9  984.66
  4782.2  978.33  4815.2  970.02  4836.3  959.39  4843.4  955.18  4859.9  947.26
  4893.5  934.26  4920.1  931.95  4931.5  929.34  4941.1  926.43  4944.6  921.43
  5055.4  921.43  5058.9  926.43  5059.6  928.79  5061.8  928.79  5070.2  930.97
  5081.4  932.98  5094.2  933.63  5117.3  933.39  5149.5  937.56  5169.6  939.08
  5185.1  941.59  5209.4  947.52  5251.9  958.91  5258.3  961.18  5280.7  973.13
#Mann=3,-1,0
  4718.5    0.14       0  4941.1    0.04       0  5058.9    0.14       0
Bank Sta=4941.1,5058.9
XS Rating Curve= 0
Exp/Cntr=0.3,0.1

Type RM Length L Ch R = 1,48503,503,503,503
BEGIN DESCRIPTION:
Fisher River 97.0
END DESCRIPTION:
XS GIS Cut Line= 4
      1505561.24       950384.01      1505365.95       950246.08
      1505227.99       950216.62      1505037.31       950156.16
#Sta/Elev= 30
  4681.0  964.66  4697.4  960.16  4716.2  956.39  4753.2  946.92  4762.2  945.41
  4772.2  942.97  4794.3  939.89  4811.1  938.12  4820.7  937.80  4849.0  935.64
  4871.5  935.45  4927.3  932.82  4937.0  931.31  4946.5  928.05  4960.3  924.66
  4964.2  919.66  5052.3  919.66  5056.3  924.66  5059.2  928.63  5064.5  931.34
  5079.0  935.00  5105.4  935.84  5123.2  937.16  5165.7  943.45  5176.8  944.66
  5185.3  946.33  5221.2  955.33  5235.2  959.45  5255.8  963.68  5261.2  964.38
#Mann=4,-1,0
  4681.0    0.08       0  4820.7    0.14       0  4960.3    0.04       0
  5056.3    0.14       0
Bank Sta=4960.3,5056.3
XS Rating Curve= 0
Exp/Cntr=0.3,0.1

Type RM Length L Ch R = 1,48000,500,500,500
BEGIN DESCRIPTION:
Fisher River 96.0
END DESCRIPTION:
XS GIS Cut Line= 4
      1505658.96       949789.57      1505536.47       949772.52
      1505409.88       949742.38      1505174.95       949674.99
#Sta/Elev= 30
  4746.2 1003.23  4757.9 1000.47  4763.1  998.41  4786.2  992.09  4830.6  977.79
  4833.7  976.39  4863.1  959.16  4889.9  949.87  4894.5  946.16  4916.3  935.43
  4934.7  932.36  4935.4  931.44  4944.9  924.97  4948.2  924.96  4948.4  923.82
  4957.5  918.82  5044.6  918.82  5051.6  923.82  5066.6  931.64  5074.7  930.73
  5117.6  932.82  5129.5  934.99  5139.7  937.98  5151.6  942.60  5162.9  948.15
  5173.9  951.23  5180.2  953.77  5201.4  960.89  5219.6  965.53  5244.4  969.88
#Mann=3,-1,0
  4746.2    0.14       0  4948.4    0.04       0  5051.6    0.14       0
Bank Sta=4948.4,5051.6
XS Rating Curve= 0
Exp/Cntr=0.3,0.1

Type RM Length L Ch R = 1,47500,502,502,502
BEGIN DESCRIPTION:
Fisher River 95.0
END DESCRIPTION:
XS GIS Cut Line= 4
      1505764.35       949245.48      1505651.17       949267.18
      1505517.26       949255.06      1505255.94       949225.33
#Sta/Elev= 30
  4750.3  985.76  4782.0  974.32  4787.7  972.51  4800.9  969.38  4814.2  964.02
  4819.8  960.75  4847.6  949.83  4853.9  947.95  4871.7  941.55  4887.2  937.25
  4914.5  931.85  4940.7  928.29  4956.0  923.73  4957.9  919.90  4960.4  914.90
  5056.8  914.90  5058.5  919.90  5060.1  919.91  5060.6  922.23  5068.5  931.21
  5078.3  931.75  5101.3  931.37  5139.1  934.54  5155.0  940.34  5160.8  943.04
  5167.3  946.72  5185.2  954.80  5209.6  963.46  5234.2  969.34  5263.0  975.52
#Mann=4,-1,0
  4750.3    0.14       0  4957.9    0.04       0  5058.5    0.08       0
  5160.8    0.14       0
Bank Sta=4957.9,5058.5
XS Rating Curve= 0
Exp/Cntr=0.3,0.1

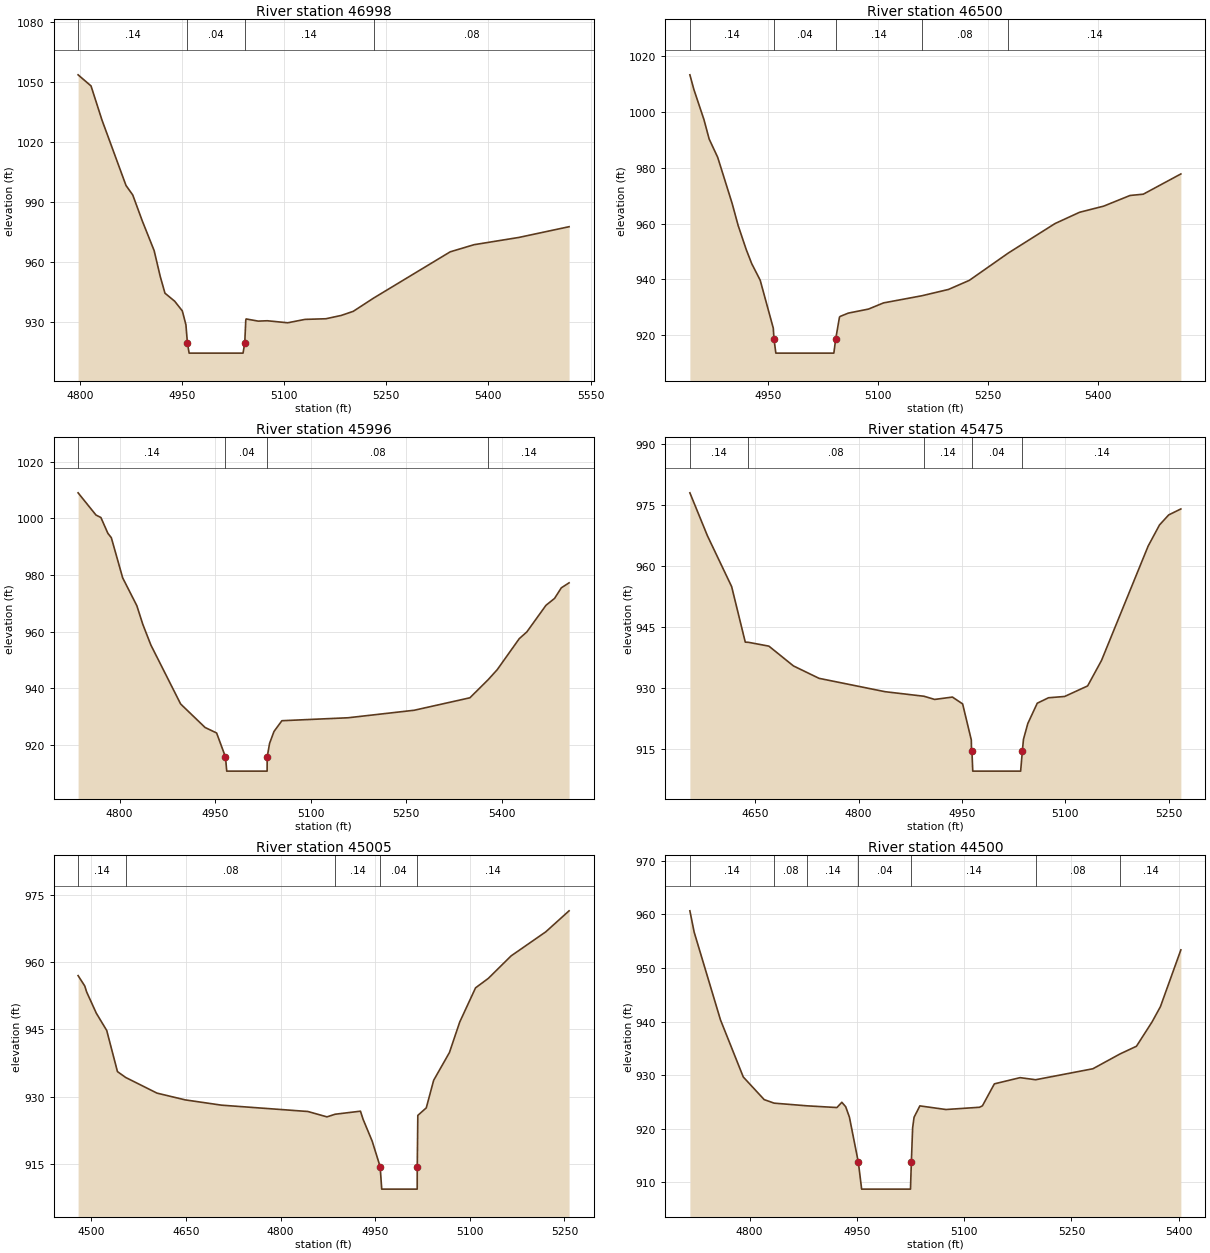
Type RM Length L Ch R = 1,46998,498,498,498
BEGIN DESCRIPTION:
Fisher River 94.0
END DESCRIPTION:
XS GIS Cut Line= 4
      1505625.03       948624.97      1505420.21       948854.85
      1505225.59       949052.40      1505203.20       949186.54
#Sta/Elev= 30
  4797.3 1053.50  4816.3 1047.96  4832.3 1031.01  4867.7  998.25  4877.6  993.52
  4891.7  980.48  4909.0  965.77  4917.9  952.93  4924.9  944.50  4939.2  940.48
  4950.4  935.65  4955.7  928.72  4957.9  919.57  4960.4  914.57  5039.6  914.57
  5042.1  919.57  5043.6  930.86  5044.1  931.63  5061.9  930.55  5075.2  930.73
  5105.2  929.72  5130.6  931.41  5161.3  931.73  5184.0  933.40  5201.5  935.44
  5231.6  942.09  5343.9  965.14  5378.9  968.70  5444.9  972.33  5518.5  977.68
#Mann=4,-1,0
  4797.3    0.14       0  4957.9    0.04       0  5042.1    0.14       0
  5231.6    0.08       0
Bank Sta=4957.9,5042.1
XS Rating Curve= 0
Exp/Cntr=0.3,0.1

Type RM Length L Ch R = 1,46500,504,504,504
BEGIN DESCRIPTION:
Fisher River 93.0
END DESCRIPTION:
XS GIS Cut Line= 4
      1505025.00       948475.01      1505026.89       948632.00
      1505020.28       949019.16      1504936.57       949113.72
#Sta/Elev= 30
  4843.0 1013.37  4848.5 1008.08  4862.2  997.33  4869.3  990.36  4881.0  983.77
  4900.7  967.24  4908.9  959.33  4919.9  950.73  4927.4  945.66  4939.0  939.70
  4956.9  922.49  4957.9  918.53  4960.4  913.53  5039.6  913.53  5042.1  918.53
  5047.3  926.44  5048.5  926.73  5059.4  927.89  5086.9  929.33  5107.5  931.55
  5160.0  934.12  5196.2  936.38  5224.6  939.63  5277.8  949.43  5341.7  960.02
  5375.2  964.06  5408.1  966.26  5444.1  970.09  5462.2  970.55  5513.5  977.81
#Mann=5,-1,0
  4843.0    0.14       0  4957.9    0.04       0  5042.1    0.14       0
  5160.0    0.08       0  5277.8    0.14       0
Bank Sta=4957.9,5042.1
XS Rating Curve= 0
Exp/Cntr=0.3,0.1

Type RM Length L Ch R = 1,45996,521,521,521
BEGIN DESCRIPTION:
Fisher River 92.0
END DESCRIPTION:
XS GIS Cut Line= 4
      1504629.63       948406.90      1504524.73       948558.76
      1504524.24       948712.24      1504640.49       949129.19
#Sta/Elev= 30
  4734.9 1009.02  4763.0 1001.18  4770.7 1000.31  4781.7  994.72  4787.1  993.18
  4804.9  979.02  4827.2  969.16  4836.4  962.69  4849.2  955.30  4895.9  934.51
  4934.3  926.21  4952.4  924.27  4966.3  915.81  4968.3  910.81  5031.7  910.81
  5031.8  915.81  5035.6  920.63  5042.5  924.81  5054.9  928.60  5158.8  929.64
  5262.6  932.29  5350.1  936.69  5378.9  943.11  5393.0  946.62  5427.6  957.56
  5439.5  959.94  5469.5  969.32  5483.0  971.76  5493.6  975.49  5505.8  977.26
#Mann=4,-1,0
  4734.9    0.14       0  4966.3    0.04       0  5031.8    0.08       0
  5378.9    0.14       0
Bank Sta=4966.3,5031.8
XS Rating Curve= 0
Exp/Cntr=0.3,0.1

Type RM Length L Ch R = 1,45475,470,470,470
BEGIN DESCRIPTION:
Fisher River 91.0
END DESCRIPTION:
XS GIS Cut Line= 4
      1504190.97       948285.95      1504014.26       948602.18
      1504005.18       948747.14      1503902.63       948924.64
#Sta/Elev= 30
  4555.2  978.02  4580.7  967.46  4615.8  954.99  4635.6  941.34  4640.2  941.30
  4669.9  940.36  4705.5  935.50  4742.7  932.45  4838.5  929.17  4895.0  928.05
  4910.4  927.27  4936.2  927.85  4951.0  926.17  4963.6  917.31  4963.9  914.73
  4964.5  914.66  4965.7  909.66  5035.2  909.66  5037.7  914.66  5039.3  917.48
  5045.6  921.36  5059.3  926.34  5075.6  927.68  5099.1  928.00  5132.4  930.59
  5152.5  936.83  5220.2  964.93  5236.7  970.13  5250.0  972.59  5267.7  974.06
#Mann=5,-1,0
  4555.2    0.14       0  4640.2    0.08       0  4895.0    0.14       0
  4964.5    0.04       0  5037.7    0.14       0
Bank Sta=4964.5,5037.7
XS Rating Curve= 0
Exp/Cntr=0.3,0.1

Type RM Length L Ch R = 1,45005,505,505,505
BEGIN DESCRIPTION:
Fisher River 90.0
END DESCRIPTION:
XS GIS Cut Line= 4
      1504012.71       948231.70      1503687.18       948437.87
      1503498.07       948577.38      1503437.61       948723.11
#Sta/Elev= 30
  4479.2  957.02  4489.8  954.70  4492.7  953.39  4508.1  948.62  4524.6  944.76
  4541.6  935.58  4554.5  934.28  4604.3  930.77  4649.1  929.26  4706.7  928.08
  4843.3  926.67  4873.6  925.47  4886.6  926.06  4926.7  926.74  4930.9  924.92
  4945.3  920.04  4957.9  914.33  4960.4  909.33  5016.6  909.33  5016.7  914.33
  5017.6  925.80  5031.0  927.48  5042.7  933.64  5067.7  939.84  5084.0  946.65
  5109.1  954.29  5129.4  956.41  5165.4  961.42  5220.3  966.79  5257.3  971.49
#Mann=5,-1,0
  4479.2    0.14       0  4554.5    0.08       0  4886.6    0.14       0
  4957.9    0.04       0  5016.7    0.14       0
Bank Sta=4957.9,5016.7
XS Rating Curve= 0
Exp/Cntr=0.3,0.1

Type RM Length L Ch R = 1,44500,490,490,490
BEGIN DESCRIPTION:
Fisher River 89.0
END DESCRIPTION:
XS GIS Cut Line= 5
      1503730.62       947937.16      1503597.37       948018.74
      1503470.69       948030.83      1503369.48       948026.78
      1503209.75       948282.86
#Sta/Elev= 30
  4716.5  960.66  4722.5  956.68  4759.3  940.30  4791.2  929.64  4820.4  925.42
  4834.3  924.76  4880.3  924.26  4922.1  923.94  4929.0  924.92  4934.4  924.09
  4939.6  922.15  4952.1  913.71  4956.7  908.71  5025.0  908.71  5026.2  913.71
  5028.0  920.15  5030.0  922.12  5038.1  924.25  5074.6  923.57  5121.5  923.99
  5125.6  924.26  5142.3  928.36  5178.3  929.52  5200.0  929.13  5280.1  931.18
  5318.1  933.95  5341.0  935.38  5362.9  939.94  5374.5  942.77  5403.1  953.37
#Mann=7,-1,0
  4716.5    0.14       0  4834.3    0.08       0  4880.3    0.14       0
  4952.1    0.04       0  5026.2    0.14       0  5200.0    0.08       0
  5318.1    0.14       0
Bank Sta=4952.1,5026.2
XS Rating Curve= 0
Exp/Cntr=0.3,0.1

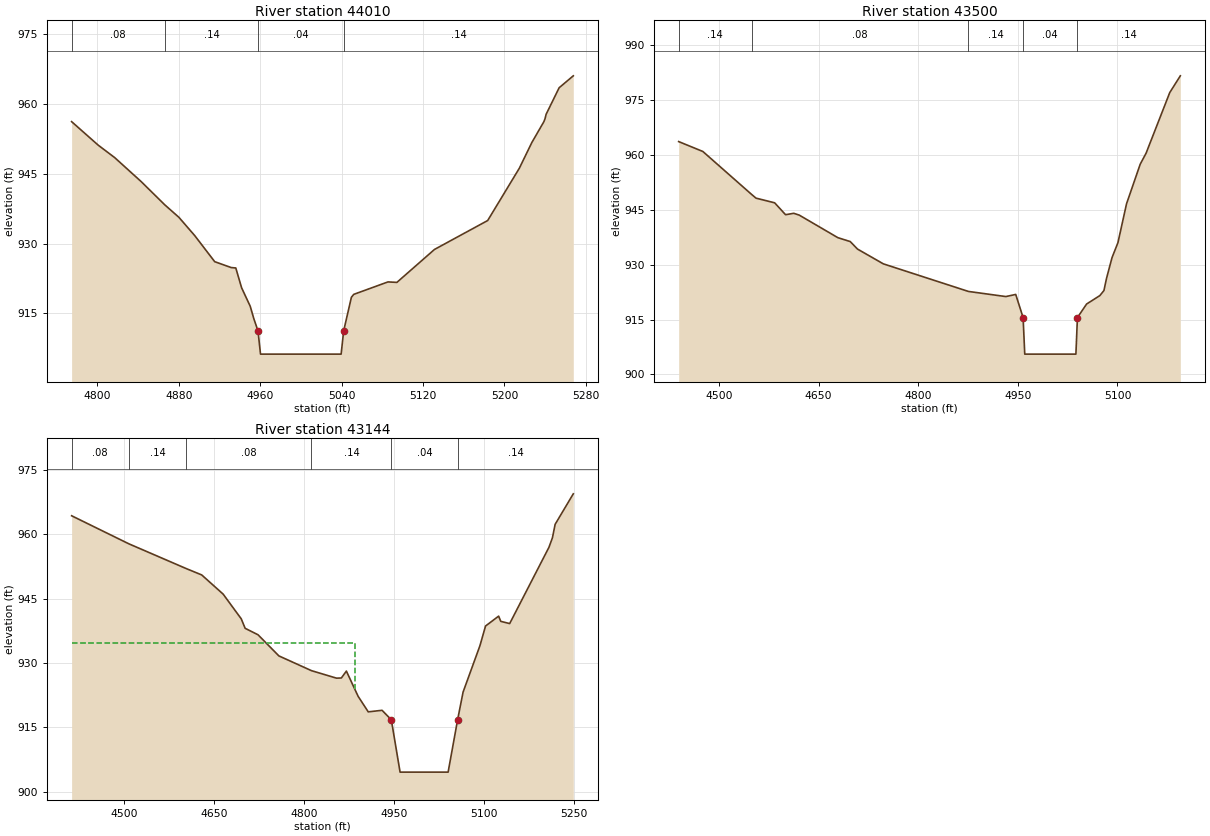
Type RM Length L Ch R = 1,44010,510,510,510
BEGIN DESCRIPTION:
Fisher River 88.0
END DESCRIPTION:
XS GIS Cut Line= 3
      1503637.60       947558.96      1503271.75       947535.70
      1503146.21       947521.75
#Sta/Elev= 30
  4774.8  956.14  4800.9  951.10  4817.1  948.43  4843.1  943.29  4866.4  938.28
  4880.2  935.62  4895.7  931.71  4915.4  926.10  4931.6  924.84  4936.1  924.75
  4941.8  920.51  4950.3  916.53  4953.9  913.82  4957.9  911.27  4960.4  906.27
  5039.6  906.27  5042.1  911.27  5049.7  918.47  5052.0  919.09  5085.6  921.76
  5094.4  921.66  5131.3  928.72  5183.6  934.93  5214.7  946.15  5227.0  951.67
  5238.8  956.13  5239.9  956.74  5241.0  957.71  5253.8  963.41  5267.7  965.97
#Mann=4,-1,0
  4774.8    0.08       0  4866.4    0.14       0  4957.9    0.04       0
  5042.1    0.14       0
Bank Sta=4957.9,5042.1
XS Rating Curve= 0
Exp/Cntr=0.3,0.1

Type RM Length L Ch R = 1,43500,356,356,356
BEGIN DESCRIPTION:
Fisher River 87.0
END DESCRIPTION:
XS GIS Cut Line= 5
      1503848.38       947307.80      1503791.72       947180.04
      1503395.80       947037.37      1503319.81       947016.42
      1503265.57       946914.14
#Sta/Elev= 30
  4439.4  963.63  4475.8  960.93  4549.4  949.16  4555.8  948.18  4583.9  946.90
  4600.3  943.65  4612.6  944.03  4620.8  943.55  4679.0  937.38  4697.7  936.31
  4708.6  934.26  4747.5  930.22  4875.6  922.68  4931.9  921.28  4946.8  921.86
  4957.9  915.55  4960.4  905.55  5037.4  905.55  5039.7  915.55  5053.5  919.24
  5073.4  921.54  5079.6  922.92  5083.4  926.18  5091.7  931.88  5100.7  936.03
  5113.6  946.62  5134.2  957.45  5143.1  960.48  5178.7  977.03  5194.6  981.60
#Mann=5,-1,0
  4439.4    0.14       0  4549.4    0.08       0  4875.6    0.14       0
  4957.9    0.04       0  5039.7    0.14       0
Bank Sta=4957.9,5039.7
XS Rating Curve= 0
Exp/Cntr=0.5,0.3

Type RM Length L Ch R = 1,43144,86,86,86
BEGIN DESCRIPTION:
NC Highway 268 - US
END DESCRIPTION:
XS GIS Cut Line= 4
      1504108.82       947010.22      1503776.29       946821.19
      1503455.25       946689.85      1503376.21       946760.38
#Sta/Elev= 30
  4413.1  964.31  4508.5  957.77  4603.9  952.01  4629.7  950.53  4665.4  946.06
  4695.6  940.29  4702.0  938.10  4723.5  936.59  4758.2  931.67  4812.4  928.24
  4854.1  926.49  4862.2  926.53  4870.6  928.13  4890.1  922.27  4907.0  918.64
  4930.0  919.00  4945.4  916.80  4960.0  904.60  5040.0  904.60  5055.8  916.80
  5064.9  923.24  5093.0  934.06  5102.3  938.63  5124.1  940.93  5127.6  939.72
  5142.5  939.20  5207.9  956.97  5213.7  959.19  5218.2  962.32  5248.4  969.42
#Mann=6,-1,0
  4413.1    0.08       0  4508.5    0.14       0  4603.9    0.08       0
  4812.4    0.14       0  4945.4    0.04       0  5055.8    0.14       0
#XS Ineff=2,0
    0.00 4885.00  934.60 5115.00    0.00  934.50
Permanent Ineff=
       F       F
Bank Sta=4945.4,5055.8
XS Rating Curve= 0
Exp/Cntr=0.5,0.3