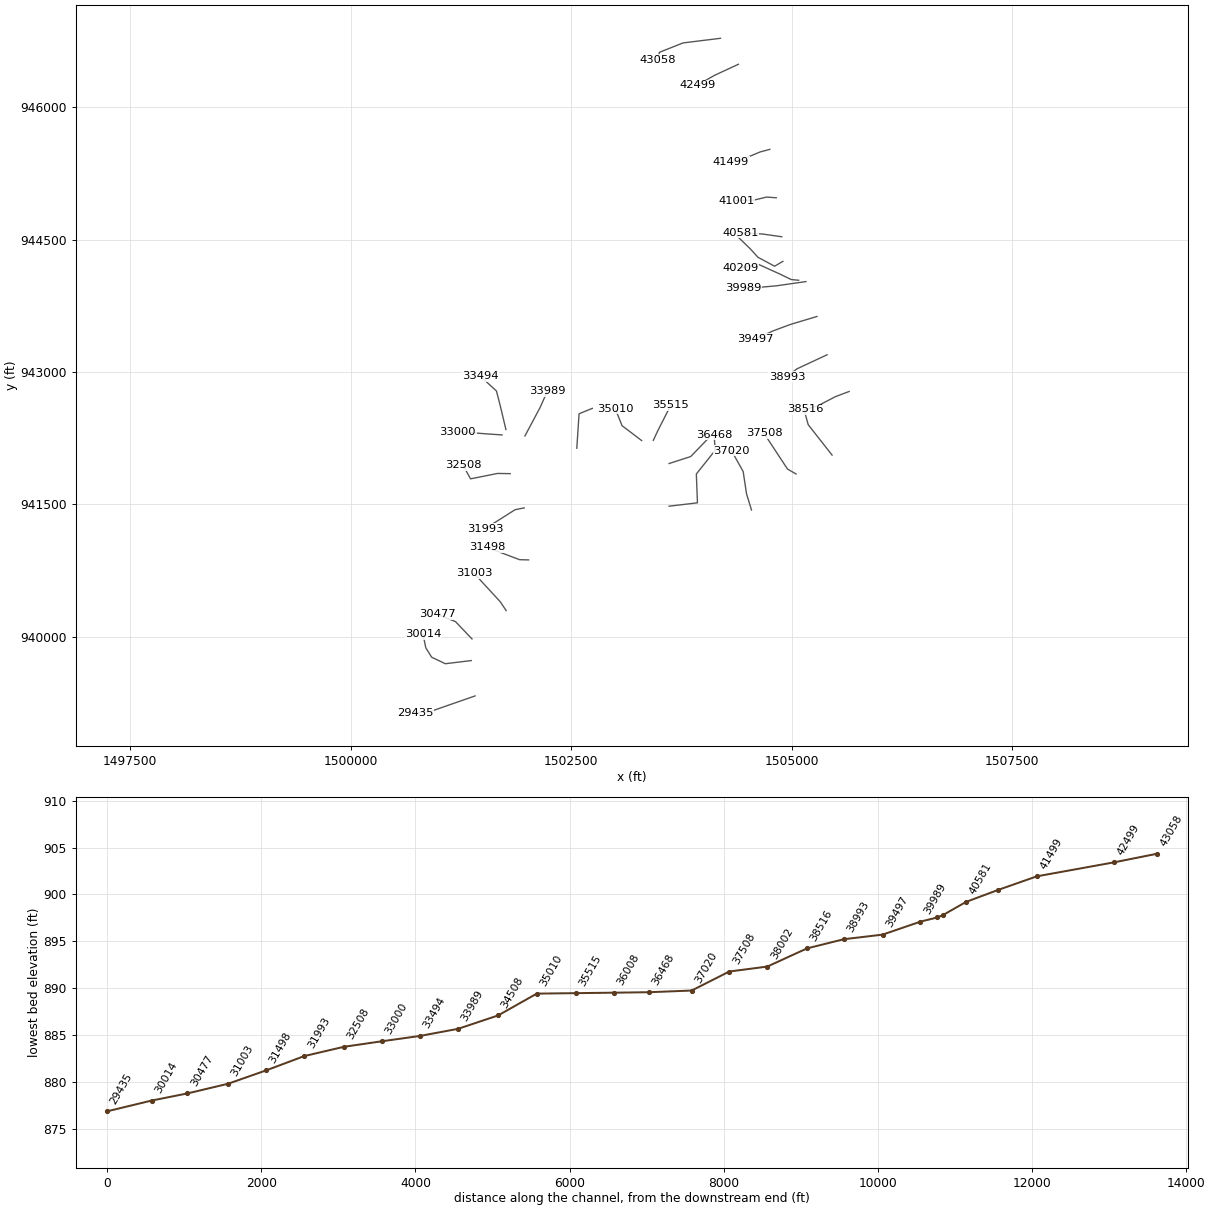
HEC-RAS study Fisher River.prj: Fisher River Limited Detail Study

--- Fisher River.g01 (geometry) --- (continued)

Type RM Length L Ch R =3,43101,,,
BEGIN DESCRIPTION:
NC Highway 268 - TOR
Structure ID: LDS_FR_04
Approximate Survey Structure
END DESCRIPTION:
Bridge Culvert--1,0,-1,-1,0
Deck Dist Width WeirC Skew NumUp NumDn MinLoCord MaxHiCord MaxSubmerge Is_Ogee
53,32,3,,41,41,,,0.95,0,1,1,,,
  4558.2  4718.5  4762.1  4805.5  4829.9  4895.0  4895.0  5105.0  5105.0  5120.4
  5130.4  5142.4  5149.3  5151.3  5161.2  5165.1  5166.4  5173.6  5183.0  5187.6
  5190.9  5196.3  5209.6  5218.3  5227.3  5231.5  5233.9  5239.8  5246.5  5253.7
  5258.2  5262.2  5275.7  5284.6  5297.8  5300.4  5317.8  5320.1  5329.0  5339.0
  5342.0
  944.20  937.61  936.12  934.98  934.74  934.60  934.60  934.60  934.60  934.64
  934.88  935.22  935.34  935.55  935.79  935.95  935.97  936.22  936.67  936.95
  937.10  937.74  938.19  938.85  939.22  939.50  939.57  939.98  940.13  940.51
  940.82  941.29  942.13  942.47  943.34  943.34  944.86  945.10  945.30  945.93
  946.25
  884.60  884.60  884.60  884.60  884.60  884.60  929.60  929.60  884.60  884.60
  884.60  884.60  884.60  884.60  884.60  884.60  884.60  884.60  884.60  884.60
  884.60  884.60  884.60  884.60  884.60  884.60  884.60  884.60  884.60  884.60
  884.60  884.60  884.60  884.60  884.60  884.60  884.60  884.60  884.60  884.60
  884.60
  4558.2  4718.5  4762.1  4805.5  4829.9  4895.0  4895.0  5105.0  5105.0  5120.4
  5130.4  5142.4  5149.3  5151.3  5161.2  5165.1  5166.4  5173.6  5183.0  5187.6
  5190.9  5196.3  5209.6  5218.3  5227.3  5231.5  5233.9  5239.8  5246.5  5253.7
  5258.2  5262.2  5275.7  5284.6  5297.8  5300.4  5317.8  5320.1  5329.0  5339.0
  5342.0
  944.20  937.61  936.12  934.98  934.74  934.60  934.60  934.60  934.60  934.64
  934.88  935.22  935.34  935.55  935.79  935.95  935.97  936.22  936.67  936.95
  937.10  937.74  938.19  938.85  939.22  939.50  939.57  939.98  940.13  940.51
  940.82  941.29  942.13  942.47  943.34  943.34  944.86  945.10  945.30  945.93
  946.25
  884.60  884.60  884.60  884.60  884.60  884.60  929.60  929.60  884.60  884.60
  884.60  884.60  884.60  884.60  884.60  884.60  884.60  884.60  884.60  884.60
  884.60  884.60  884.60  884.60  884.60  884.60  884.60  884.60  884.60  884.60
  884.60  884.60  884.60  884.60  884.60  884.60  884.60  884.60  884.60  884.60
  884.60
Pier Skew, UpSta & Num, DnSta & Num=,4947.5,2,4947.5,2,0,0,0,0,0
       3       3
  915.14  929.60
       3       3
  914.89  929.60
Pier Skew, UpSta & Num, DnSta & Num=,5052.5,2,5052.5,2,0,0,0,0,0
       3       3
  915.14  929.60
       3       3
  914.89  929.60
Abutment Skew #Up #Dn=,2,2
  4895.0  4922.0
  929.60  919.15
  4895.0  4922.0
  929.60  916.58
Abutment Skew #Up #Dn=,2,2
  5078.0  5105.0
  922.05  929.60
  5078.0  5105.0
  923.36  929.60
BR Coef=1,1,0,1.25,0,,,0.8,0,2,0,
WSPro=,,,, 1 ,,,, 0 ,,,, 0 ,,,,-1 ,-1 ,-1 , 0 , 0 , 0 , 0 , 0
BC Design=,,0,,0,,,,,,

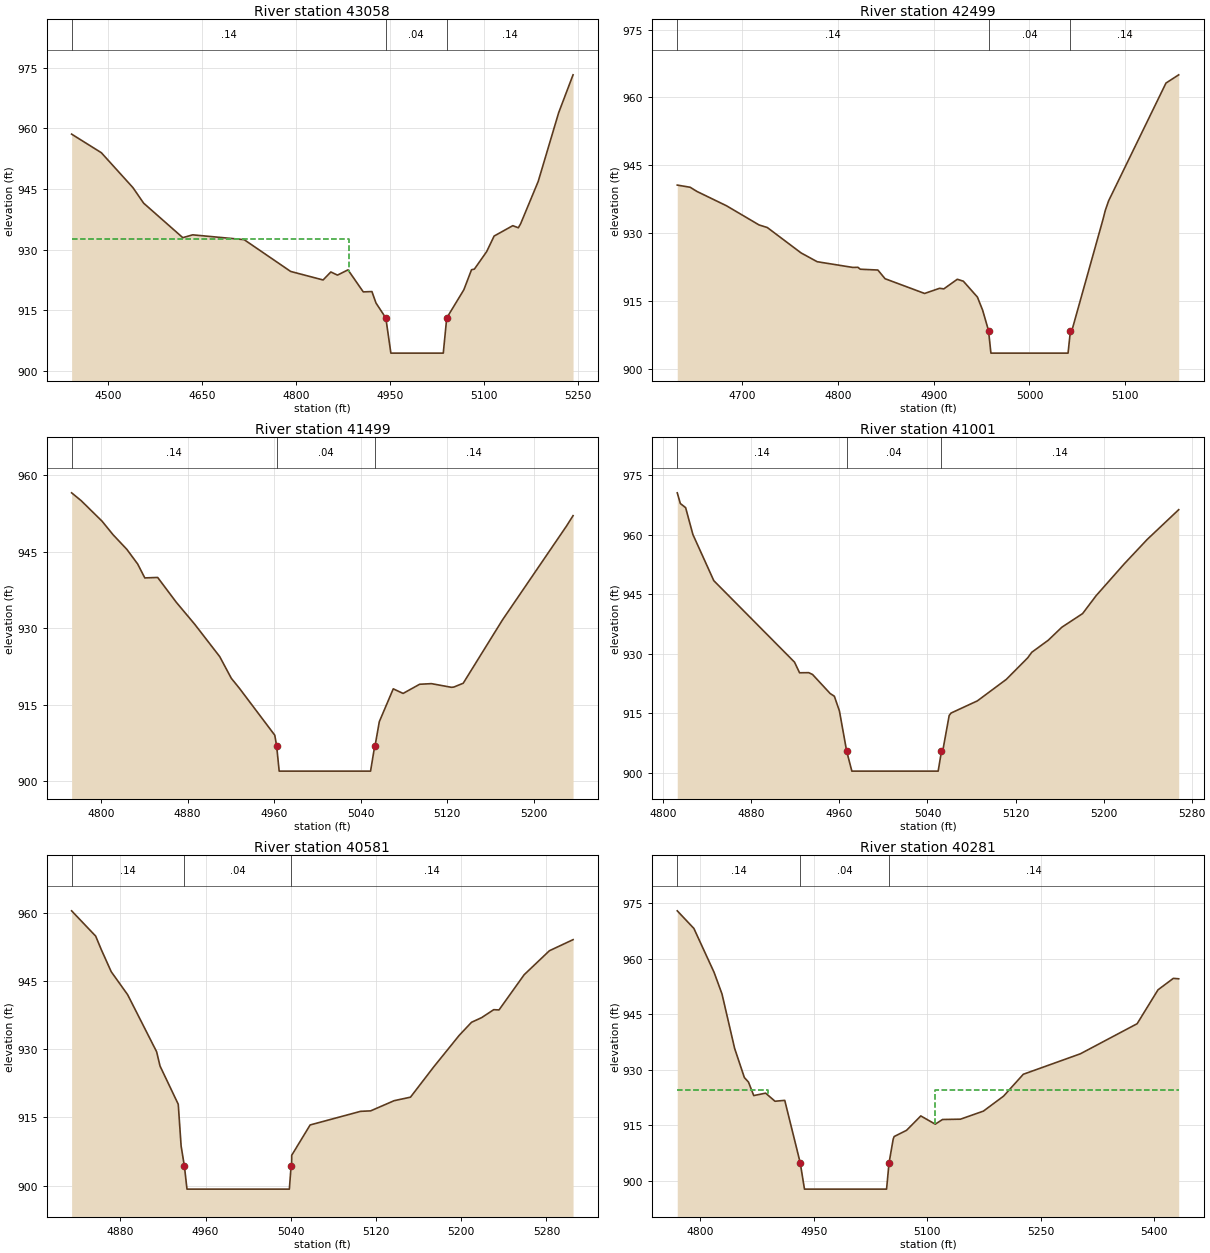
Type RM Length L Ch R = 1,43058,559,559,559
BEGIN DESCRIPTION:
NC Highway 268 - DS
END DESCRIPTION:
XS GIS Cut Line= 4
      1504192.49       946782.35      1503767.78       946729.98
      1503499.03       946622.97      1503484.11       946540.51
#Sta/Elev= 30
  4441.6  958.56  4489.1  953.96  4539.6  945.31  4556.6  941.48  4619.2  932.93
  4635.0  933.63  4717.2  932.44  4791.5  924.57  4843.3  922.46  4855.7  924.44
  4866.3  923.66  4883.1  924.96  4907.5  919.51  4921.3  919.59  4927.8  916.76
  4943.5  913.05  4951.6  904.35  5035.3  904.35  5040.8  913.05  5068.1  920.02
  5080.4  924.99  5085.0  925.15  5104.6  929.48  5116.5  933.33  5146.3  935.90
  5155.2  935.38  5158.8  936.35  5186.9  946.84  5219.6  963.86  5242.6  973.24
#Mann=3,-1,0
  4441.6    0.14       0  4943.5    0.04       0  5040.8    0.14       0
#XS Ineff=2,0
    0.00 4885.00  932.50 5115.00    0.00  932.50
Permanent Ineff=
       F       F
Bank Sta=4943.5,5040.8
XS Rating Curve= 0
Exp/Cntr=0.5,0.3

Type RM Length L Ch R = 1,42499,1000,1000,1000
BEGIN DESCRIPTION:
Fisher River 85.0
END DESCRIPTION:
XS GIS Cut Line= 3
      1504395.57       946487.82      1504124.31       946362.27
      1503928.96       946250.64
#Sta/Elev= 30
  4632.0  940.60  4645.5  940.12  4652.6  939.19  4683.4  936.03  4717.4  931.79
  4726.1  931.21  4761.4  925.59  4778.2  923.65  4815.3  922.39  4820.8  922.41
  4823.2  921.99  4841.6  921.81  4849.1  919.89  4890.4  916.63  4906.1  917.77
  4910.5  917.64  4924.6  919.77  4930.9  919.34  4945.6  915.83  4951.0  912.96
  4957.2  908.43  4959.7  903.43  5040.3  903.43  5042.8  908.43  5044.3  908.43
  5076.8  933.01  5079.2  935.00  5082.7  937.13  5142.6  963.17  5155.9  964.99
#Mann=3,-1,0
  4632.0    0.14       0  4957.2    0.04       0  5042.8    0.14       0
Bank Sta=4957.2,5042.8
XS Rating Curve= 0
Exp/Cntr=0.3,0.1

Type RM Length L Ch R = 1,41499,498,498,498
BEGIN DESCRIPTION:
Fisher River 83.0
END DESCRIPTION:
XS GIS Cut Line= 4
      1504752.12       945523.66      1504642.05       945494.21
      1504445.19       945412.05      1504311.87       945382.60
#Sta/Elev= 30
  4772.7  956.53  4781.6  954.98  4800.9  950.96  4811.0  948.32  4823.8  945.44
  4833.8  942.57  4840.4  939.84  4852.3  939.93  4869.6  935.04  4886.6  930.74
  4909.7  924.40  4920.4  920.15  4927.8  918.22  4960.6  908.99  4962.3  906.94
  4964.7  901.94  5049.2  901.94  5053.1  906.94  5053.4  906.94  5057.3  911.64
  5070.2  918.08  5079.3  917.18  5094.6  918.98  5105.5  919.10  5124.0  918.38
  5126.2  918.43  5134.9  919.18  5171.3  931.63  5230.3  949.97  5236.5  952.05
#Mann=3,-1,0
  4772.7    0.14       0  4962.3    0.04       0  5053.1    0.14       0
Bank Sta=4962.3,5053.1
XS Rating Curve= 0
Exp/Cntr=0.3,0.1

Type RM Length L Ch R = 1,41001,420,420,420
BEGIN DESCRIPTION:
Fisher River 82.0
END DESCRIPTION:
XS GIS Cut Line= 4
      1504825.00       944975.00      1504714.91       944982.67
      1504572.30       944948.57      1504373.85       944943.91
#Sta/Elev= 30
  4812.7  970.51  4815.5  967.82  4820.3  966.78  4826.9  960.03  4845.9  948.41
  4919.2  927.92  4923.8  925.24  4932.1  925.27  4935.6  924.81  4951.6  920.02
  4955.4  919.34  4960.0  915.65  4966.6  905.50  4971.3  900.50  5049.7  900.50
  5052.7  905.50  5053.8  905.50  5059.7  914.49  5061.4  915.11  5085.3  918.17
  5111.6  923.58  5131.0  928.99  5134.7  930.39  5149.8  933.45  5162.0  936.69
  5180.9  940.13  5193.1  944.61  5218.7  952.63  5239.5  958.76  5268.2  966.27
#Mann=3,-1,0
  4812.7    0.14       0  4966.6    0.04       0  5052.7    0.14       0
Bank Sta=4966.6,5052.7
XS Rating Curve= 0
Exp/Cntr=0.3,0.1

Type RM Length L Ch R = 1,40581,300,300,300
BEGIN DESCRIPTION:
Fisher River 81.0
END DESCRIPTION:
XS GIS Cut Line= 3
      1504887.00       944533.13      1504668.40       944564.14
      1504418.88       944578.09
#Sta/Elev= 29
  4834.3  960.49  4856.9  954.92  4862.2  951.93  4871.5  947.08  4886.9  942.02
  4914.1  929.46  4917.3  926.32  4934.4  917.90  4937.1  908.69  4940.2  904.21
  4942.6  899.21  5038.7  899.21  5040.3  904.21  5040.8  904.28  5040.9  906.66
  5058.2  913.34  5105.6  916.34  5115.0  916.44  5137.0  918.68  5152.4  919.46
  5174.2  926.12  5198.2  933.09  5209.7  935.95  5219.1  936.96  5230.5  938.72
  5235.5  938.67  5259.1  946.42  5282.8  951.70  5305.0  954.14
#Mann=3,-1,0
  4834.3    0.14       0  4940.2    0.04       0  5040.3    0.14       0
Bank Sta=4940.2,5040.3
XS Rating Curve= 0
Exp/Cntr=0.5,0.3

Type RM Length L Ch R = 1,40281,72,72,72
BEGIN DESCRIPTION:
Rock Ford Road - US
END DESCRIPTION:
XS GIS Cut Line= 5
      1504899.93       944254.02      1504806.32       944199.31
      1504617.82       944300.25      1504531.48       944395.10
      1504378.54       944543.20
#Sta/Elev= 30
  4769.4  973.01  4791.4  968.25  4818.1  956.39  4828.6  950.53  4845.3  935.83
  4858.2  927.95  4863.6  926.74  4870.6  923.08  4886.3  923.74  4898.7  921.55
  4911.6  921.79  4932.1  904.90  4937.7  897.80  5046.3  897.80  5049.6  904.90
  5055.1  911.34  5056.4  912.02  5072.8  913.70  5091.6  917.58  5110.7  915.36
  5120.4  916.62  5144.0  916.70  5174.4  918.88  5201.1  922.93  5227.2  928.84
  5302.7  934.37  5377.8  942.50  5405.4  951.66  5425.7  954.76  5432.8  954.64
#Mann=3,-1,0
  4769.4    0.14       0  4932.1    0.04       0  5049.6    0.14       0
#XS Ineff=2,0
    0.00 4890.00  924.50 5110.00    0.00  924.50
Permanent Ineff=
       F       F
Bank Sta=4932.1,5049.6
XS Rating Curve= 0
Exp/Cntr=0.5,0.3

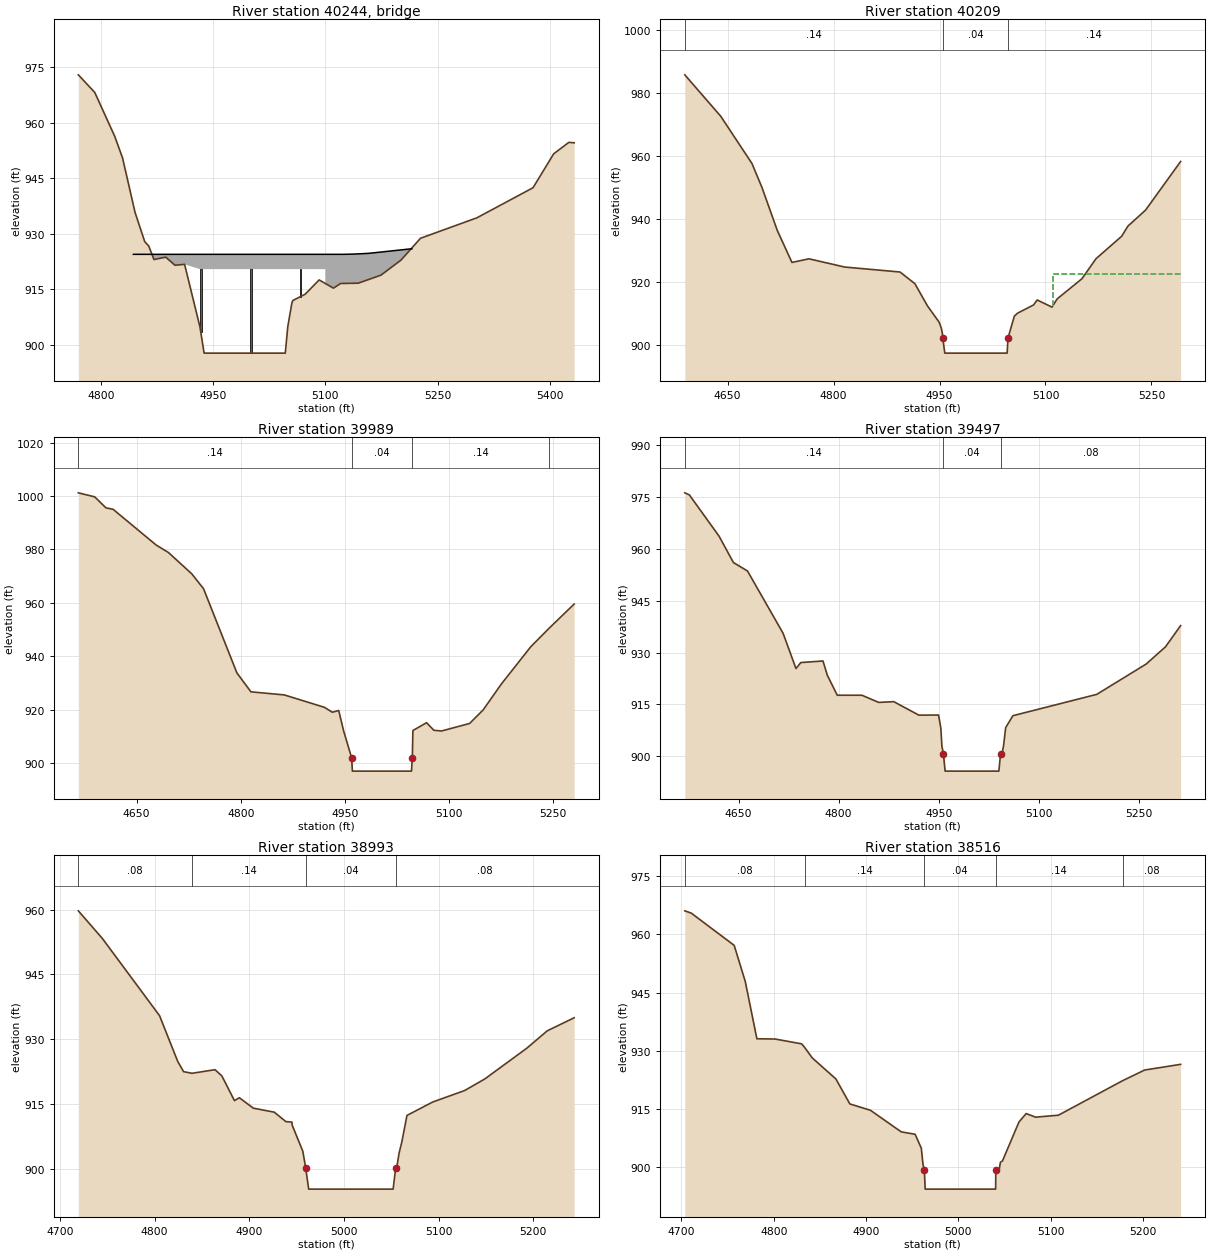
Type RM Length L Ch R =3,40244,,,
BEGIN DESCRIPTION:
Rock Ford Road - TOR
Structure ID: LDS_FR_03
Approximate Survey Structure
END DESCRIPTION:
Bridge Culvert--1,0,-1,-1,0
Deck Dist Width WeirC Skew NumUp NumDn MinLoCord MaxHiCord MaxSubmerge Is_Ogee
19.5,35,3,,10,10,,,0.95,0,1,1,,,
  4843.1  4900.0  4900.0  5100.0  5100.0  5123.7  5137.0  5146.5  5157.6  5215.7
  924.50  924.50  924.50  924.50  924.50  924.50  924.56  924.65  924.76  926.01
  877.80  877.80  920.50  920.50  877.80  877.80  877.80  877.80  877.80  877.80
  4843.1  4900.0  4900.0  5100.0  5100.0  5123.7  5137.0  5146.5  5157.6  5215.7
  924.50  924.50  924.50  924.50  924.50  924.50  924.56  924.65  924.76  926.01
  877.80  877.80  920.50  920.50  877.80  877.80  877.80  877.80  877.80  877.80
Pier Skew, UpSta & Num, DnSta & Num=,4933.3,2,4933.3,2,0,0,0,0,0
     2.5     2.5
  906.87  920.50
     2.5     2.5
  914.62  920.50
Pier Skew, UpSta & Num, DnSta & Num=,5000,2,5000,2,0,0,0,0,0
     2.5     2.5
  901.80  920.50
     2.5     2.5
  901.55  920.50
Pier Skew, UpSta & Num, DnSta & Num=,5066.7,2,5066.7,2,0,0,0,0,0
     2.5     2.5
  913.39  920.50
     2.5     2.5
  911.24  920.50
Abutment Skew #Up #Dn=,2,2
  4900.0  4925.0
  920.50  912.62
  4900.0  4925.0
  920.50  916.27
Abutment Skew #Up #Dn=,2,2
  5075.0  5100.0
  914.17  920.50
  5075.0  5100.0
  912.07  920.50
BR Coef=1,1,0,1.25,0,,,0.8,0,2,0,
WSPro=,,,, 1 ,,,, 0 ,,,, 0 ,,,,-1 ,-1 ,-1 , 0 , 0 , 0 , 0 , 0
BC Design=,,0,,0,,,,,,

Type RM Length L Ch R = 1,40209,220,220,220
BEGIN DESCRIPTION:
Rock Ford Road - DS
END DESCRIPTION:
XS GIS Cut Line= 5
      1505078.70       944040.01      1504994.03       944048.20
      1504865.91       944110.54      1504618.80       944222.34
      1504420.36       944178.93
#Sta/Elev= 30
  4589.4  985.72  4640.3  972.59  4684.4  957.66  4698.7  950.01  4720.3  936.44
  4741.1  926.28  4765.2  927.43  4815.8  924.82  4894.1  923.25  4915.2  919.53
  4932.9  912.53  4949.6  907.31  4952.5  905.49  4954.4  903.36  4954.6  902.29
  4957.5  897.55  5045.7  897.55  5046.9  902.29  5055.9  909.26  5060.4  910.20
  5083.2  912.82  5088.2  914.39  5109.2  912.13  5116.6  914.75  5151.6  921.11
  5171.5  927.46  5207.9  934.59  5216.7  937.79  5241.7  942.87  5291.3  958.26
#Mann=3,-1,0
  4589.4    0.14       0  4954.6    0.04       0  5046.9    0.14       0
#XS Ineff=2,0
    0.00 4890.00  922.50 5110.00    0.00  922.50
Permanent Ineff=
       F       F
Bank Sta=4954.6,5046.9
XS Rating Curve= 0
Exp/Cntr=0.5,0.3

Type RM Length L Ch R = 1,39989,492,492,492
BEGIN DESCRIPTION:
Fisher River 80.0
END DESCRIPTION:
XS GIS Cut Line= 4
      1505161.77       944025.13      1504824.82       943976.63
      1504667.53       943962.86      1504452.14       943953.66
#Sta/Elev= 30
  4566.1 1001.18  4589.7  999.67  4605.9  995.56  4616.1  995.03  4678.2  981.65
  4695.8  978.87  4729.5  970.87  4746.4  965.31  4794.4  933.84  4814.6  926.76
  4862.6  925.60  4920.2  920.99  4931.8  919.13  4941.0  919.77  4948.2  912.02
  4959.6  902.10  4960.7  897.10  5045.8  897.10  5047.0  902.10  5047.8  911.87
  5047.9  912.29  5067.5  915.21  5078.0  912.38  5089.0  912.11  5129.4  914.92
  5149.0  919.99  5174.9  929.58  5217.6  943.64  5244.0  950.55  5280.0  959.58
#Mann=4,-1,0
  4566.1    0.14       0  4959.6    0.04       0  5047.0    0.14       0
  5244.0    0.08       0
Bank Sta=4959.6,5047
XS Rating Curve= 0
Exp/Cntr=0.3,0.1

Type RM Length L Ch R = 1,39497,504,504,504
BEGIN DESCRIPTION:
Fisher River 79.0
END DESCRIPTION:
XS GIS Cut Line= 4
      1505286.84       943629.53      1504988.17       943540.19
      1504789.09       943466.17      1504590.01       943374.28
#Sta/Elev= 30
  4569.4  976.23  4576.2  975.64  4620.8  963.68  4642.3  956.06  4663.4  953.62
  4716.8  935.58  4736.1  925.39  4743.3  927.12  4776.6  927.58  4783.1  923.44
  4798.0  917.67  4835.1  917.66  4860.2  915.59  4882.7  915.81  4920.3  911.91
  4949.9  911.94  4953.3  908.14  4954.9  902.92  4957.2  900.71  4959.7  895.71
  5040.3  895.71  5042.8  900.71  5044.9  900.73  5047.3  903.00  5050.5  908.31
  5061.4  911.75  5187.1  917.92  5261.2  926.70  5290.1  931.67  5312.8  937.81
#Mann=3,-1,0
  4569.4    0.14       0  4957.2    0.04       0  5042.8    0.08       0
Bank Sta=4957.2,5042.8
XS Rating Curve= 0
Exp/Cntr=0.3,0.1

Type RM Length L Ch R = 1,38993,477,477,477
BEGIN DESCRIPTION:
Fisher River 78.0
END DESCRIPTION:
XS GIS Cut Line= 3
      1505401.60       943195.61      1505057.08       943034.83
      1504944.77       942945.49
#Sta/Elev= 30
  4719.5  959.72  4744.9  953.31  4805.3  935.42  4824.5  924.81  4830.7  922.44
  4839.6  922.07  4863.9  922.90  4871.1  921.46  4884.4  915.73  4889.6  916.40
  4904.3  913.99  4926.5  913.05  4938.7  910.87  4945.1  910.75  4945.4  910.03
  4956.6  904.01  4959.6  900.22  4962.8  895.22  5052.0  895.22  5054.7  900.22
  5055.8  900.22  5058.3  903.58  5061.3  906.27  5066.6  912.30  5093.8  915.41
  5127.4  918.06  5148.8  920.75  5193.0  927.85  5214.8  931.91  5243.2  934.94
#Mann=4,-1,0
  4719.5    0.08       0  4839.6    0.14       0  4959.6    0.04       0
  5054.7    0.08       0
Bank Sta=4959.6,5054.7
XS Rating Curve= 0
Exp/Cntr=0.3,0.1

Type RM Length L Ch R = 1,38516,514,514,514
BEGIN DESCRIPTION:
Fisher River 77.0
END DESCRIPTION:
XS GIS Cut Line= 4
      1505651.76       942779.60      1505496.08       942720.90
      1505304.66       942621.36      1505156.66       942575.43
#Sta/Elev= 30
  4703.6  966.10  4710.6  965.51  4757.1  957.18  4769.1  947.87  4781.7  933.06
  4801.4  933.00  4830.2  931.75  4833.4  930.83  4841.7  928.12  4867.3  922.68
  4882.4  916.24  4904.7  914.60  4938.0  909.03  4953.1  908.41  4959.8  904.80
  4961.6  900.67  4963.1  899.24  4964.0  894.24  5040.3  894.24  5040.5  899.24
  5044.3  899.47  5045.5  901.18  5047.7  901.52  5065.6  911.58  5073.4  913.75
  5083.6  912.82  5108.3  913.33  5177.8  922.23  5201.7  924.99  5240.7  926.46
#Mann=5,-1,0
  4703.6    0.08       0  4833.4    0.14       0  4963.1    0.04       0
  5040.5    0.14       0  5177.8    0.08       0
Bank Sta=4963.1,5040.5
XS Rating Curve= 0
Exp/Cntr=0.3,0.1

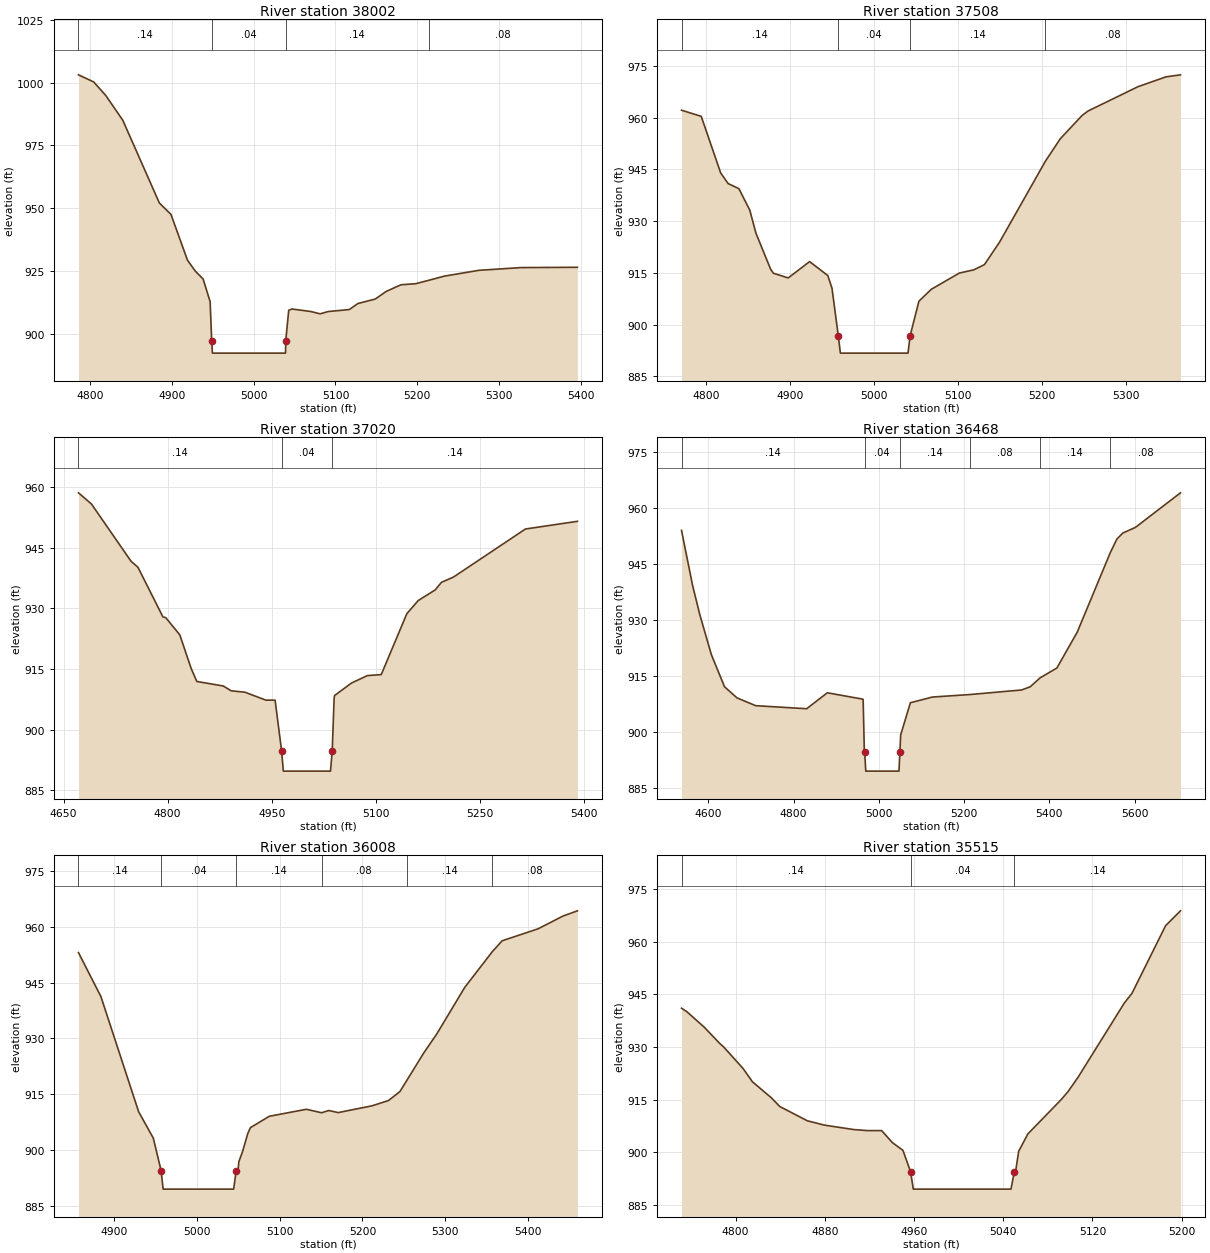
Type RM Length L Ch R = 1,38002,494,494,494
BEGIN DESCRIPTION:
Fisher River 76.0
END DESCRIPTION:
XS GIS Cut Line= 3
      1505457.79       942058.58      1505187.25       942403.14
      1505141.31       942569.02
#Sta/Elev= 30
  4785.7 1003.14  4804.3 1000.31  4819.0  994.94  4839.8  985.10  4884.6  952.10
  4898.8  947.56  4919.0  929.31  4928.7  924.90  4938.1  921.83  4946.7  912.81
  4948.6  897.30  4949.5  892.30  5038.9  892.30  5039.2  897.30  5042.8  909.35
  5046.7  909.88  5069.7  908.88  5081.2  907.95  5091.0  908.86  5116.8  909.65
  5127.5  912.06  5148.6  913.84  5162.2  916.91  5180.2  919.53  5198.1  919.95
  5214.3  921.32  5233.0  922.96  5275.4  925.28  5326.9  926.37  5395.9  926.49
#Mann=4,-1,0
  4785.7    0.14       0  4948.6    0.04       0  5039.2    0.14       0
  5214.3    0.08       0
Bank Sta=4948.6,5039.2
XS Rating Curve= 0
Exp/Cntr=0.3,0.1

Type RM Length L Ch R = 1,37508,488,488,488
BEGIN DESCRIPTION:
Fisher River 75.0
END DESCRIPTION:
XS GIS Cut Line= 3
      1505049.40       941844.20      1504952.44       941900.33
      1504687.01       942303.58
#Sta/Elev= 30
  4770.3  962.16  4793.8  960.38  4817.0  943.98  4825.9  940.90  4838.7  939.43
  4851.7  933.19  4859.0  926.55  4876.5  916.10  4879.8  914.92  4897.5  913.56
  4923.0  918.29  4944.7  914.25  4949.7  910.56  4957.2  896.77  4959.7  891.77
  5040.3  891.77  5042.8  896.77  5053.3  906.81  5068.0  910.26  5101.6  914.98
  5118.6  915.89  5131.4  917.41  5149.4  923.91  5204.0  947.35  5221.8  953.87
  5247.8  960.63  5254.8  961.91  5314.5  968.98  5347.8  971.82  5365.1  972.41
#Mann=4,-1,0
  4770.3    0.14       0  4957.2    0.04       0  5042.8    0.14       0
  5204.0    0.08       0
Bank Sta=4957.2,5042.8
XS Rating Curve= 0
Exp/Cntr=0.3,0.1

Type RM Length L Ch R = 1,37020,552,552,552
BEGIN DESCRIPTION:
Fisher River 74.0
END DESCRIPTION:
XS GIS Cut Line= 4
      1504544.08       941435.78      1504487.92       941619.58
      1504449.64       941872.26      1504316.92       942109.62
#Sta/Elev= 30
  4671.4  958.58  4690.1  955.82  4747.1  941.68  4757.2  940.16  4793.2  927.89
  4797.3  927.70  4817.5  923.46  4833.9  915.15  4842.1  911.92  4880.2  910.80
  4891.8  909.60  4911.4  909.27  4941.6  907.30  4955.0  907.29  4964.4  894.74
  4966.9  889.74  5034.9  889.74  5037.4  894.74  5040.1  907.58  5040.7  908.42
  5065.0  911.51  5088.1  913.37  5108.1  913.62  5145.0  928.67  5161.4  931.93
  5185.8  934.55  5195.1  936.46  5212.1  937.72  5316.1  949.63  5391.1  951.53
#Mann=3,-1,0
  4671.4    0.14       0  4964.4    0.04       0  5037.4    0.14       0
Bank Sta=4964.4,5037.4
XS Rating Curve= 0
Exp/Cntr=0.3,0.1

Type RM Length L Ch R = 1,36468,460,460,460
BEGIN DESCRIPTION:
Fisher River 73.0
END DESCRIPTION:
XS GIS Cut Line= 5
      1503609.94       941479.21      1503931.52       941517.49
      1503918.76       941844.18      1504132.66       942112.57
      1504120.39       942288.25
#Sta/Elev= 30
  4537.3  953.99  4563.4  939.19  4580.2  931.44  4607.2  920.78  4638.1  912.15
  4667.4  909.16  4711.3  907.08  4830.8  906.26  4879.2  910.53  4963.0  908.81
  4963.3  908.33  4966.1  894.56  4966.9  894.56  4969.4  889.56  5047.3  889.56
  5049.3  894.56  5051.3  899.26  5074.0  907.86  5125.7  909.39  5213.9  910.06
  5334.8  911.28  5355.1  912.14  5378.4  914.54  5417.5  917.15  5465.3  926.75
  5542.9  948.06  5558.4  951.69  5572.7  953.32  5601.4  954.77  5707.4  964.05
#Mann=6,-1,0
  4537.3    0.14       0  4966.9    0.04       0  5049.3    0.14       0
  5213.9    0.08       0  5378.4    0.14       0  5542.9    0.08       0
Bank Sta=4966.9,5049.3
XS Rating Curve= 0
Exp/Cntr=0.3,0.1

Type RM Length L Ch R = 1,36008,493,493,493
BEGIN DESCRIPTION:
Fisher River 72.0
END DESCRIPTION:
XS GIS Cut Line= 3
      1503609.90       941962.85      1503854.95       942041.99
      1504094.89       942289.58
#Sta/Elev= 30
  4857.2  953.05  4884.3  941.22  4929.8  910.31  4947.5  903.21  4956.9  894.51
  4959.4  889.51  5044.5  889.51  5047.6  894.51  5049.8  894.51  5050.8  896.89
  5055.3  899.61  5061.4  904.34  5064.7  906.02  5087.5  909.08  5132.4  910.96
  5150.6  910.03  5159.3  910.63  5170.7  910.07  5211.4  911.88  5231.4  913.30
  5245.2  915.71  5253.6  918.74  5274.1  926.13  5289.6  931.16  5323.4  943.69
  5356.6  953.26  5368.6  956.22  5411.9  959.43  5442.1  962.87  5459.5  964.27
#Mann=6,-1,0
  4857.2    0.14       0  4956.9    0.04       0  5047.6    0.14       0
  5150.6    0.08       0  5253.6    0.14       0  5356.6    0.08       0
Bank Sta=4956.9,5047.6
XS Rating Curve= 0
Exp/Cntr=0.3,0.1

Type RM Length L Ch R = 1,35515,505,505,505
BEGIN DESCRIPTION:
Fisher River 71.0
END DESCRIPTION:
XS GIS Cut Line= 3
      1503431.25       942225.71      1503479.76       942330.40
      1503630.33       942626.42
#Sta/Elev= 30
  4751.5  941.07  4756.3  940.06  4771.9  935.65  4785.6  931.07  4789.5  929.95
  4806.7  923.87  4815.1  920.08  4832.0  915.53  4839.6  913.03  4864.3  908.96
  4879.6  907.72  4906.2  906.44  4918.4  906.15  4931.0  906.15  4940.6  902.74
  4950.1  900.52  4956.9  894.46  4959.4  889.46  5047.0  889.46  5050.0  894.46
  5051.1  894.46  5053.9  900.26  5062.2  905.23  5092.2  915.05  5098.3  917.34
  5107.2  921.39  5148.6  942.52  5155.5  945.30  5185.7  964.62  5199.0  968.84
#Mann=3,-1,0
  4751.5    0.14       0  4956.9    0.04       0  5050.0    0.14       0
Bank Sta=4956.9,5050
XS Rating Curve= 0
Exp/Cntr=0.3,0.1

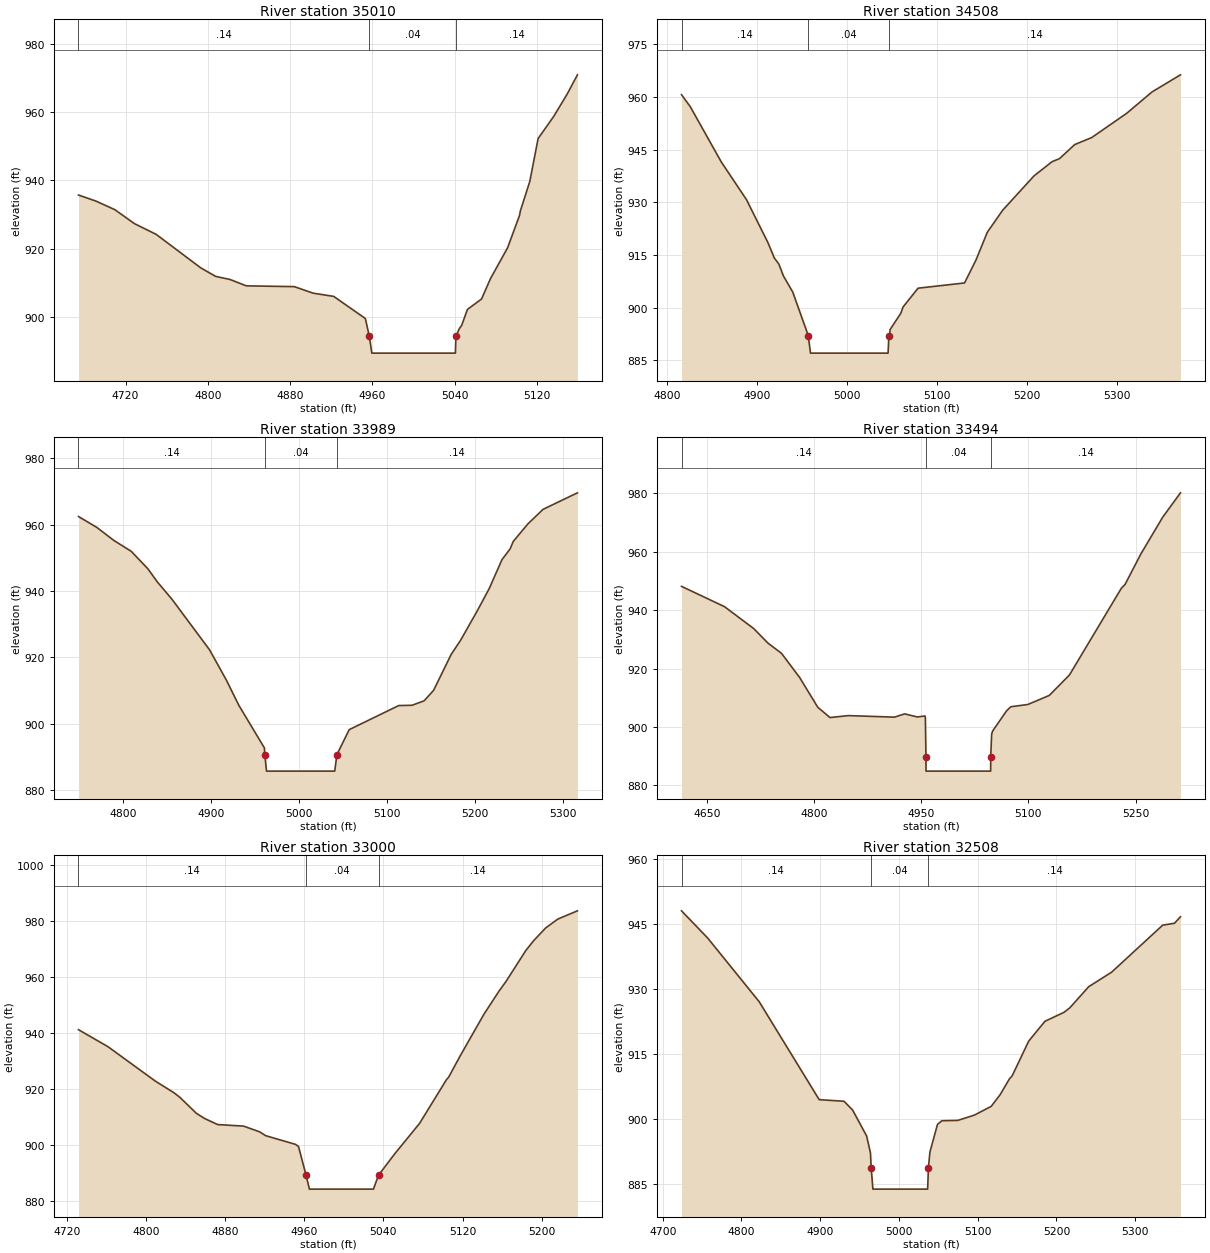
Type RM Length L Ch R = 1,35010,502,502,502
BEGIN DESCRIPTION:
Fisher River 70.0
END DESCRIPTION:
XS GIS Cut Line= 3
      1503298.58       942223.18      1503076.50       942391.65
      1502999.94       942583.05
#Sta/Elev= 30
  4674.3  935.68  4691.5  933.88  4709.6  931.40  4728.8  927.29  4749.8  924.17
  4793.1  914.37  4807.6  911.87  4821.6  910.96  4837.4  909.10  4884.1  908.87
  4902.3  906.96  4922.3  906.02  4953.1  899.54  4956.9  894.41  4959.4  889.41
  5040.6  889.41  5041.1  894.41  5044.4  896.55  5046.7  897.54  5052.3  902.20
  5066.0  905.25  5074.7  911.22  5091.3  920.23  5102.9  929.69  5103.8  931.08
  5112.9  939.66  5121.0  952.22  5136.2  958.71  5149.1  965.16  5159.2  970.86
#Mann=3,-1,0
  4674.3    0.14       0  4956.9    0.04       0  5041.1    0.14       0
Bank Sta=4956.9,5041.1
XS Rating Curve= 0
Exp/Cntr=0.3,0.1

Type RM Length L Ch R = 1,34508,519,519,519
BEGIN DESCRIPTION:
Fisher River 69.0
END DESCRIPTION:
XS GIS Cut Line= 3
      1502563.49       942136.44      1502589.01       942526.92
      1502739.62       942588.19
#Sta/Elev= 30
  4816.2  960.59  4825.9  957.19  4860.3  941.48  4888.3  930.75  4912.1  918.54
  4919.2  914.15  4924.2  912.44  4929.4  909.00  4939.7  904.45  4956.9  892.08
  4959.4  887.08  5045.5  887.08  5046.4  892.08  5047.3  892.08  5047.7  893.77
  5059.5  898.35  5062.2  900.23  5078.8  905.55  5130.4  907.04  5143.2  913.62
  5155.7  921.47  5172.8  927.75  5207.5  937.49  5227.6  941.54  5235.9  942.42
  5252.7  946.40  5271.6  948.40  5310.6  955.33  5338.5  961.37  5370.1  966.24
#Mann=3,-1,0
  4816.2    0.14       0  4956.9    0.04       0  5046.4    0.14       0
Bank Sta=4956.9,5046.4
XS Rating Curve= 0
Exp/Cntr=0.3,0.1

Type RM Length L Ch R = 1,33989,495,495,495
BEGIN DESCRIPTION:
Fisher River 68.0
END DESCRIPTION:
XS GIS Cut Line= 3
      1501975.00       942275.00      1502147.46       942598.39
      1502229.13       942782.15
#Sta/Elev= 30
  4749.1  962.49  4770.0  959.20  4789.3  955.28  4809.1  951.99  4828.1  946.70
  4838.8  942.75  4855.5  937.50  4898.2  922.26  4917.5  913.04  4931.5  905.52
  4960.6  892.65  4961.1  890.65  4963.0  885.65  5040.6  885.65  5043.1  890.65
  5057.1  898.17  5113.4  905.44  5128.5  905.52  5142.3  906.87  5153.1  910.05
  5173.1  920.89  5183.8  925.15  5202.9  934.10  5216.3  940.72  5230.9  949.50
  5240.1  952.71  5243.7  954.98  5260.3  960.25  5277.5  964.64  5316.7  969.64
#Mann=3,-1,0
  4749.1    0.14       0  4961.1    0.04       0  5043.1    0.14       0
Bank Sta=4961.1,5043.1
XS Rating Curve= 0
Exp/Cntr=0.3,0.1

Type RM Length L Ch R = 1,33494,494,494,494
BEGIN DESCRIPTION:
Fisher River 67.0
END DESCRIPTION:
XS GIS Cut Line= 4
      1501759.51       942348.26      1501693.15       942626.46
      1501652.32       942784.70      1501468.57       942953.14
#Sta/Elev= 30
  4614.2  948.18  4674.3  941.24  4715.3  933.73  4735.4  928.71  4754.1  925.27
  4779.6  916.97  4805.0  906.78  4822.1  903.24  4847.8  903.91  4912.4  903.38
  4926.6  904.50  4944.6  903.44  4955.2  903.79  4955.7  903.19  4956.5  889.89
  4956.6  884.89  5047.1  884.89  5047.2  889.89  5048.5  897.56  5050.0  898.67
  5069.5  905.58  5075.4  906.95  5099.1  907.71  5129.2  910.82  5157.4  917.81
  5230.1  947.52  5235.3  948.84  5257.4  959.26  5288.1  971.90  5312.9  980.22
#Mann=3,-1,0
  4614.2    0.14       0  4956.5    0.04       0  5047.2    0.14       0
Bank Sta=4956.5,5047.2
XS Rating Curve= 0
Exp/Cntr=0.3,0.1

Type RM Length L Ch R = 1,33000,492,492,492
BEGIN DESCRIPTION:
Fisher River 66.0
END DESCRIPTION:
XS GIS Cut Line= 3
      1501716.12       942287.01      1501527.25       942299.77
      1501213.28       942325.29
#Sta/Elev= 30
  4731.8  941.23  4761.6  935.16  4809.4  922.89  4828.4  918.70  4834.5  917.01
  4850.8  911.43  4859.1  909.56  4872.5  907.36  4898.6  906.82  4915.1  904.74
  4920.8  903.42  4951.3  900.28  4954.2  899.51  4961.8  889.32  4965.2  884.32
  5029.9  884.32  5035.1  889.32  5051.5  896.95  5076.5  907.77  5103.7  923.37
  5105.9  924.27  5117.7  931.94  5141.5  946.69  5157.0  955.08  5163.7  958.33
  5183.9  969.47  5192.1  973.09  5204.0  977.54  5216.3  980.71  5236.1  983.65
#Mann=3,-1,0
  4731.8    0.14       0  4961.8    0.04       0  5035.1    0.14       0
Bank Sta=4961.8,5035.1
XS Rating Curve= 0
Exp/Cntr=0.3,0.1

Type RM Length L Ch R = 1,32508,515,515,515
BEGIN DESCRIPTION:
Fisher River 65.0
END DESCRIPTION:
XS GIS Cut Line= 4
      1501807.98       941848.01      1501665.08       941850.56
      1501358.80       941789.31      1501272.03       941944.99
#Sta/Elev= 30
  4723.9  948.11  4757.2  941.80  4822.5  927.09  4898.7  904.43  4930.3  904.05
  4941.2  902.01  4958.9  896.03  4963.8  892.12  4964.7  888.73  4966.9  883.73
  5036.4  883.73  5037.4  888.73  5039.3  892.31  5048.9  898.71  5054.5  899.55
  5074.7  899.63  5095.7  900.85  5117.2  902.89  5128.4  905.57  5140.3  909.25
  5143.7  909.93  5164.7  917.97  5185.3  922.55  5209.7  924.65  5217.0  925.69
  5240.9  930.56  5270.0  933.92  5334.8  944.79  5349.8  945.23  5357.4  946.74
#Mann=3,-1,0
  4723.9    0.14       0  4964.7    0.04       0  5037.4    0.14       0
Bank Sta=4964.7,5037.4
XS Rating Curve= 0
Exp/Cntr=0.3,0.1

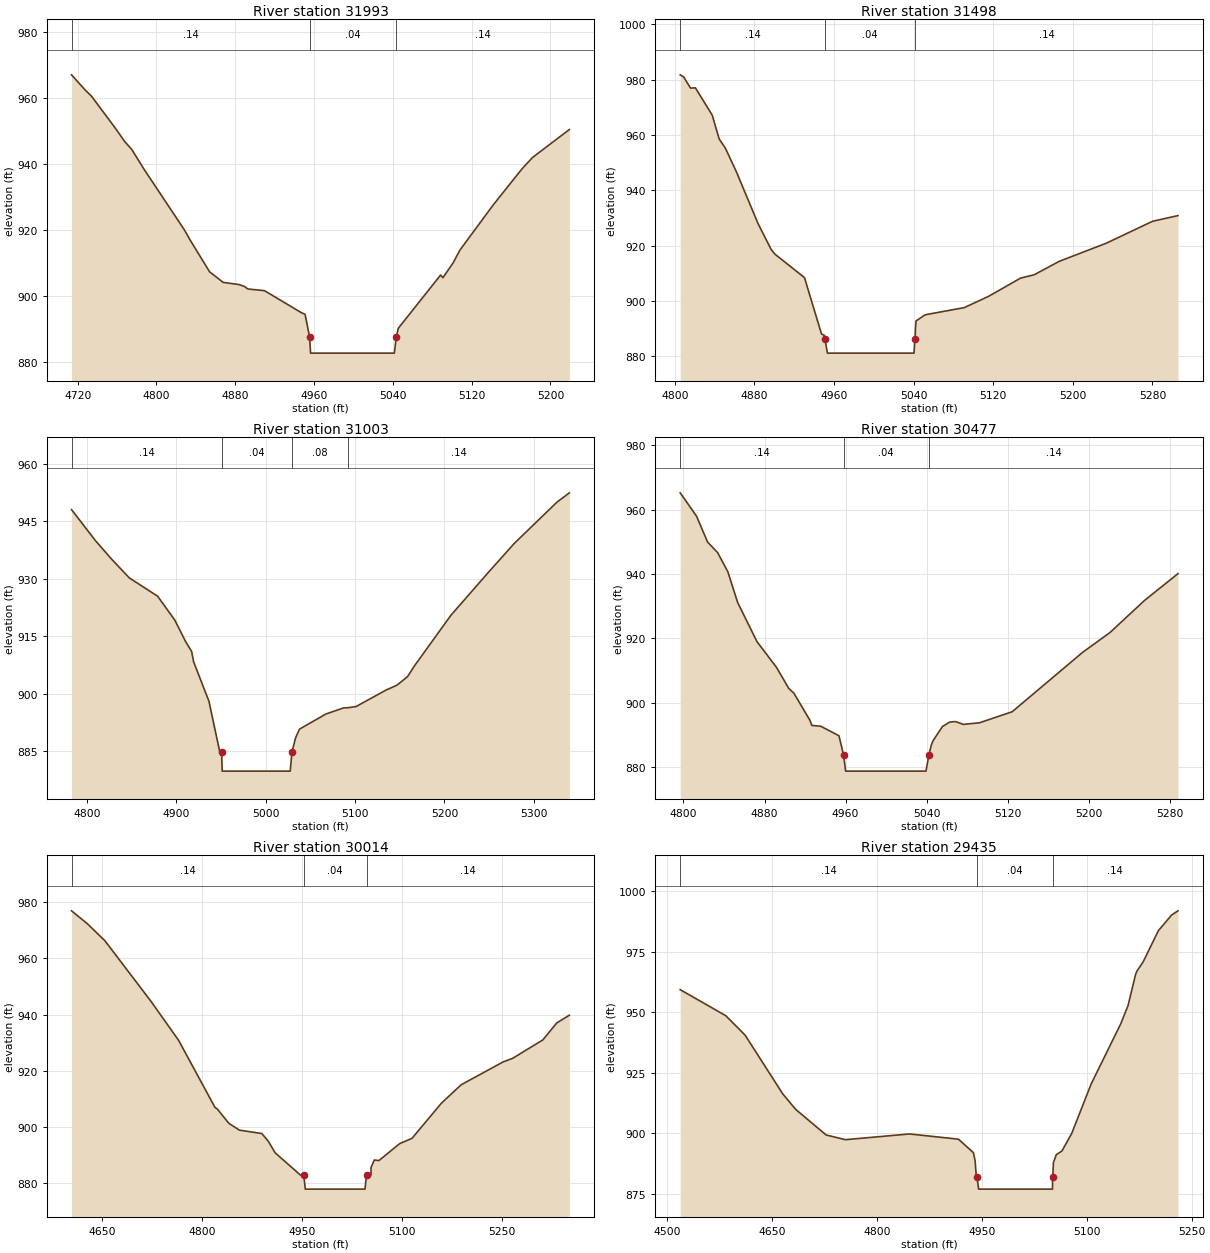
Type RM Length L Ch R = 1,31993,495,495,495
BEGIN DESCRIPTION:
Fisher River 64.0
END DESCRIPTION:
XS GIS Cut Line= 3
      1501966.20       941460.05      1501864.16       941439.64
      1501525.03       941225.02
#Sta/Elev= 30
  4713.8  967.09  4727.2  962.62  4734.1  960.60  4758.1  950.99  4767.8  946.86
  4774.9  944.48  4787.6  938.38  4828.4  920.07  4833.7  917.26  4853.9  907.41
  4867.7  904.18  4883.6  903.54  4889.2  902.97  4892.8  902.18  4909.7  901.67
  4946.6  895.09  4950.9  894.49  4955.4  887.74  4956.5  882.74  5041.5  882.74
  5043.6  887.74  5045.5  890.26  5088.5  906.42  5090.8  905.58  5101.0  910.01
  5108.2  914.01  5141.9  927.66  5170.9  938.51  5181.8  942.03  5219.2  950.51
#Mann=3,-1,0
  4713.8    0.14       0  4955.4    0.04       0  5043.6    0.14       0
Bank Sta=4955.4,5043.6
XS Rating Curve= 0
Exp/Cntr=0.3,0.1

Type RM Length L Ch R = 1,31498,495,495,495
BEGIN DESCRIPTION:
Fisher River 63.0
END DESCRIPTION:
XS GIS Cut Line= 3
      1502017.29       940870.48      1501915.20       940873.03
      1501542.59       941013.40
#Sta/Elev= 30
  4805.4  981.80  4808.9  981.04  4815.8  977.00  4820.7  977.09  4837.6  967.22
  4844.6  958.59  4850.8  955.31  4862.0  946.65  4883.7  927.98  4896.8  918.70
  4900.5  917.02  4930.3  908.51  4947.4  888.15  4950.3  887.62  4950.9  886.21
  4953.4  881.21  5040.4  881.21  5041.2  886.21  5041.5  886.21  5041.8  889.72
  5042.4  892.84  5051.7  895.08  5090.8  897.65  5115.0  901.67  5147.5  908.32
  5161.3  909.55  5186.2  914.37  5233.4  920.90  5280.1  928.86  5305.7  930.92
#Mann=3,-1,0
  4805.4    0.14       0  4950.9    0.04       0  5041.2    0.14       0
Bank Sta=4950.9,5041.2
XS Rating Curve= 0
Exp/Cntr=0.3,0.1

Type RM Length L Ch R = 1,31003,526,526,526
BEGIN DESCRIPTION:
Fisher River 62.0
END DESCRIPTION:
XS GIS Cut Line= 3
      1501762.07       940296.21      1501695.70       940395.75
      1501399.61       940717.37
#Sta/Elev= 30
  4782.9  948.09  4809.3  940.09  4827.7  935.15  4847.5  930.26  4879.2  925.47
  4898.5  919.19  4910.5  913.61  4917.2  911.05  4919.4  908.36  4936.6  898.02
  4948.7  884.78  4950.7  884.78  4951.4  879.78  5027.5  879.78  5029.4  884.78
  5033.5  888.48  5037.9  890.76  5067.4  894.70  5087.1  896.29  5092.3  896.35
  5101.1  896.65  5134.4  900.92  5146.9  902.24  5158.6  904.44  5166.7  907.36
  5207.1  920.46  5249.5  931.80  5277.9  939.22  5325.6  949.99  5339.7  952.48
#Mann=4,-1,0
  4782.9    0.14       0  4950.7    0.04       0  5029.4    0.08       0
  5092.3    0.14       0
Bank Sta=4950.7,5029.4
XS Rating Curve= 0
Exp/Cntr=0.3,0.1

Type RM Length L Ch R = 1,30477,463,463,463
BEGIN DESCRIPTION:
Fisher River 61.0
END DESCRIPTION:
XS GIS Cut Line= 4
      1501375.01       939974.98      1501276.39       940078.33
      1501187.80       940171.15      1500983.59       940252.83
#Sta/Elev= 30
  4796.8  965.24  4812.9  958.00  4823.8  949.96  4833.7  946.67  4843.8  940.72
  4853.5  931.14  4872.5  919.02  4891.8  911.00  4904.1  904.37  4908.9  903.01
  4924.7  894.60  4926.7  892.96  4935.5  892.69  4953.4  889.76  4958.0  883.75
  4960.0  878.75  5039.3  878.75  5042.1  883.75  5044.6  886.91  5046.3  888.21
  5055.5  892.61  5062.6  893.97  5068.3  894.16  5076.1  893.28  5092.0  893.77
  5124.3  897.20  5193.9  915.69  5220.8  921.82  5255.0  931.83  5287.9  940.13
#Mann=3,-1,0
  4796.8    0.14       0  4958.0    0.04       0  5042.1    0.14       0
Bank Sta=4958,5042.1
XS Rating Curve= 0
Exp/Cntr=0.3,0.1

Type RM Length L Ch R = 1,30014,579,579,579
BEGIN DESCRIPTION:
Fisher River 60.0
END DESCRIPTION:
XS GIS Cut Line= 5
      1501366.44       939729.60      1501072.94       939693.87
      1500917.25       939767.89      1500850.89       939875.08
      1500820.27       940025.67
#Sta/Elev= 30
  4603.8  976.88  4627.7  972.26  4654.0  966.23  4723.4  944.63  4764.6  930.87
  4819.2  907.05  4822.6  906.51  4840.1  901.37  4856.0  898.95  4889.6  897.75
  4899.5  894.97  4909.6  890.91  4947.6  882.99  4952.7  882.99  4954.9  877.99
  5044.6  877.99  5046.9  882.99  5053.6  883.02  5053.7  885.70  5058.7  888.35
  5065.5  888.14  5096.9  894.19  5115.2  896.03  5159.3  908.50  5188.9  915.04
  5252.1  923.20  5266.2  924.44  5311.6  930.98  5332.7  937.04  5351.6  939.80
#Mann=3,-1,0
  4603.8    0.14       0  4952.7    0.04       0  5046.9    0.14       0
Bank Sta=4952.7,5046.9
XS Rating Curve= 0
Exp/Cntr=0.3,0.1

Type RM Length L Ch R = 1,29435,506,506,506
BEGIN DESCRIPTION:
Fisher River 59.0
END DESCRIPTION:
XS GIS Cut Line= 3
      1501409.80       939328.88      1500896.83       939150.23
      1500728.43       939140.02
#Sta/Elev= 30
  4518.5  959.35  4583.7  948.57  4611.4  940.51  4665.1  916.26  4683.6  909.84
  4727.2  899.24  4754.8  897.29  4846.4  899.66  4916.5  897.50  4937.8  891.92
  4940.3  888.54  4942.0  881.84  4942.9  881.84  4945.3  876.84  5050.9  876.84
  5051.0  881.84  5051.4  881.87  5052.2  887.78  5056.3  891.05  5064.4  892.60
  5078.4  899.86  5106.2  920.32  5148.6  945.27  5159.0  952.80  5169.8  965.71
  5172.0  967.15  5180.6  970.86  5202.4  983.77  5221.4  990.26  5230.4  991.95
#Mann=3,-1,0
  4518.5    0.14       0  4942.9    0.04       0  5051.0    0.14       0
Bank Sta=4942.9,5051
XS Rating Curve= 0
Exp/Cntr=0.3,0.1