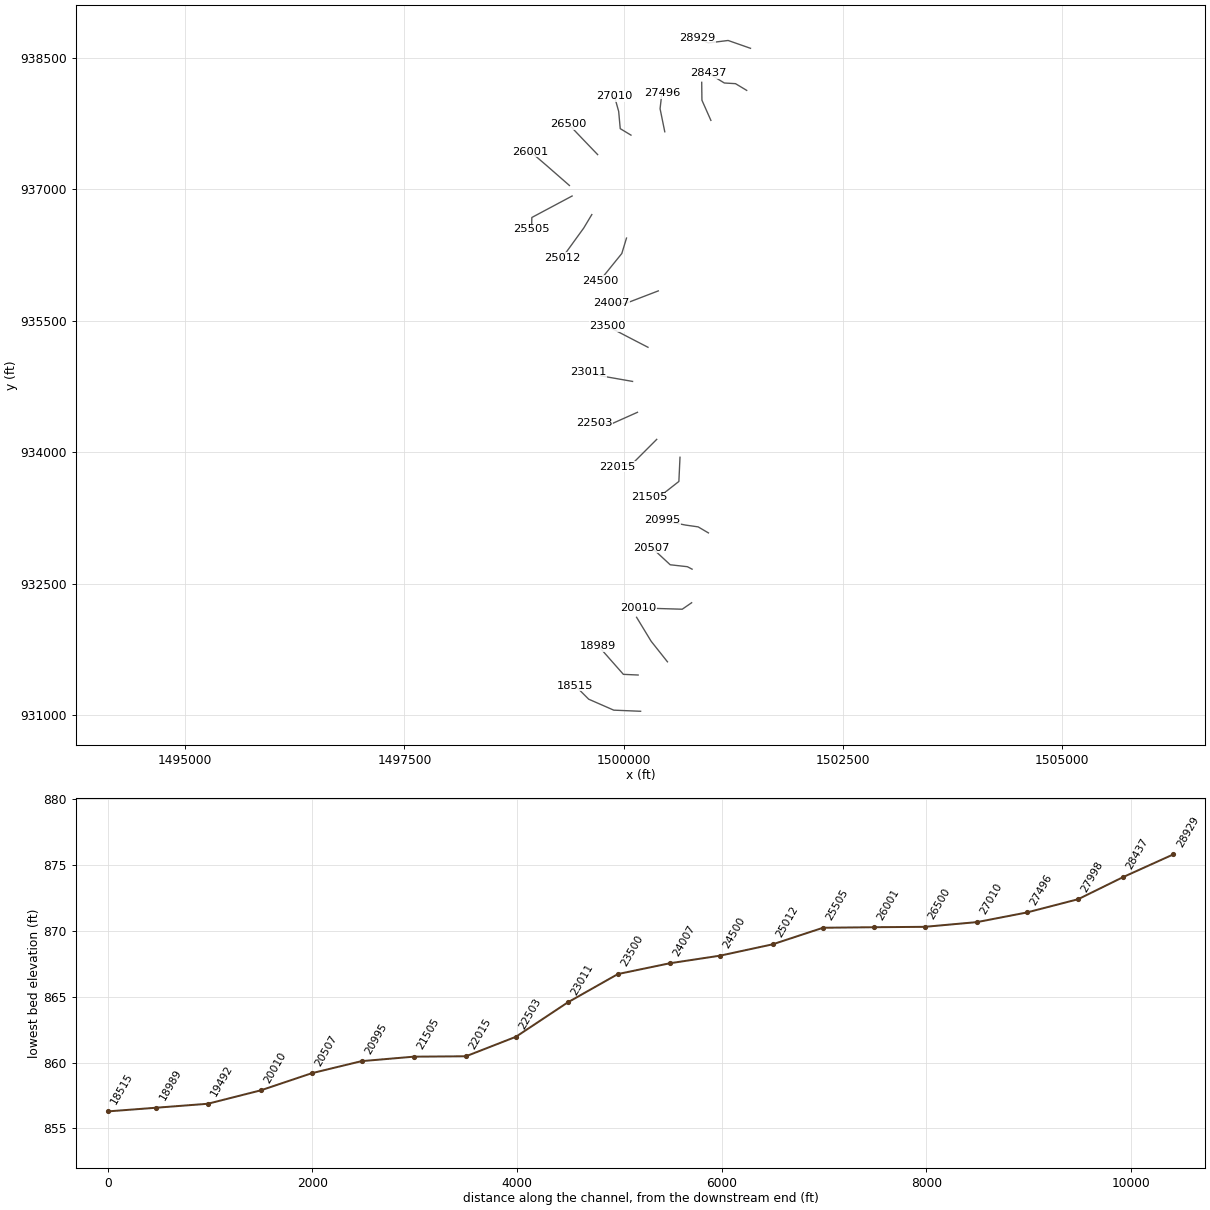
HEC-RAS study Fisher River.prj: Fisher River Limited Detail Study

--- Fisher River.g01 (geometry) --- (continued)

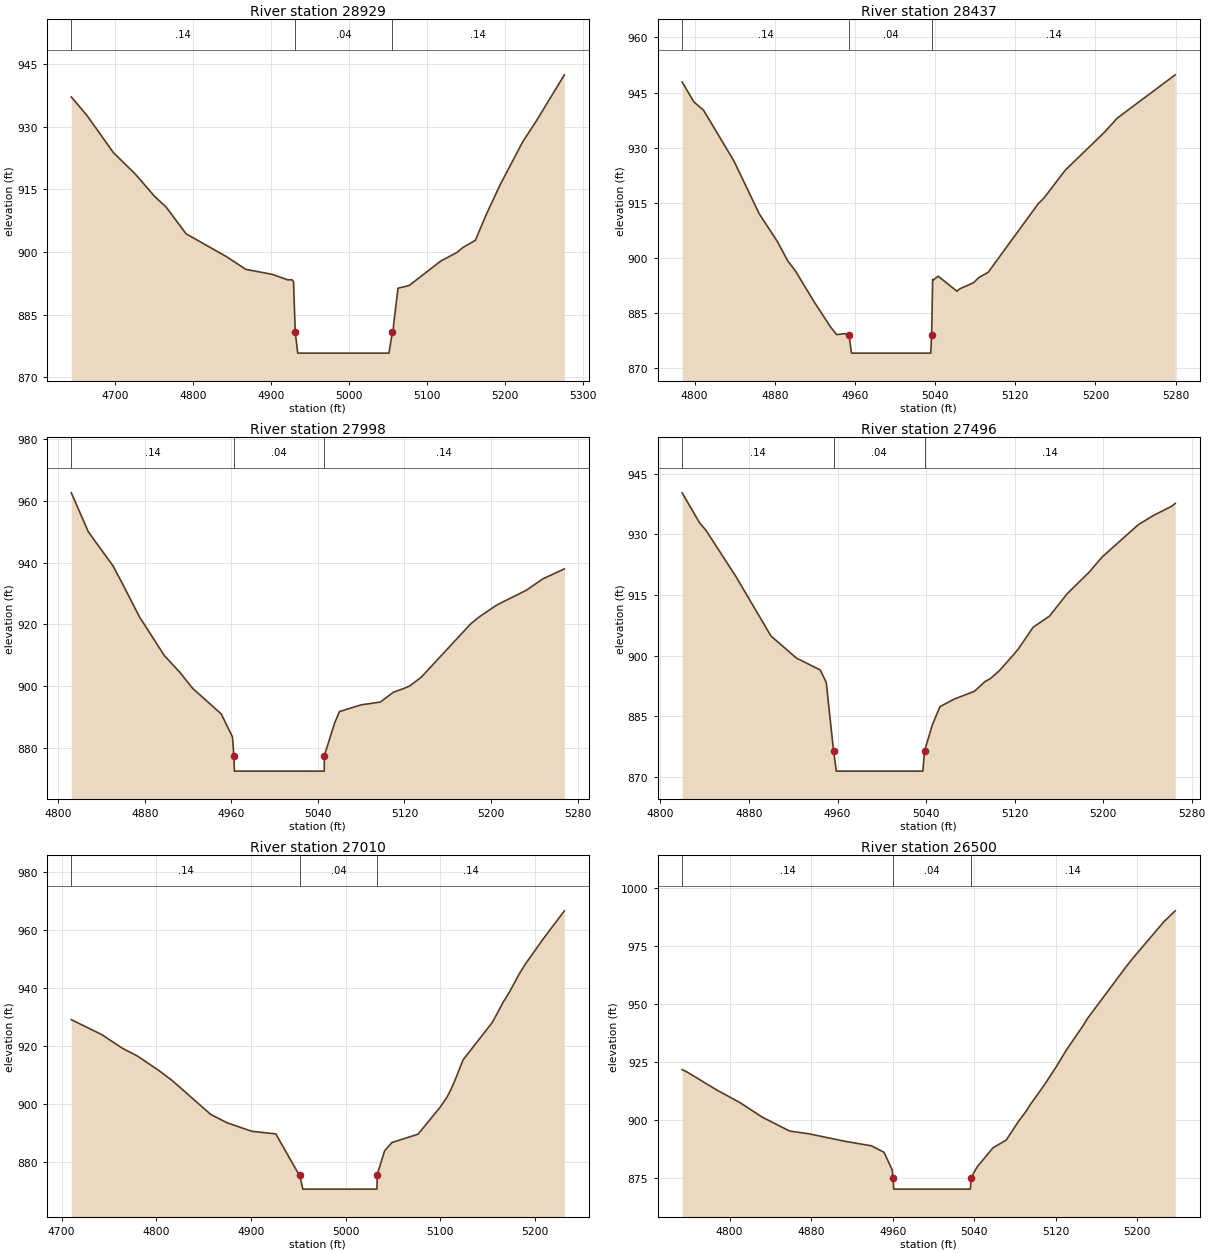
Type RM Length L Ch R = 1,28929,492,492,492
BEGIN DESCRIPTION:
Fisher River 58.0
END DESCRIPTION:
XS GIS Cut Line= 4
      1501445.59       938609.14      1501190.35       938698.47
      1500965.75       938670.40      1500840.72       938723.98
#Sta/Elev= 30
  4643.7  937.12  4663.6  932.73  4697.6  923.83  4725.9  918.65  4750.6  913.33
  4765.4  910.78  4791.0  904.38  4843.5  898.84  4867.7  895.87  4901.2  894.69
  4921.6  893.35  4926.7  893.39  4928.9  892.94  4931.1  880.83  4934.3  875.83
  5051.4  875.83  5055.7  880.83  5056.8  880.84  5057.2  882.43  5063.0  891.35
  5077.3  892.01  5118.0  897.88  5138.8  899.93  5146.2  901.10  5162.3  902.82
  5175.3  908.60  5193.7  915.98  5223.2  926.44  5240.8  931.46  5276.5  942.41
#Mann=3,-1,0
  4643.7    0.14       0  4931.1    0.04       0  5055.7    0.14       0
Bank Sta=4931.1,5055.7
XS Rating Curve= 0
Exp/Cntr=0.3,0.1

Type RM Length L Ch R = 1,28437,439,439,439
BEGIN DESCRIPTION:
Fisher River 57.0
END DESCRIPTION:
XS GIS Cut Line= 4
      1501402.21       938129.29      1501274.58       938205.88
      1501146.96       938213.54      1500963.16       938325.86
#Sta/Elev= 30
  4787.5  947.88  4799.1  942.46  4808.8  940.20  4839.0  926.47  4864.3  912.08
  4882.9  904.29  4892.7  899.28  4901.0  896.27  4919.1  888.11  4935.5  881.26
  4941.7  879.13  4949.6  879.39  4954.0  879.10  4956.5  874.10  5035.6  874.10
  5036.5  879.10  5037.5  894.17  5038.4  894.02  5043.0  895.03  5061.8  890.93
  5064.2  891.54  5078.2  893.24  5083.7  894.68  5092.9  896.08  5142.9  914.75
  5148.6  916.29  5169.8  923.86  5208.4  934.03  5221.8  938.04  5279.6  949.81
#Mann=3,-1,0
  4787.5    0.14       0  4954.0    0.04       0  5036.5    0.14       0
Bank Sta=4954,5036.5
XS Rating Curve= 0
Exp/Cntr=0.3,0.1

Type RM Length L Ch R = 1,27998,502,502,502
BEGIN DESCRIPTION:
Fisher River 56.0
END DESCRIPTION:
XS GIS Cut Line= 3
      1500993.83       937787.28      1500891.73       938017.01
      1500889.18       938221.20
#Sta/Elev= 30
  4812.2  962.65  4827.8  950.11  4832.2  947.92  4850.4  939.14  4859.5  933.16
  4875.1  922.47  4898.2  909.87  4912.6  904.41  4924.3  899.26  4950.7  890.98
  4961.1  883.51  4962.4  877.42  4962.9  872.42  5045.9  872.42  5046.0  877.42
  5055.5  888.03  5060.0  891.73  5079.9  893.90  5097.8  894.82  5109.9  898.03
  5118.5  899.08  5124.8  900.01  5135.4  902.82  5181.2  920.15  5189.2  922.44
  5204.3  926.03  5208.1  926.77  5232.5  931.03  5248.2  934.82  5267.8  937.97
#Mann=3,-1,0
  4812.2    0.14       0  4962.4    0.04       0  5046.0    0.14       0
Bank Sta=4962.4,5046
XS Rating Curve= 0
Exp/Cntr=0.3,0.1

Type RM Length L Ch R = 1,27496,486,486,486
BEGIN DESCRIPTION:
Fisher River 55.0
END DESCRIPTION:
XS GIS Cut Line= 3
      1500468.04       937657.18      1500414.45       937920.02
      1500434.86       938096.09
#Sta/Elev= 30
  4819.6  940.24  4835.1  932.93  4841.4  930.86  4868.1  919.57  4899.8  904.85
  4922.8  899.38  4944.4  896.42  4949.8  893.33  4956.4  876.41  4958.9  871.41
  5037.1  871.41  5038.6  876.41  5045.7  882.88  5052.5  887.36  5065.5  889.23
  5083.8  891.17  5093.0  893.52  5098.0  894.27  5106.2  896.24  5119.1  900.23
  5123.6  901.72  5136.7  906.99  5151.6  909.78  5167.2  915.20  5187.4  920.64
  5199.0  924.34  5231.6  932.33  5245.8  934.70  5261.7  936.89  5265.1  937.62
#Mann=3,-1,0
  4819.6    0.14       0  4956.4    0.04       0  5038.6    0.14       0
Bank Sta=4956.4,5038.6
XS Rating Curve= 0
Exp/Cntr=0.3,0.1

Type RM Length L Ch R = 1,27010,510,510,510
BEGIN DESCRIPTION:
Fisher River 54.0
END DESCRIPTION:
XS GIS Cut Line= 4
      1500082.61       937618.87      1499960.14       937692.87
      1499942.27       937889.39      1499893.79       938062.92
#Sta/Elev= 30
  4710.3  929.06  4742.6  923.90  4764.4  919.18  4780.2  916.53  4802.5  911.60
  4816.3  908.24  4857.6  896.39  4875.0  893.51  4900.9  890.61  4926.2  889.71
  4949.1  876.57  4951.3  875.68  4954.8  870.68  5033.0  870.68  5033.3  875.68
  5041.1  883.91  5048.8  886.73  5076.4  889.60  5099.3  898.73  5106.9  902.32
  5110.5  904.59  5115.4  908.17  5124.0  915.25  5155.1  928.24  5166.2  935.04
  5172.9  938.56  5183.5  944.99  5190.6  948.65  5208.2  956.74  5230.9  966.57
#Mann=3,-1,0
  4710.3    0.14       0  4951.3    0.04       0  5033.3    0.14       0
Bank Sta=4951.3,5033.3
XS Rating Curve= 0
Exp/Cntr=0.3,0.1

Type RM Length L Ch R = 1,26500,499,499,499
BEGIN DESCRIPTION:
Fisher River 53.0
END DESCRIPTION:
XS GIS Cut Line= 3
      1499702.34       937396.82      1499531.66       937574.81
      1499367.98       937746.49
#Sta/Elev= 30
  4753.4  921.74  4757.9  920.80  4787.7  912.89  4810.1  907.57  4832.1  901.26
  4859.0  895.29  4877.2  894.18  4913.4  890.88  4939.0  888.98  4951.5  886.16
  4959.6  878.51  4960.2  875.32  4961.0  870.32  5036.2  870.32  5037.0  875.32
  5042.8  879.83  5058.3  888.06  5071.4  891.44  5082.9  899.15  5091.6  904.26
  5094.6  906.43  5109.0  915.30  5120.4  922.93  5130.2  930.04  5147.0  940.80
  5151.1  943.74  5188.6  965.79  5195.5  969.61  5226.0  985.35  5237.2  990.08
#Mann=3,-1,0
  4753.4    0.14       0  4960.2    0.04       0  5037.0    0.14       0
Bank Sta=4960.2,5037
XS Rating Curve= 0
Exp/Cntr=0.3,0.1

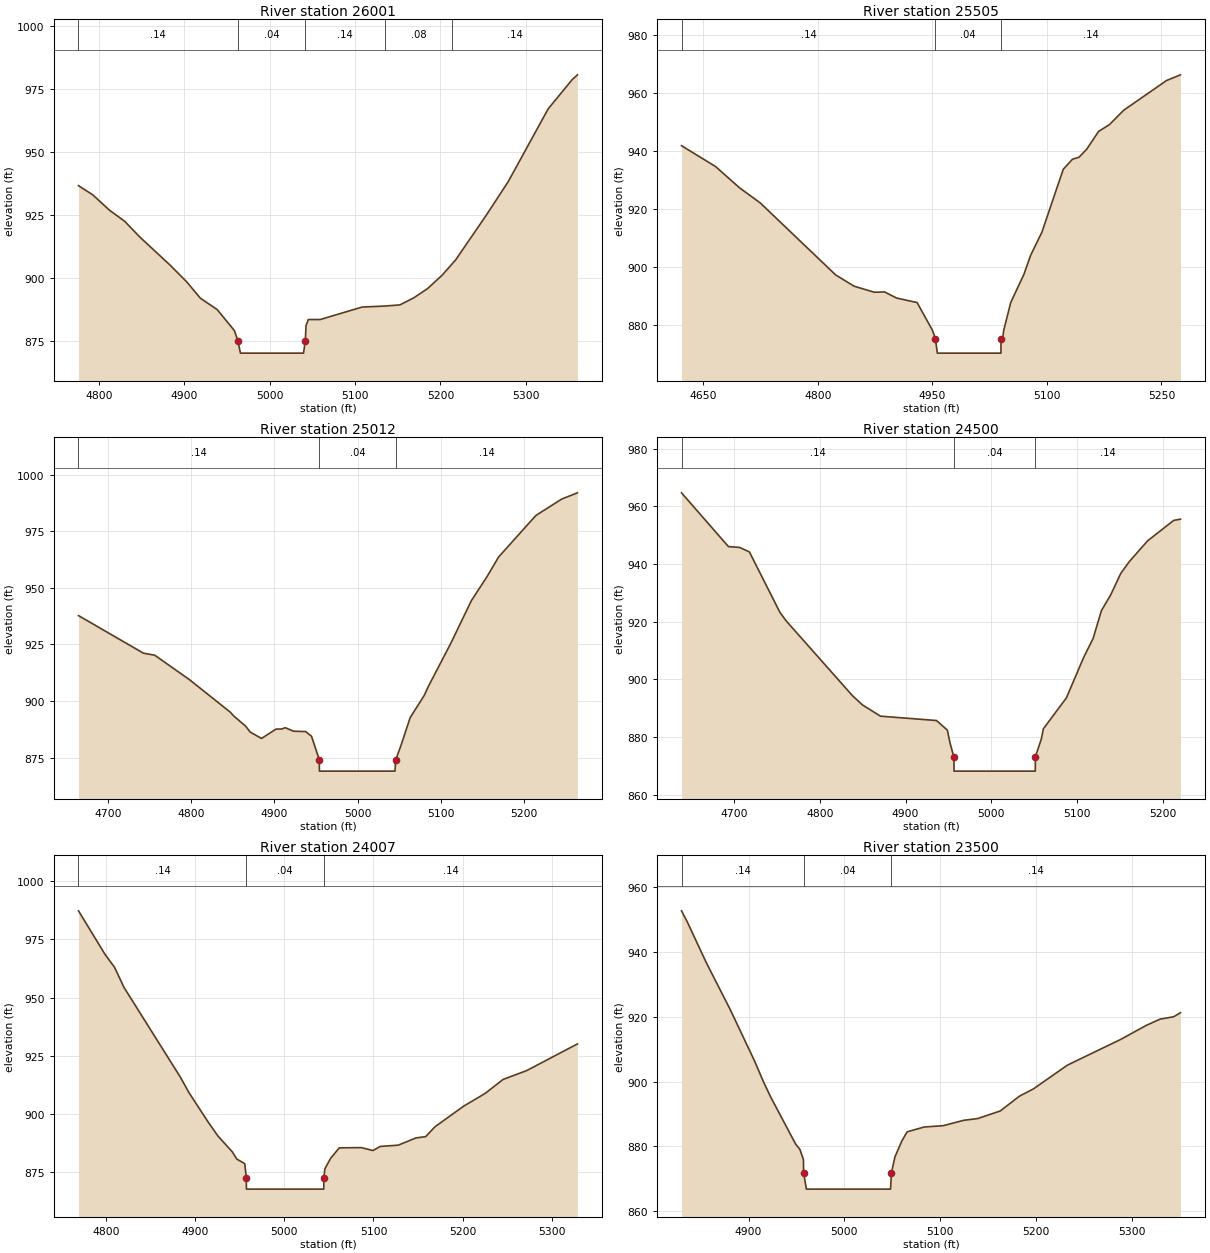
Type RM Length L Ch R = 1,26001,496,496,496
BEGIN DESCRIPTION:
Fisher River 52.0
END DESCRIPTION:
XS GIS Cut Line= 3
      1499380.74       937044.60      1499117.88       937274.29
      1498939.21       937427.44
#Sta/Elev= 30
  4776.1  936.70  4792.6  933.12  4812.5  926.95  4830.2  922.58  4848.0  916.31
  4884.0  904.99  4902.7  898.62  4918.8  892.09  4938.6  887.55  4958.7  879.23
  4962.7  875.29  4965.8  870.29  5039.7  870.29  5041.8  875.29  5042.6  881.20
  5045.3  883.60  5059.3  883.62  5108.3  888.56  5135.3  888.96  5152.6  889.42
  5168.9  892.23  5185.0  895.89  5201.9  901.15  5213.2  905.48  5217.7  907.19
  5253.6  924.92  5279.4  938.27  5326.2  967.14  5354.3  978.73  5360.5  980.65
#Mann=5,-1,0
  4776.1    0.14       0  4962.7    0.04       0  5041.8    0.14       0
  5135.3    0.08       0  5213.2    0.14       0
Bank Sta=4962.7,5041.8
XS Rating Curve= 0
Exp/Cntr=0.3,0.1

Type RM Length L Ch R = 1,25505,493,493,493
BEGIN DESCRIPTION:
Fisher River 51.0
END DESCRIPTION:
XS GIS Cut Line= 3
      1499411.36       936924.60      1498951.98       936679.60
      1498949.43       936546.85
#Sta/Elev= 30
  4621.5  941.86  4666.1  934.66  4697.7  927.27  4724.6  922.10  4823.3  897.26
  4847.5  893.35  4874.0  891.27  4887.4  891.38  4903.1  889.27  4930.0  887.71
  4949.8  878.29  4954.0  875.25  4956.5  870.25  5039.8  870.25  5039.9  875.25
  5042.0  875.25  5043.4  878.07  5052.6  887.70  5070.0  897.52  5078.6  903.98
  5093.5  912.03  5121.4  933.71  5133.5  937.19  5142.1  937.89  5152.0  940.59
  5167.7  946.79  5181.8  949.12  5200.5  954.09  5256.7  964.36  5274.9  966.32
#Mann=3,-1,0
  4621.5    0.14       0  4954.0    0.04       0  5039.9    0.14       0
Bank Sta=4954,5039.9
XS Rating Curve= 0
Exp/Cntr=0.3,0.1

Type RM Length L Ch R = 1,25012,512,512,512
BEGIN DESCRIPTION:
Fisher River 50.0
END DESCRIPTION:
XS GIS Cut Line= 3
      1499635.98       936712.76      1499544.12       936559.64
      1499296.53       936217.61
#Sta/Elev= 30
  4664.0  937.75  4742.2  921.13  4755.8  920.24  4797.3  909.52  4847.0  894.99
  4850.8  893.40  4865.1  888.93  4870.8  886.25  4884.4  883.44  4902.0  887.59
  4908.5  887.59  4912.9  888.20  4922.9  886.64  4937.5  886.48  4944.6  884.41
  4954.0  873.99  4954.1  868.99  5045.1  868.99  5046.0  873.99  5052.3  880.31
  5063.4  892.65  5080.3  902.44  5085.2  906.36  5112.4  925.55  5137.1  944.37
  5155.5  954.72  5169.9  963.66  5214.7  981.99  5245.9  989.27  5264.8  992.02
#Mann=3,-1,0
  4664.0    0.14       0  4954.0    0.04       0  5046.0    0.14       0
Bank Sta=4954,5046
XS Rating Curve= 0
Exp/Cntr=0.3,0.1

Type RM Length L Ch R = 1,24500,493,493,493
BEGIN DESCRIPTION:
Fisher River 49.0
END DESCRIPTION:
XS GIS Cut Line= 3
      1500031.60       936444.78      1499978.01       936268.68
      1499727.87       935959.84
#Sta/Elev= 30
  4638.9  964.70  4693.6  946.04  4706.7  945.75  4718.0  944.20  4753.6  923.22
  4760.7  920.33  4837.9  894.38  4849.8  891.10  4870.8  887.20  4936.1  885.69
  4948.7  882.36  4951.9  877.85  4955.5  873.89  4955.6  873.13  4956.4  873.13
  4956.5  868.13  5051.2  868.13  5051.3  873.13  5058.2  879.21  5060.6  882.81
  5087.4  893.52  5107.6  907.60  5118.6  914.18  5128.3  923.84  5139.1  929.29
  5150.8  936.73  5160.6  940.77  5182.1  948.04  5212.5  955.13  5220.4  955.57
#Mann=3,-1,0
  4638.9    0.14       0  4956.4    0.04       0  5051.3    0.14       0
Bank Sta=4956.4,5051.3
XS Rating Curve= 0
Exp/Cntr=0.3,0.1

Type RM Length L Ch R = 1,24007,507,507,507
BEGIN DESCRIPTION:
Fisher River 48.0
END DESCRIPTION:
XS GIS Cut Line= 3
      1500394.05       935842.46      1500008.63       935694.42
      1499863.11       935709.73
#Sta/Elev= 30
  4769.4  987.34  4799.4  968.45  4809.8  963.04  4820.4  954.38  4883.6  915.74
  4893.4  908.98  4914.4  896.62  4925.6  890.46  4941.9  883.55  4946.7  880.52
  4955.8  878.49  4957.5  872.26  4957.6  867.55  5044.3  867.55  5044.4  872.55
  5045.6  876.33  5052.0  880.82  5061.7  885.32  5086.2  885.42  5099.5  884.17
  5107.5  885.92  5127.7  886.47  5147.7  889.59  5158.5  890.15  5168.9  894.38
  5201.0  903.24  5225.1  908.73  5245.3  914.77  5271.7  918.57  5328.6  930.05
#Mann=3,-1,0
  4769.4    0.14       0  4957.5    0.04       0  5044.4    0.14       0
Bank Sta=4957.5,5044.4
XS Rating Curve= 0
Exp/Cntr=0.3,0.1

Type RM Length L Ch R = 1,23500,489,489,489
BEGIN DESCRIPTION:
Fisher River 47.0
END DESCRIPTION:
XS GIS Cut Line= 3
      1500276.64       935199.26      1500125.63       935277.12
      1499814.64       935439.20
#Sta/Elev= 30
  4830.1  952.76  4836.1  949.35  4856.1  936.65  4880.6  922.43  4906.1  906.48
  4915.7  899.85  4923.0  895.29  4949.2  880.64  4953.6  879.03  4957.3  875.86
  4957.5  871.73  4960.4  866.73  5048.2  866.73  5049.1  871.73  5052.8  876.72
  5060.1  881.68  5065.5  884.44  5083.4  885.94  5103.1  886.34  5124.6  888.01
  5139.0  888.53  5162.7  890.90  5182.6  895.45  5197.5  897.76  5232.8  905.07
  5288.2  912.99  5315.3  917.39  5329.5  919.29  5343.5  920.00  5350.7  921.26
#Mann=3,-1,0
  4830.1    0.14       0  4957.5    0.04       0  5049.1    0.14       0
Bank Sta=4957.5,5049.1
XS Rating Curve= 0
Exp/Cntr=0.3,0.1

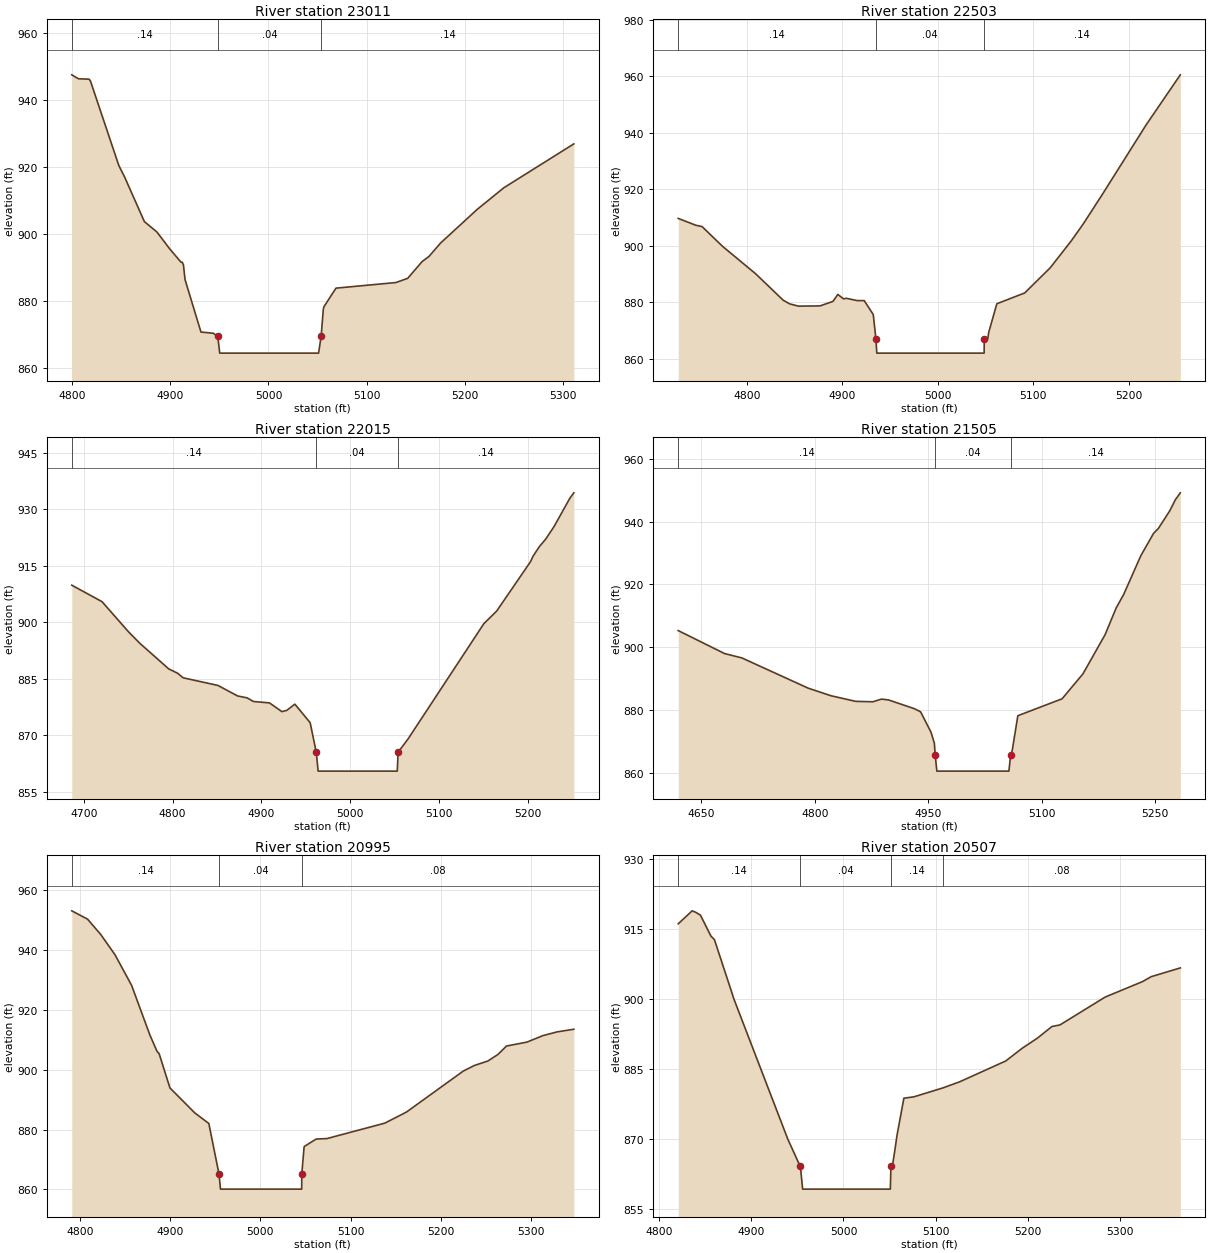
Type RM Length L Ch R = 1,23011,508,508,508
BEGIN DESCRIPTION:
Fisher River 46.0
END DESCRIPTION:
XS GIS Cut Line= 3
      1500100.47       934810.05      1499750.85       934871.30
      1499600.24       934912.14
#Sta/Elev= 30
  4799.8  947.66  4806.6  946.48  4817.4  946.36  4818.8  945.83  4847.7  920.58
  4853.5  917.21  4873.7  903.85  4886.5  900.73  4899.6  895.67  4911.1  891.69
  4912.3  891.73  4913.5  890.85  4915.1  886.51  4931.3  870.87  4943.8  870.52
  4948.4  869.58  4950.4  864.58  5051.0  864.58  5053.6  869.58  5055.8  877.66
  5056.5  878.44  5068.7  883.98  5129.7  885.65  5141.7  886.91  5156.5  891.95
  5163.4  893.46  5175.2  897.46  5212.4  907.48  5239.6  913.95  5310.8  927.05
#Mann=3,-1,0
  4799.8    0.14       0  4948.4    0.04       0  5053.6    0.14       0
Bank Sta=4948.4,5053.6
XS Rating Curve= 0
Exp/Cntr=0.3,0.1

Type RM Length L Ch R = 1,22503,488,488,488
BEGIN DESCRIPTION:
Fisher River 45.0
END DESCRIPTION:
XS GIS Cut Line= 3
      1500156.71       934457.84      1499847.84       934320.00
      1499661.49       934340.42
#Sta/Elev= 30
  4728.3  909.66  4746.7  907.24  4753.3  906.75  4774.6  899.80  4809.3  890.07
  4838.3  880.67  4845.0  879.40  4854.1  878.60  4876.8  878.68  4890.3  880.27
  4895.4  882.74  4901.4  881.16  4904.3  881.38  4915.7  880.55  4923.0  880.56
  4932.5  875.63  4935.3  866.96  4936.2  861.96  5048.6  861.96  5048.7  866.96
  5052.4  866.96  5053.3  869.20  5061.9  879.44  5091.1  883.27  5117.8  892.18
  5139.8  901.69  5152.4  907.71  5172.6  918.27  5218.2  942.76  5254.0  960.49
#Mann=3,-1,0
  4728.3    0.14       0  4935.3    0.04       0  5048.7    0.14       0
Bank Sta=4935.3,5048.7
XS Rating Curve= 0
Exp/Cntr=0.3,0.1

Type RM Length L Ch R = 1,22015,510,510,510
BEGIN DESCRIPTION:
Fisher River 44.0
END DESCRIPTION:
XS GIS Cut Line= 3
      1500376.13       934148.96      1500108.17       933881.01
      1499926.94       933837.61
#Sta/Elev= 30
  4686.4  909.83  4720.5  905.45  4750.5  897.40  4763.2  894.37  4795.6  887.61
  4805.6  886.46  4811.8  885.25  4851.0  883.22  4873.1  880.43  4883.9  879.92
  4890.9  878.96  4909.0  878.59  4923.0  876.27  4928.5  876.61  4937.6  878.25
  4954.8  873.35  4961.7  865.48  4963.8  860.48  5052.9  860.48  5053.8  865.48
  5065.3  869.11  5150.4  899.62  5164.8  902.96  5202.9  916.06  5205.7  917.49
  5212.7  920.01  5220.1  922.09  5229.4  925.38  5247.3  932.95  5251.7  934.34
#Mann=3,-1,0
  4686.4    0.14       0  4961.7    0.04       0  5053.8    0.14       0
Bank Sta=4961.7,5053.8
XS Rating Curve= 0
Exp/Cntr=0.3,0.1

Type RM Length L Ch R = 1,21505,510,510,510
BEGIN DESCRIPTION:
Fisher River 43.0
END DESCRIPTION:
XS GIS Cut Line= 4
      1500641.61       933944.82      1500628.84       933669.17
      1500450.18       933528.79      1500294.49       933490.50
#Sta/Elev= 30
  4619.5  905.27  4680.8  897.93  4703.6  896.55  4791.3  886.90  4821.4  884.49
  4854.0  882.70  4876.8  882.57  4888.0  883.41  4897.2  883.17  4931.6  880.36
  4939.8  879.36  4953.5  872.89  4958.0  869.34  4959.1  865.45  4961.3  860.45
  5056.5  860.45  5058.7  865.45  5059.8  865.45  5068.3  878.12  5126.8  883.52
  5154.4  891.49  5183.7  904.01  5198.2  912.47  5208.1  916.76  5230.9  929.18
  5247.7  936.30  5253.9  937.80  5269.0  943.44  5276.4  946.97  5283.0  949.20
#Mann=3,-1,0
  4619.5    0.14       0  4959.1    0.04       0  5058.7    0.14       0
Bank Sta=4959.1,5058.7
XS Rating Curve= 0
Exp/Cntr=0.3,0.1

Type RM Length L Ch R = 1,20995,488,488,488
BEGIN DESCRIPTION:
Fisher River 42.0
END DESCRIPTION:
XS GIS Cut Line= 4
      1500965.77       933082.12      1500848.34       933151.05
      1500705.41       933171.47      1500434.82       933225.07
#Sta/Elev= 30
  4791.0  953.17  4808.5  950.39  4823.1  945.26  4839.0  938.44  4857.3  928.26
  4877.5  911.70  4885.5  906.17  4887.8  905.43  4899.8  893.95  4927.2  885.64
  4942.9  882.06  4954.2  865.11  4955.8  860.11  5045.8  860.11  5045.9  865.11
  5048.4  873.99  5048.7  874.37  5061.8  876.85  5073.7  877.01  5137.9  882.17
  5161.9  885.88  5224.9  899.59  5237.2  901.46  5252.1  902.95  5263.1  905.10
  5272.8  907.96  5295.5  909.28  5313.0  911.43  5328.7  912.68  5347.4  913.57
#Mann=3,-1,0
  4791.0    0.14       0  4954.2    0.04       0  5045.9    0.08       0
Bank Sta=4954.2,5045.9
XS Rating Curve= 0
Exp/Cntr=0.3,0.1

Type RM Length L Ch R = 1,20507,497,497,497
BEGIN DESCRIPTION:
Fisher River 41.0
END DESCRIPTION:
XS GIS Cut Line= 4
      1500779.41       932668.67      1500725.83       932696.74
      1500530.06       932718.80      1500320.03       932913.67
#Sta/Elev= 30
  4821.0  916.12  4836.1  918.90  4839.8  918.60  4845.1  917.97  4856.5  913.46
  4860.2  912.73  4880.2  900.69  4880.4  900.45  4939.7  869.93  4951.6  864.75
  4953.3  864.19  4955.8  859.19  5050.8  859.19  5051.5  864.19  5053.1  864.24
  5055.8  867.62  5058.0  870.68  5065.5  878.70  5076.3  878.99  5107.7  880.90
  5126.1  882.23  5175.9  886.69  5193.8  889.43  5210.2  891.59  5225.9  894.08
  5234.6  894.42  5283.5  900.39  5324.1  903.72  5333.4  904.77  5365.0  906.65
#Mann=4,-1,0
  4821.0    0.14       0  4953.3    0.04       0  5051.5    0.14       0
  5107.7    0.08       0
Bank Sta=4953.3,5051.5
XS Rating Curve= 0
Exp/Cntr=0.3,0.1

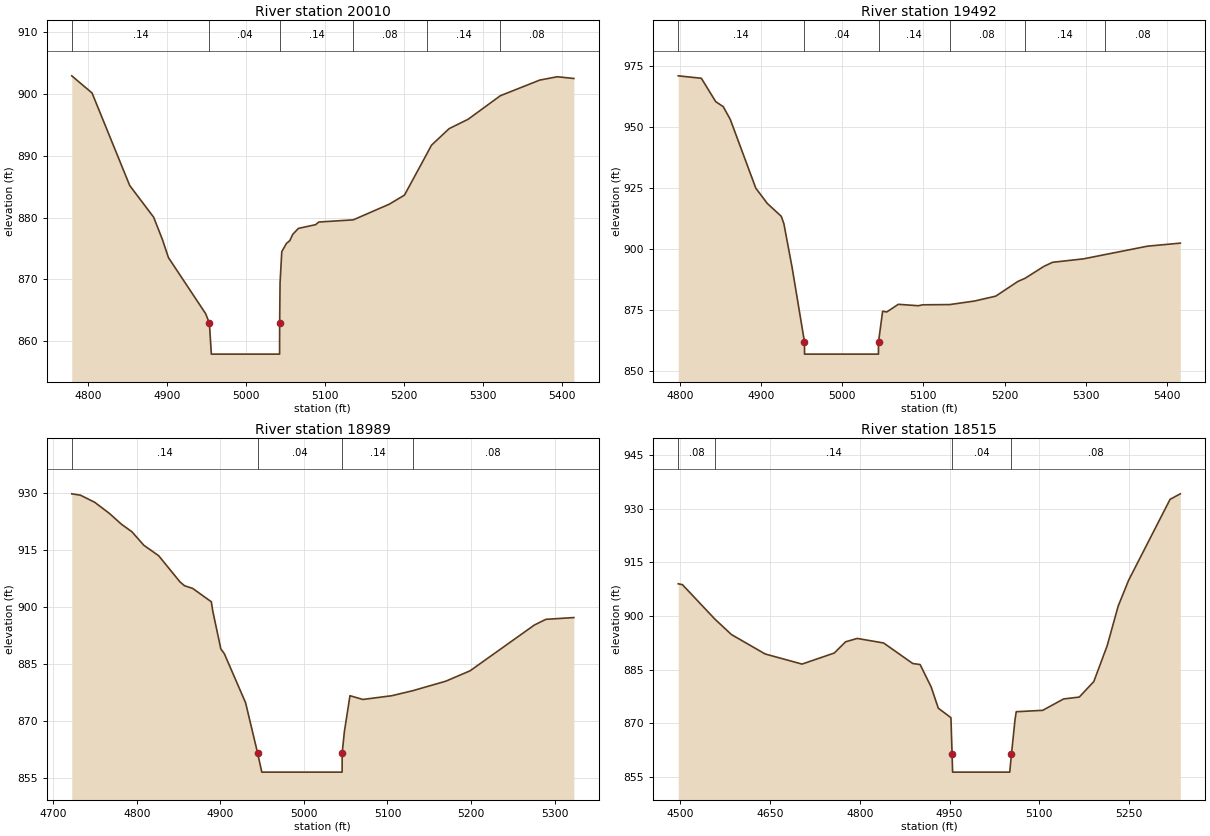
Type RM Length L Ch R = 1,20010,518,518,518
BEGIN DESCRIPTION:
Fisher River 40.0
END DESCRIPTION:
XS GIS Cut Line= 3
      1500774.33       932285.82      1500667.13       932211.80
      1500161.74       932227.12
#Sta/Elev= 30
  4779.0  902.93  4804.7  900.15  4852.4  885.18  4882.7  880.05  4894.0  876.38
  4901.4  873.52  4948.6  864.43  4953.3  862.89  4955.8  857.89  5042.2  857.89
  5042.3  862.89  5042.8  869.42  5045.0  874.48  5051.0  875.82  5055.1  876.25
  5059.0  877.30  5066.1  878.24  5087.8  878.84  5091.9  879.27  5135.5  879.62
  5181.2  882.16  5200.4  883.63  5228.6  890.27  5234.5  891.69  5256.9  894.38
  5281.0  895.90  5321.8  899.71  5371.7  902.24  5393.9  902.78  5414.9  902.50
#Mann=6,-1,0
  4779.0    0.14       0  4953.3    0.04       0  5042.3    0.14       0
  5135.5    0.08       0  5228.6    0.14       0  5321.8    0.08       0
Bank Sta=4953.3,5042.3
XS Rating Curve= 0
Exp/Cntr=0.3,0.1

Type RM Length L Ch R = 1,19492,503,503,503
BEGIN DESCRIPTION:
Fisher River 39.0
END DESCRIPTION:
XS GIS Cut Line= 3
      1500498.65       931612.04      1500312.36       931846.82
      1500146.48       932119.88
#Sta/Elev= 30
  4797.6  971.12  4826.1  970.12  4843.8  960.53  4853.1  958.47  4861.8  953.22
  4893.3  924.98  4907.5  918.71  4924.7  913.44  4927.9  910.41  4938.1  892.34
  4953.3  861.87  4953.4  856.87  5044.5  856.87  5044.6  861.87  5049.7  874.48
  5054.8  874.18  5069.0  877.32  5093.7  876.74  5099.2  877.12  5132.3  877.21
  5162.9  878.66  5189.2  880.68  5216.6  886.73  5225.2  887.98  5248.8  892.94
  5259.3  894.57  5297.4  895.98  5324.3  897.76  5376.4  901.19  5416.8  902.44
#Mann=6,-1,0
  4797.6    0.14       0  4953.3    0.04       0  5044.6    0.14       0
  5132.3    0.08       0  5225.2    0.14       0  5324.3    0.08       0
Bank Sta=4953.3,5044.6
XS Rating Curve= 0
Exp/Cntr=0.3,0.1

Type RM Length L Ch R = 1,18989,474,474,474
BEGIN DESCRIPTION:
Fisher River 38.0
END DESCRIPTION:
XS GIS Cut Line= 3
      1500164.36       931461.42      1499995.87       931469.08
      1499710.05       931793.19
#Sta/Elev= 30
  4722.2  929.83  4732.6  929.47  4749.6  927.61  4767.1  924.70  4781.6  921.84
  4794.2  919.84  4808.5  916.28  4826.2  913.54  4851.7  906.65  4857.1  905.64
  4866.9  904.93  4889.2  901.41  4890.9  899.00  4900.6  889.00  4904.8  887.73
  4930.2  874.84  4944.6  861.57  4949.6  856.57  5045.7  856.57  5045.8  861.57
  5048.4  867.21  5055.1  876.69  5070.5  875.70  5105.0  876.68  5130.0  877.99
  5169.8  880.51  5198.8  883.24  5275.8  895.30  5289.5  896.79  5323.0  897.26
#Mann=4,-1,0
  4722.2    0.14       0  4944.6    0.04       0  5045.8    0.14       0
  5130.0    0.08       0
Bank Sta=4944.6,5045.8
XS Rating Curve= 0
Exp/Cntr=0.3,0.1

Type RM Length L Ch R = 1,18515,303,303,303
BEGIN DESCRIPTION:
Fisher River 37.0
END DESCRIPTION:
XS GIS Cut Line= 4
      1500192.43       931047.95      1499886.12       931060.71
      1499600.27       931185.78      1499444.56       931341.49
#Sta/Elev= 30
  4496.7  909.04  4503.8  908.78  4558.1  899.11  4585.6  894.82  4641.9  889.38
  4703.5  886.55  4757.3  889.64  4776.3  892.79  4795.8  893.73  4839.8  892.46
  4888.5  886.71  4900.8  886.42  4919.3  880.13  4931.2  874.19  4952.3  871.54
  4954.2  861.29  4955.1  856.29  5050.5  856.29  5053.4  861.29  5059.4  871.05
  5061.4  873.21  5105.5  873.59  5140.5  876.78  5166.7  877.31  5191.0  881.66
  5213.3  891.68  5231.7  902.79  5249.1  910.01  5318.4  932.69  5335.5  934.23
#Mann=4,-1,0
  4496.7    0.08       0  4558.1    0.14       0  4954.2    0.04       0
  5053.4    0.08       0
Bank Sta=4954.2,5053.4
XS Rating Curve= 0
Exp/Cntr=0.5,0.3