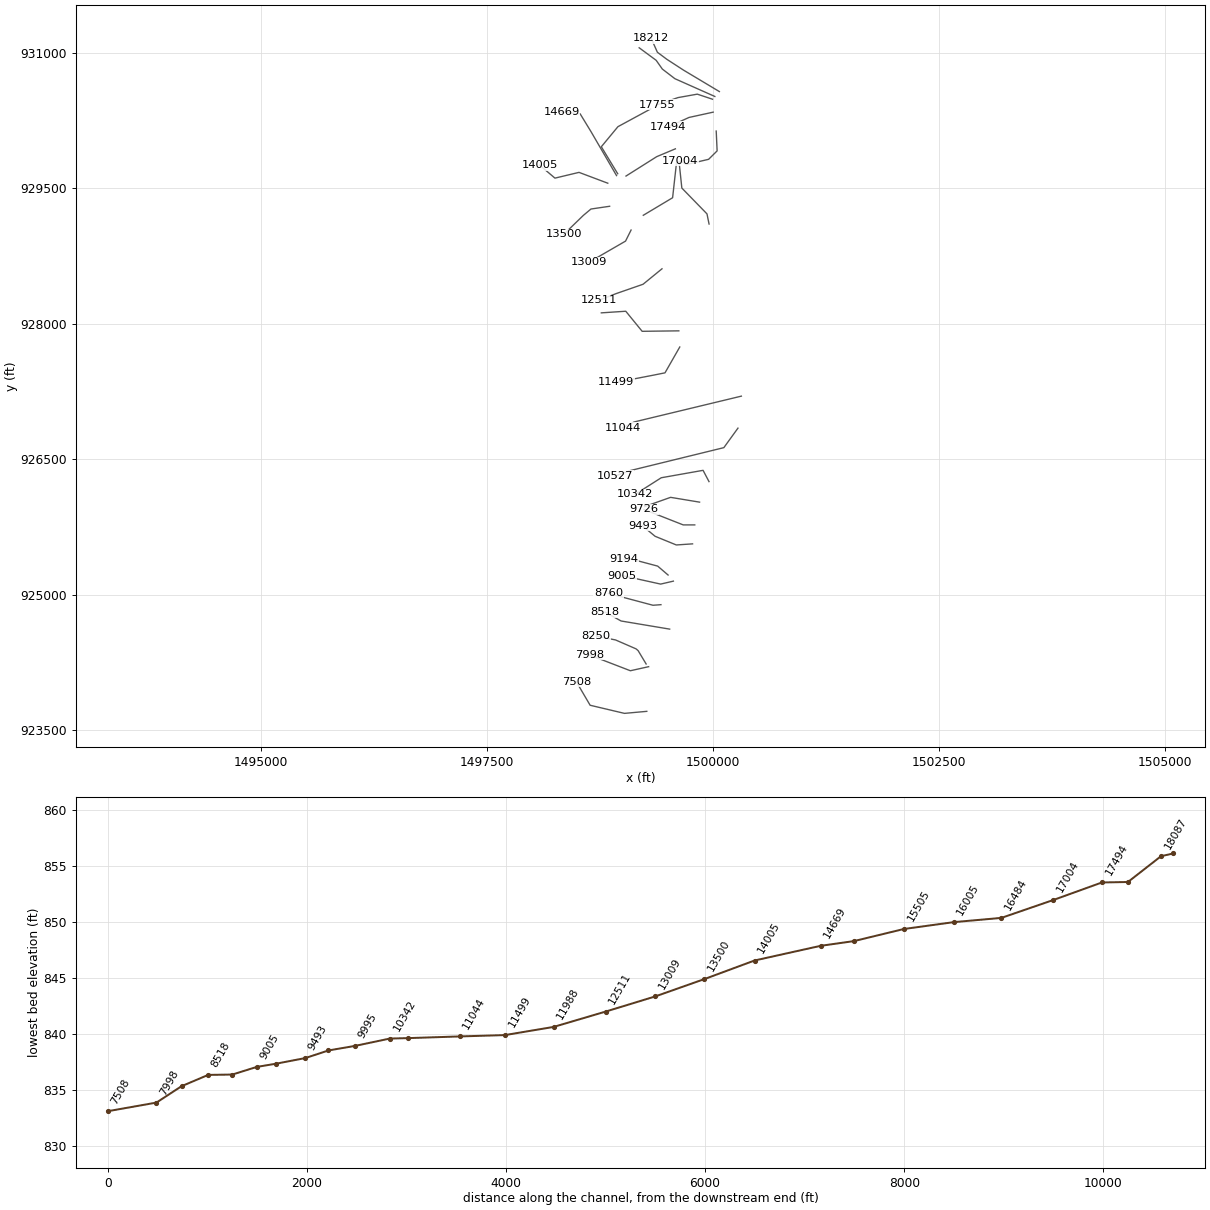
HEC-RAS study Fisher River.prj: Fisher River Limited Detail Study

--- Fisher River.g01 (geometry) --- (continued)

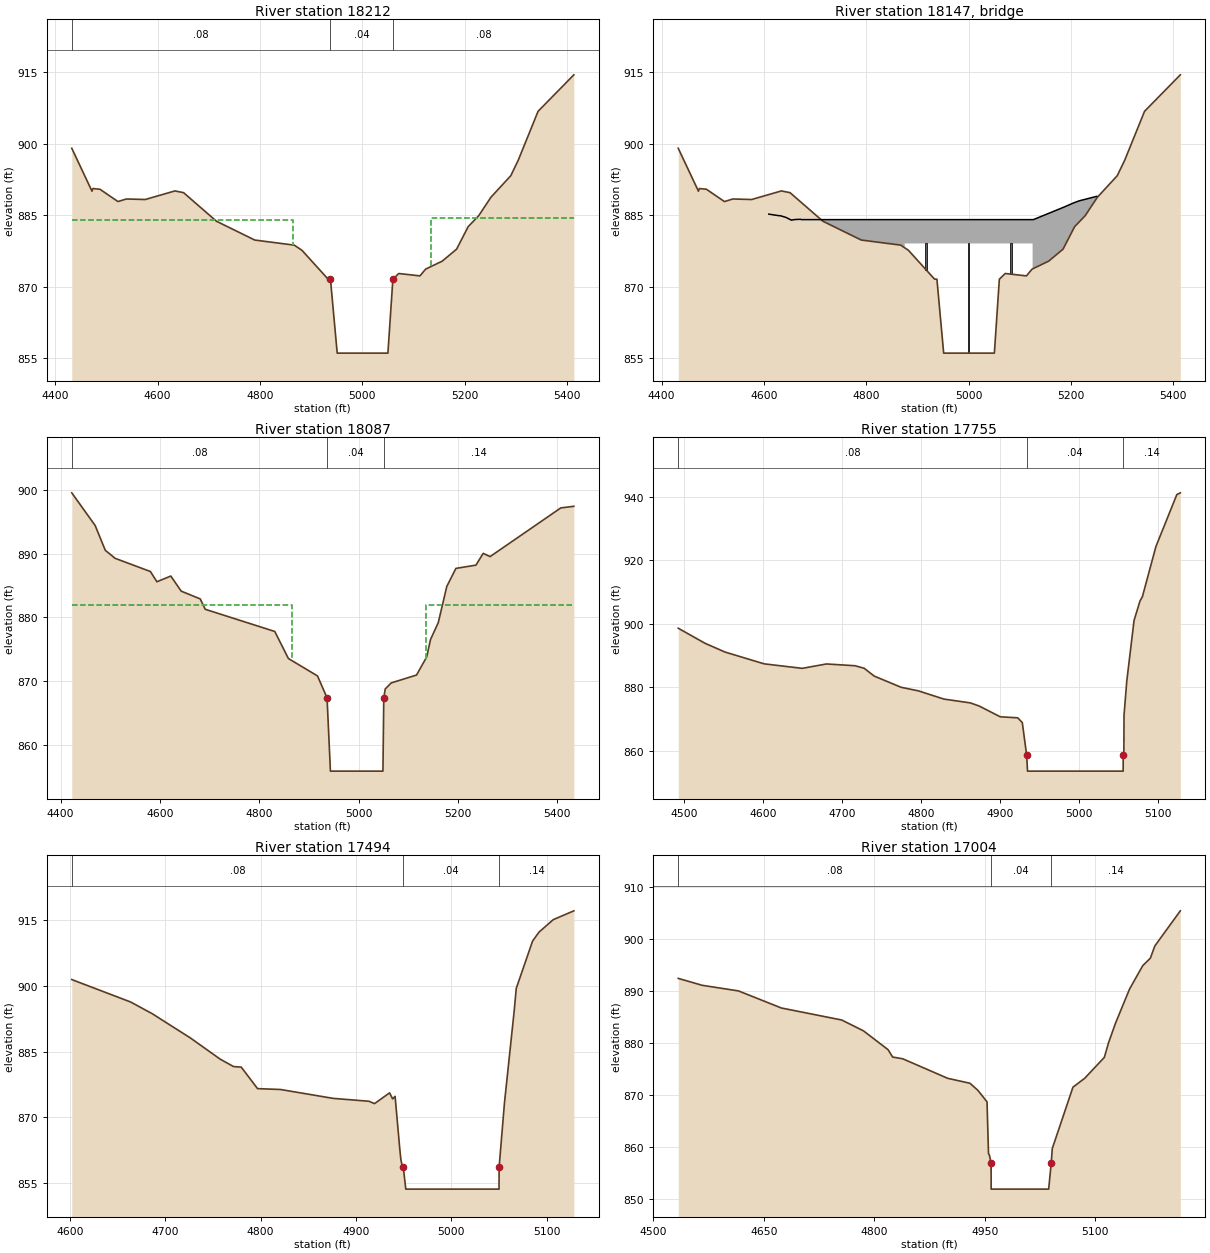
Type RM Length L Ch R = 1,18212,125,125,125
BEGIN DESCRIPTION:
Jenkins Town Road - US
END DESCRIPTION:
XS GIS Cut Line= 5
      1500069.21       930568.51      1499672.05       930806.04
      1499487.74       930925.75      1499383.23       931003.66
      1499314.83       931157.55
#Sta/Elev= 30
  4432.4  899.07  4471.9  890.07  4473.7  890.62  4487.5  890.47  4522.7  887.89
  4539.2  888.43  4576.0  888.32  4634.1  890.12  4651.0  889.75  4715.2  883.76
  4790.0  879.82  4867.2  878.75  4882.3  877.67  4933.3  871.63  4938.0  871.60
  4951.2  856.10  5050.3  856.10  5060.0  871.60  5071.5  872.80  5112.9  872.30
  5124.0  873.72  5156.4  875.39  5184.5  877.90  5207.2  882.63  5227.6  884.90
  5251.7  888.80  5290.5  893.32  5305.2  896.60  5343.8  906.82  5413.7  914.47
#Mann=3,-1,0
  4432.4    0.08       0  4938.0    0.04       0  5060.0    0.08       0
#XS Ineff=2,0
    0.00 4865.00  884.10 5135.00    0.00  884.48
Permanent Ineff=
       F       F
Bank Sta=4938,5060
XS Rating Curve= 0
Exp/Cntr=0.5,0.3

Type RM Length L Ch R =3,18147,,,
BEGIN DESCRIPTION:
Jenkins Town Road - TOR
Structure ID: LDS_FR_02
Approximate Survey Structure
END DESCRIPTION:
Bridge Culvert--1,0,-1,-1,0
Deck Dist Width WeirC Skew NumUp NumDn MinLoCord MaxHiCord MaxSubmerge Is_Ogee
90,28,3,,18,18,,,0.95,0,1,1,,,
  4609.4  4628.7  4631.5  4643.1  4653.1  4653.2  4660.7  4671.1  4673.2  4875.0
  4875.0  5125.0  5125.0  5126.4  5186.6  5206.1  5216.0  5250.2
  885.25  884.93  884.93  884.56  884.01  884.00  884.12  884.17  884.10  884.10
  884.10  884.10  884.10  884.10  886.74  887.65  888.04  888.98
  836.10  836.10  836.10  836.10  836.10  836.10  836.10  836.10  836.10  836.10
  879.10  879.10  836.10  836.10  836.10  836.10  836.10  836.10
  4609.4  4628.7  4631.5  4643.1  4653.1  4653.2  4660.7  4671.1  4673.2  4875.0
  4875.0  5125.0  5125.0  5126.4  5186.6  5206.1  5216.0  5250.2
  885.25  884.93  884.93  884.56  884.01  884.00  884.12  884.17  884.10  884.10
  884.10  884.10  884.10  884.10  886.74  887.65  888.04  888.98
  836.10  836.10  836.10  836.10  836.10  836.10  836.10  836.10  836.10  836.10
  879.10  879.10  836.10  836.10  836.10  836.10  836.10  836.10
Pier Skew, UpSta & Num, DnSta & Num=,4916.7,2,4916.7,2,0,0,0,0,0
       3       3
  875.31  879.10
       3       3
  870.87  879.10
Pier Skew, UpSta & Num, DnSta & Num=,5000,2,5000,2,0,0,0,0,0
       3       3
  856.10  879.10
       3       3
  855.85  879.10
Pier Skew, UpSta & Num, DnSta & Num=,5083.3,2,5083.3,2,0,0,0,0,0
       3       3
  872.86  879.10
       3       3
  866.27  879.10
Abutment Skew #Up #Dn=,2,2
  4875.0  4900.0
  879.10  875.65
  4875.0  4900.0
  879.10  870.91
Abutment Skew #Up #Dn=,2,2
  5100.0  5125.0
  873.08  879.10
  5100.0  5125.0
  870.70  879.10
BR Coef=1,1,0,1.25,0,,,0.8,0,2,0,
WSPro=,,,, 1 ,,,, 0 ,,,, 0 ,,,,-1 ,-1 ,-1 , 0 , 0 , 0 , 0 , 0
BC Design=,,0,,0,,,,,,

Type RM Length L Ch R = 1,18087,332,332,332
BEGIN DESCRIPTION:
Jenkins Town Road - DS
END DESCRIPTION:
XS GIS Cut Line= 5
      1500018.86       930514.52      1499577.04       930711.04
      1499438.33       930817.44      1499369.93       930914.35
      1499181.83       931053.05
#Sta/Elev= 30
  4422.5  899.53  4469.6  894.40  4490.0  890.51  4509.8  889.25  4580.8  887.18
  4593.9  885.57  4621.8  886.47  4642.8  884.10  4681.1  882.88  4691.2  881.25
  4831.2  877.77  4858.5  873.53  4917.2  870.79  4936.4  867.35  4943.2  855.85
  5048.9  855.85  5050.6  867.35  5053.5  868.74  5065.4  869.69  5116.5  870.93
  5137.0  873.77  5144.6  876.49  5160.3  879.16  5177.4  884.83  5195.8  887.67
  5236.1  888.18  5250.7  890.03  5264.6  889.52  5406.9  897.16  5433.2  897.42
#Mann=3,-1,0
  4422.5    0.08       0  4936.4    0.04       0  5050.6    0.14       0
#XS Ineff=2,0
    0.00 4865.00  882.00 5135.00    0.00  882.00
Permanent Ineff=
       F       F
Bank Sta=4936.4,5050.6
XS Rating Curve= 0
Exp/Cntr=0.5,0.3

Type RM Length L Ch R = 1,17755,261,261,261
BEGIN DESCRIPTION:
Fisher River 36.0
END DESCRIPTION:
XS GIS Cut Line= 4
      1499993.31       930483.90      1499824.87       930540.05
      1499610.48       930501.76      1499383.29       930422.63
#Sta/Elev= 30
  4492.5  898.56  4526.3  893.83  4551.8  891.05  4601.3  887.34  4649.5  885.92
  4680.3  887.30  4716.5  886.74  4728.0  885.95  4740.6  883.50  4774.7  879.96
  4796.8  878.82  4829.0  876.24  4862.6  875.03  4873.5  874.07  4900.4  870.66
  4922.5  870.34  4928.3  868.81  4933.8  858.55  4934.9  853.55  5056.0  853.55
  5056.1  858.55  5056.9  858.55  5057.1  871.11  5060.6  881.91  5069.8  900.98
  5077.3  907.11  5080.4  908.51  5097.5  924.28  5124.0  940.65  5128.4  941.20
#Mann=3,-1,0
  4492.5    0.08       0  4933.8    0.04       0  5056.1    0.14       0
Bank Sta=4933.8,5056.1
XS Rating Curve= 0
Exp/Cntr=0.3,0.1

Type RM Length L Ch R = 1,17494,490,490,490
BEGIN DESCRIPTION:
Fisher River 35.0
END DESCRIPTION:
XS GIS Cut Line= 3
      1500000.93       930340.96      1499732.99       930282.26
      1499503.29       930177.63
#Sta/Elev= 30
  4601.9  901.47  4663.7  896.33  4686.2  893.67  4726.4  888.10  4757.5  883.27
  4771.6  881.56  4779.7  881.43  4796.8  876.51  4820.9  876.31  4876.1  874.28
  4913.6  873.62  4919.5  873.08  4935.3  875.54  4938.5  874.16  4941.1  874.74
  4946.1  862.45  4947.2  860.23  4948.4  858.98  4948.5  858.51  4949.7  858.51
  4952.3  853.51  5050.1  853.51  5050.2  858.51  5055.8  873.20  5066.0  894.26
  5068.2  899.46  5085.3  910.27  5092.0  912.32  5107.0  915.18  5128.6  917.20
#Mann=3,-1,0
  4601.9    0.08       0  4949.7    0.04       0  5050.2    0.14       0
Bank Sta=4949.7,5050.2
XS Rating Curve= 0
Exp/Cntr=0.3,0.1

Type RM Length L Ch R = 1,17004,520,520,520
BEGIN DESCRIPTION:
Fisher River 34.0
END DESCRIPTION:
XS GIS Cut Line= 5
      1500034.16       930131.69      1500044.28       929912.32
      1499950.19       929819.18      1499704.91       929761.59
      1499638.52       929802.45
#Sta/Elev= 30
  4533.7  892.43  4566.3  891.10  4615.6  890.02  4673.8  886.74  4755.8  884.43
  4785.2  882.36  4818.7  878.73  4824.9  877.32  4838.6  876.98  4899.7  873.23
  4929.9  872.28  4940.6  870.93  4953.1  868.71  4955.1  858.80  4956.4  858.44
  4958.6  856.94  4958.7  851.94  5036.8  851.94  5040.3  856.94  5041.7  859.73
  5069.8  871.53  5085.7  873.23  5112.4  877.25  5118.2  880.09  5127.4  883.75
  5146.6  890.36  5164.6  894.88  5174.9  896.31  5181.0  898.66  5215.6  905.41
#Mann=3,-1,0
  4533.7    0.08       0  4958.6    0.04       0  5040.3    0.14       0
Bank Sta=4958.6,5040.3
XS Rating Curve= 0
Exp/Cntr=0.3,0.1

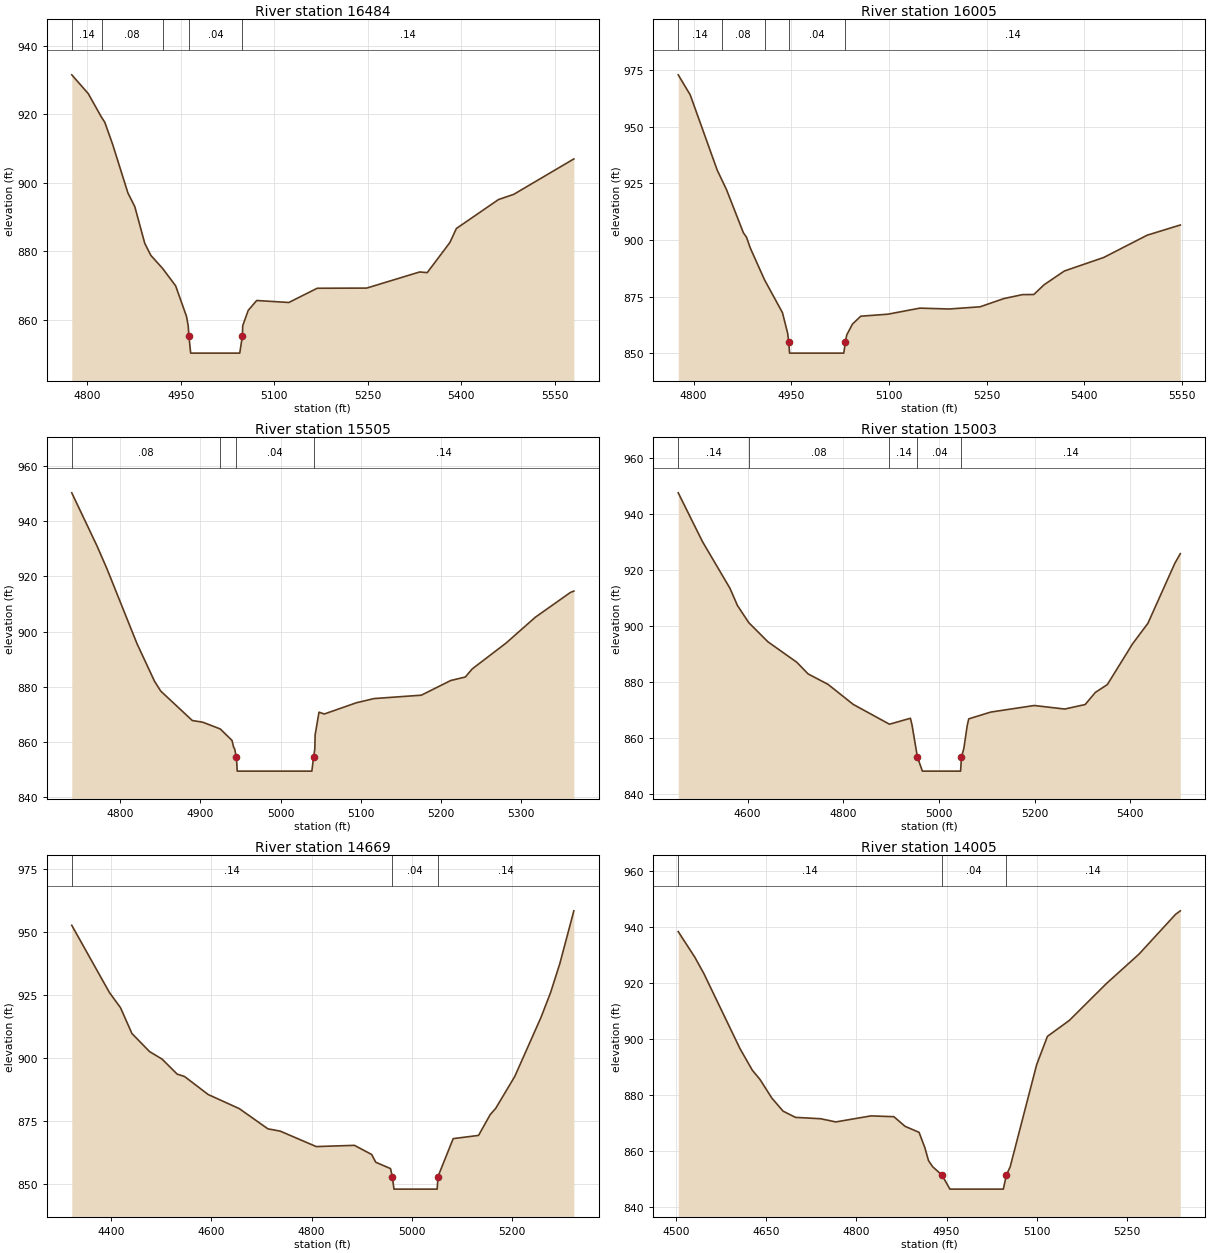
Type RM Length L Ch R = 1,16484,479,479,479
BEGIN DESCRIPTION:
Fisher River 33.0
END DESCRIPTION:
XS GIS Cut Line= 4
      1499955.04       929103.09      1499932.07       929215.40
      1499653.86       929501.26      1499623.24       929792.23
#Sta/Elev= 30
  4774.9  931.52  4801.4  926.03  4822.7  919.14  4827.9  917.70  4840.4  911.31
  4865.1  897.04  4876.1  893.08  4892.1  882.37  4901.9  878.85  4920.9  875.02
  4941.7  869.97  4959.1  861.07  4961.8  858.37  4963.0  855.35  4965.8  850.35
  5044.6  850.35  5048.8  855.35  5049.4  858.38  5058.2  862.81  5071.8  865.70
  5123.4  865.12  5168.9  869.27  5248.4  869.32  5333.4  874.02  5345.6  873.83
  5381.9  882.59  5392.4  886.70  5459.9  895.13  5484.5  896.66  5581.0  906.99
#Mann=5,-1,0
  4774.9    0.14       0  4822.7    0.08       0  4920.9     0.1       0
  4963.0    0.04       0  5048.8    0.14       0
Bank Sta=4963,5048.8
XS Rating Curve= 0
Exp/Cntr=0.3,0.1

Type RM Length L Ch R = 1,16005,500,500,500
BEGIN DESCRIPTION:
Fisher River 32.0
END DESCRIPTION:
XS GIS Cut Line= 3
      1499227.60       929200.07      1499551.77       929394.06
      1499595.16       929784.58
#Sta/Elev= 30
  4776.5  972.99  4794.9  964.13  4836.3  930.90  4843.3  926.66  4850.6  922.24
  4876.5  903.19  4881.3  901.20  4887.3  896.31  4909.0  882.36  4936.5  867.85
  4944.5  858.69  4946.1  854.97  4947.4  849.97  5030.6  849.97  5033.2  854.97
  5035.1  857.97  5043.9  862.80  5056.7  866.29  5098.5  867.19  5147.4  869.86
  5192.6  869.48  5239.9  870.45  5276.4  874.09  5304.9  875.83  5322.3  875.88
  5338.1  880.19  5369.2  886.27  5429.7  892.26  5496.4  902.11  5547.2  906.61
#Mann=5,-1,0
  4776.5    0.14       0  4843.3    0.08       0  4909.0    0.14       0
  4946.1    0.04       0  5033.2    0.14       0
Bank Sta=4946.1,5033.2
XS Rating Curve= 0
Exp/Cntr=0.3,0.1

Type RM Length L Ch R = 1,15505,502,502,502
BEGIN DESCRIPTION:
Fisher River 31.0
END DESCRIPTION:
XS GIS Cut Line= 3
      1499036.18       929633.96      1499375.66       929848.37
      1499582.37       929935.14
#Sta/Elev= 30
  4739.7  950.30  4771.2  931.01  4783.4  922.86  4821.1  895.52  4842.8  881.98
  4850.6  878.39  4889.9  867.72  4903.1  867.09  4924.8  864.65  4939.4  860.50
  4941.5  857.97  4942.6  857.53  4944.9  854.36  4945.9  849.36  5038.9  849.36
  5041.0  854.36  5042.6  857.43  5043.0  862.53  5047.8  870.74  5054.4  870.08
  5094.2  874.14  5116.5  875.68  5175.3  876.90  5211.9  882.22  5230.2  883.50
  5238.7  886.42  5280.7  895.75  5317.5  905.20  5361.3  914.20  5365.4  914.65
#Mann=4,-1,0
  4739.7    0.08       0  4924.8    0.14       0  4944.9    0.04       0
  5041.0    0.14       0
Bank Sta=4944.9,5041
XS Rating Curve= 0
Exp/Cntr=0.3,0.1

Type RM Length L Ch R = 1,15003,334,334,334
BEGIN DESCRIPTION:
Fisher River 30.0
END DESCRIPTION:
XS GIS Cut Line= 4
      1498944.34       929659.48      1498763.11       929958.12
      1498946.88       930180.17      1499309.27       930376.68
#Sta/Elev= 30
  4454.8  947.52  4505.4  930.15  4563.1  913.43  4578.6  907.34  4602.4  901.21
  4642.3  894.40  4702.8  887.09  4726.3  882.95  4768.0  879.22  4820.8  872.06
  4896.5  865.01  4940.3  867.13  4943.7  864.68  4954.9  853.28  4965.3  848.28
  5045.2  848.28  5047.0  853.28  5052.0  856.39  5059.2  864.69  5062.3  866.92
  5108.3  869.34  5199.2  871.68  5262.9  870.42  5305.7  872.03  5326.9  876.34
  5352.1  879.16  5404.7  893.66  5436.9  901.01  5493.1  922.38  5504.6  925.83
#Mann=5,-1,0
  4454.8    0.14       0  4602.4    0.08       0  4896.5    0.14       0
  4954.9    0.04       0  5047.0    0.14       0
Bank Sta=4954.9,5047
XS Rating Curve= 0
Exp/Cntr=0.3,0.1

Type RM Length L Ch R = 1,14669,664,664,664
BEGIN DESCRIPTION:
Fisher River 29.5
END DESCRIPTION:
XS GIS Cut Line= 4
      1498931.57       929639.07      1498648.26       930126.57
      1498528.30       930323.10      1498321.57       930340.97
#Sta/Elev= 30
  4321.4  952.71  4396.5  926.01  4418.7  919.94  4441.4  909.71  4476.6  902.52
  4501.5  899.54  4531.6  893.58  4546.5  892.60  4593.6  885.45  4655.5  879.86
  4712.7  871.82  4737.1  870.92  4809.1  864.77  4885.3  865.26  4919.6  861.64
  4927.9  858.54  4957.3  856.02  4960.8  852.86  4964.2  847.86  5050.3  847.86
  5052.0  852.86  5082.3  867.93  5132.9  869.21  5156.1  877.46  5167.1  879.95
  5205.1  892.63  5257.5  916.13  5276.7  926.03  5295.1  937.53  5323.0  958.46
#Mann=3,-1,0
  4321.4    0.14       0  4960.8    0.04       0  5052.0    0.14       0
Bank Sta=4960.8,5052
XS Rating Curve= 0
Exp/Cntr=0.3,0.1

Type RM Length L Ch R = 1,14005,505,505,505
BEGIN DESCRIPTION:
Fisher River 28.0
END DESCRIPTION:
XS GIS Cut Line= 4
      1498834.60       929554.85      1498516.31       929674.62
      1498250.10       929611.01      1498081.65       929753.93
#Sta/Elev= 30
  4503.9  938.47  4531.4  929.36  4546.4  923.54  4606.6  896.70  4627.1  888.99
  4639.6  885.77  4659.7  879.00  4678.3  874.38  4699.0  872.16  4740.6  871.68
  4765.9  870.54  4824.3  872.69  4862.4  872.41  4880.9  868.98  4904.3  866.82
  4913.9  861.35  4920.0  856.71  4926.8  854.57  4942.4  851.55  4955.6  846.55
  5044.4  846.55  5049.4  851.55  5055.8  854.55  5099.8  891.00  5117.7  901.09
  5154.1  906.77  5215.4  919.86  5270.0  930.45  5330.8  944.66  5338.6  945.89
#Mann=3,-1,0
  4503.9    0.14       0  4942.4    0.04       0  5049.4    0.14       0
Bank Sta=4942.4,5049.4
XS Rating Curve= 0
Exp/Cntr=0.3,0.1

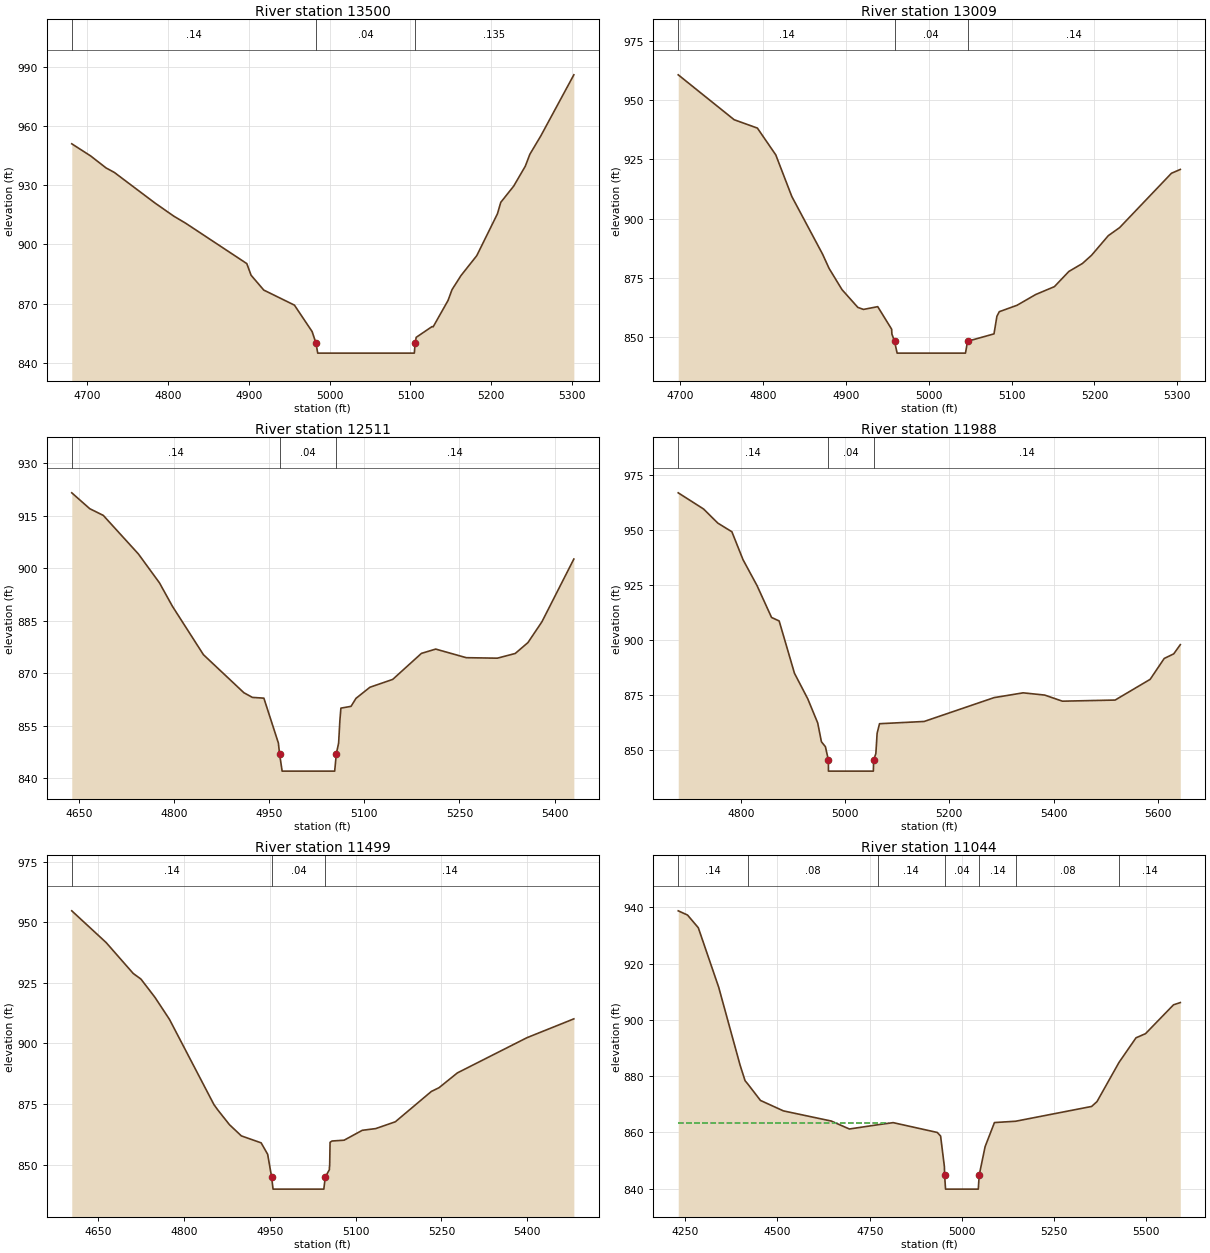
Type RM Length L Ch R = 1,13500,491,491,491
BEGIN DESCRIPTION:
Fisher River 27.0
END DESCRIPTION:
XS GIS Cut Line= 4
      1498855.02       929299.63      1498648.52       929269.18
      1498564.03       929198.48      1498347.09       928988.25
#Sta/Elev= 30
  4681.1  951.04  4704.4  944.90  4723.6  938.78  4733.7  936.54  4784.1  920.99
  4807.4  914.32  4822.1  910.74  4897.6  890.29  4902.9  884.38  4918.6  876.86
  4956.5  869.23  4978.4  855.81  4983.2  849.89  4985.3  844.89  5104.8  844.89
  5105.8  849.89  5107.1  852.89  5126.7  858.35  5128.1  858.23  5146.5  871.60
  5151.4  877.06  5162.6  884.27  5182.0  894.30  5207.6  915.55  5211.7  921.35
  5227.7  929.59  5242.0  939.64  5247.7  945.73  5261.2  955.02  5302.1  986.02
#Mann=3,-1,0
  4681.1    0.14       0  4983.2    0.04       0  5105.8   0.135       0
Bank Sta=4983.2,5105.8
XS Rating Curve= 0
Exp/Cntr=0.3,0.1

Type RM Length L Ch R = 1,13009,498,498,498
BEGIN DESCRIPTION:
Fisher River 26.0
END DESCRIPTION:
XS GIS Cut Line= 3
      1499092.37       929036.76      1499031.10       928914.23
      1498625.33       928679.44
#Sta/Elev= 30
  4697.8  960.60  4765.3  941.68  4793.3  938.16  4815.5  926.87  4834.8  909.37
  4872.0  885.03  4879.8  879.05  4895.4  870.10  4914.5  862.62  4921.3  861.76
  4938.5  862.93  4955.3  853.43  4955.6  851.38  4958.8  848.35  4961.9  843.35
  5044.4  843.35  5046.9  848.35  5078.8  851.46  5082.3  858.87  5085.2  860.81
  5106.6  863.51  5129.1  868.04  5151.7  871.36  5169.1  877.75  5185.5  881.12
  5196.6  884.61  5216.7  892.84  5230.4  896.24  5292.9  919.13  5303.6  920.74
#Mann=3,-1,0
  4697.8    0.14       0  4958.8    0.04       0  5046.9    0.14       0
Bank Sta=4958.8,5046.9
XS Rating Curve= 0
Exp/Cntr=0.3,0.1

Type RM Length L Ch R = 1,12511,523,523,523
BEGIN DESCRIPTION:
Fisher River 25.0
END DESCRIPTION:
XS GIS Cut Line= 4
      1499434.34       928607.93      1499225.08       928436.95
      1498923.91       928332.31      1498735.06       928258.30
#Sta/Elev= 30
  4638.6  921.56  4666.9  917.03  4688.3  915.11  4743.7  904.08  4776.9  895.83
  4797.4  889.11  4846.3  875.28  4910.1  864.41  4923.5  863.08  4941.6  862.86
  4964.5  850.02  4966.3  847.00  4970.4  842.00  5053.3  842.00  5055.9  847.00
  5059.5  850.01  5061.5  856.51  5063.1  860.01  5079.1  860.52  5086.9  862.81
  5108.9  865.98  5144.8  868.22  5190.1  875.66  5212.6  876.89  5260.8  874.43
  5309.8  874.29  5338.0  875.63  5358.1  878.74  5380.2  884.71  5430.5  902.63
#Mann=3,-1,0
  4638.6    0.14       0  4966.3    0.04       0  5055.9    0.14       0
Bank Sta=4966.3,5055.9
XS Rating Curve= 0
Exp/Cntr=0.3,0.1

Type RM Length L Ch R = 1,11988,489,489,489
BEGIN DESCRIPTION:
Fisher River 24.0
END DESCRIPTION:
XS GIS Cut Line= 4
      1499620.69       927921.39      1499214.87       927916.28
      1499033.66       928138.33      1498763.11       928120.46
#Sta/Elev= 30
  4679.7  967.00  4728.3  959.66  4755.7  953.25  4782.7  949.31  4804.0  936.66
  4830.9  924.89  4858.8  910.41  4873.4  908.82  4902.8  885.06  4928.3  873.45
  4947.4  862.50  4954.5  853.97  4962.2  851.71  4967.9  845.63  4968.0  840.63
  5054.2  840.63  5054.7  845.63  5059.0  848.63  5061.4  857.81  5066.0  862.16
  5151.7  863.18  5285.8  874.00  5341.7  876.18  5383.1  875.16  5417.0  872.39
  5518.2  872.90  5585.4  882.30  5612.4  891.79  5630.7  893.88  5643.3  898.06
#Mann=3,-1,0
  4679.7    0.14       0  4967.9    0.04       0  5054.7    0.14       0
Bank Sta=4967.9,5054.7
XS Rating Curve= 0
Exp/Cntr=0.3,0.1

Type RM Length L Ch R = 1,11499,455,455,455
BEGIN DESCRIPTION:
Fisher River 23.0
END DESCRIPTION:
XS GIS Cut Line= 4
      1499630.89       927742.72      1499467.55       927456.87
      1499327.17       927428.79      1498929.06       927352.23
#Sta/Elev= 30
  4603.7  954.71  4663.8  941.62  4711.2  928.86  4724.6  926.56  4749.2  919.00
  4774.5  909.94  4852.3  874.76  4859.6  872.39  4879.3  866.51  4900.2  861.86
  4934.8  858.99  4946.2  854.26  4953.1  844.90  4955.6  839.90  5044.4  839.90
  5046.9  844.90  5054.1  847.91  5054.2  849.00  5054.6  849.46  5055.3  859.22
  5058.8  859.75  5079.9  860.09  5111.6  864.16  5135.2  864.88  5169.4  867.68
  5232.4  880.20  5245.8  881.74  5277.9  887.85  5399.4  902.36  5481.5  910.14
#Mann=3,-1,0
  4603.7    0.14       0  4953.1    0.04       0  5046.9    0.14       0
Bank Sta=4953.1,5046.9
XS Rating Curve= 0
Exp/Cntr=0.3,0.1

Type RM Length L Ch R = 1,11044,517,517,517
BEGIN DESCRIPTION:
Fisher River 22.0
END DESCRIPTION:
XS GIS Cut Line= 3
      1500312.38       927199.09      1499125.54       926913.23
      1499000.46       926849.41
#Sta/Elev= 30
  4230.9  938.74  4256.1  937.24  4285.3  932.73  4340.6  911.56  4398.7  883.82
  4412.1  878.34  4420.0  877.08  4453.9  871.31  4516.1  867.60  4645.8  863.99
  4694.9  861.16  4772.6  862.68  4813.6  863.42  4933.2  859.93  4942.2  858.66
  4952.5  847.78  4953.1  844.78  4955.6  839.78  5044.4  839.78  5046.9  844.78
  5062.9  854.89  5088.2  863.45  5145.7  863.92  5351.7  869.18  5366.2  870.90
  5425.9  884.84  5472.0  893.59  5497.8  895.06  5573.7  905.32  5592.1  906.12
#Mann=7,-1,0
  4230.9    0.14       0  4420.0    0.08       0  4772.6    0.14       0
  4953.1    0.04       0  5046.9    0.14       0  5145.7    0.08       0
  5425.9    0.14       0
#XS Ineff=2,0
    0.00 4802.90  863.39               0
Permanent Ineff=
       F       F
Bank Sta=4953.1,5046.9
XS Rating Curve= 0
Exp/Cntr=0.3,0.1

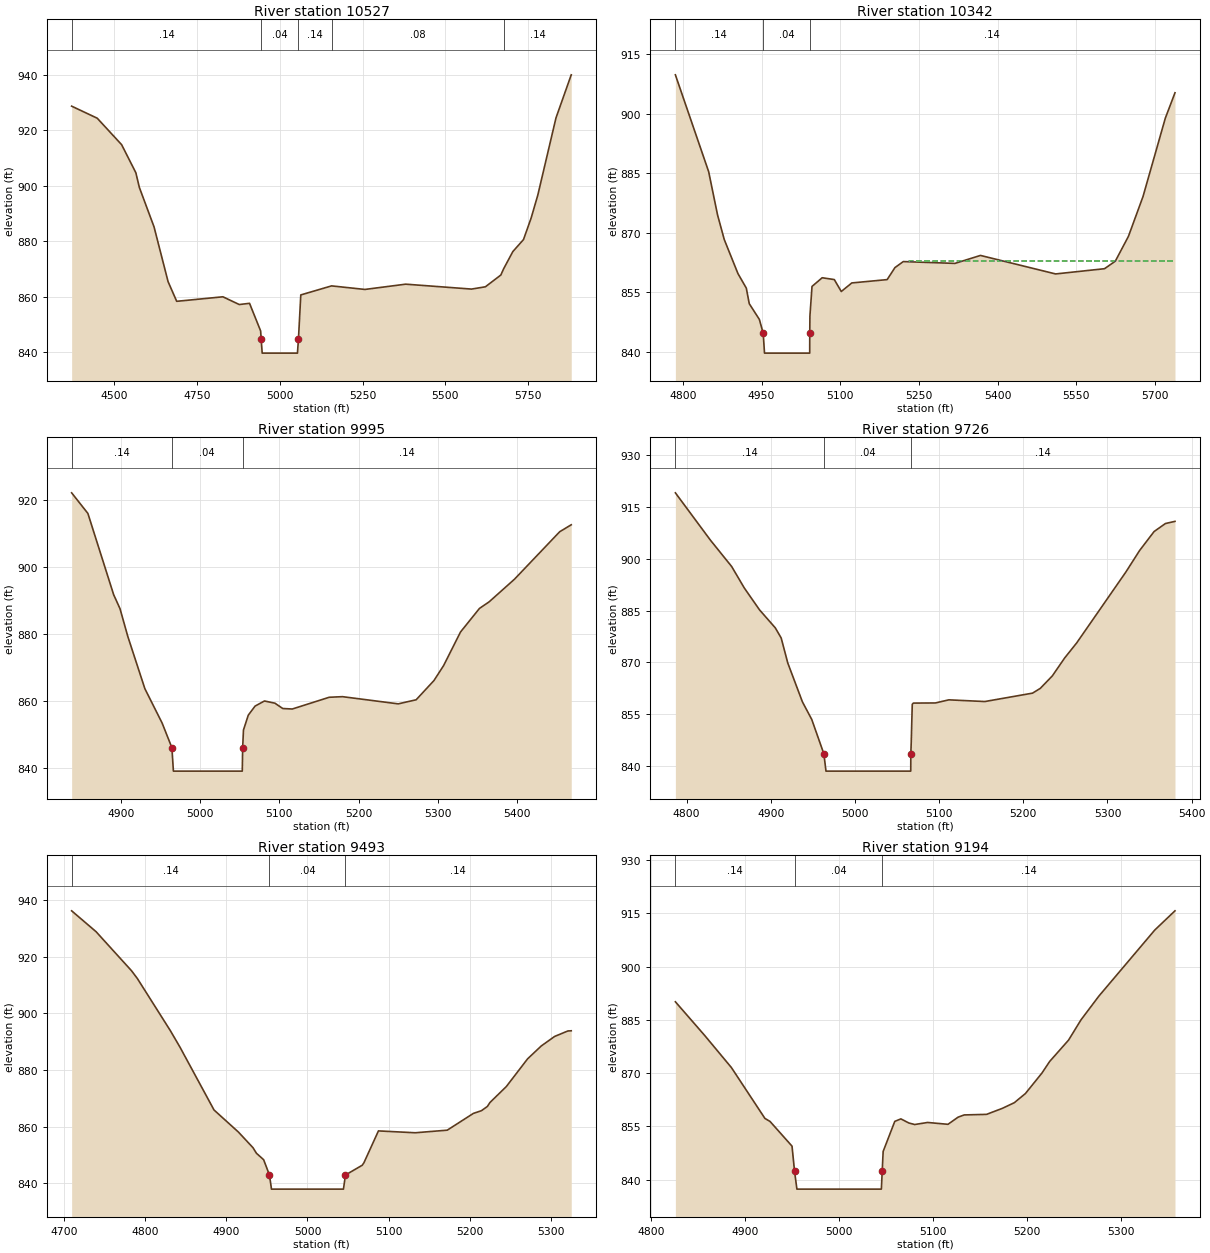
Type RM Length L Ch R = 1,10527,185,185,185
BEGIN DESCRIPTION:
Fisher River 21.0
END DESCRIPTION:
XS GIS Cut Line= 4
      1500274.86       926845.11      1500118.64       926629.26
      1499079.60       926374.69      1498916.26       926315.99
#Sta/Elev= 30
  4370.9  928.63  4448.2  924.29  4522.0  914.74  4564.9  904.65  4575.6  899.32
  4619.9  885.13  4662.3  865.41  4688.4  858.30  4828.0  859.93  4877.5  857.14
  4908.5  857.58  4942.0  847.63  4943.7  844.63  4946.7  839.63  5053.3  839.63
  5056.3  844.63  5063.4  860.60  5156.4  863.86  5257.2  862.58  5380.5  864.48
  5579.3  862.71  5621.2  863.53  5668.0  867.78  5676.0  869.93  5704.2  876.22
  5736.4  880.55  5759.4  888.27  5779.6  896.55  5834.6  924.40  5880.7  939.92
#Mann=5,-1,0
  4370.9    0.14       0  4943.7    0.04       0  5056.3    0.14       0
  5156.4    0.08       0  5676.0    0.14       0
Bank Sta=4943.7,5056.3
XS Rating Curve= 0
Exp/Cntr=0.3,0.1

Type RM Length L Ch R = 1,10342,347,347,347
BEGIN DESCRIPTION:
Fisher River 20.5
END DESCRIPTION:
XS GIS Cut Line= 4
      1499954.41       926253.54      1499888.78       926378.23
      1499426.18       926296.21      1499137.50       926112.50
#Sta/Elev= 30
  4785.6  909.81  4849.1  885.36  4866.0  874.48  4878.8  868.26  4904.9  859.67
  4920.9  855.98  4926.5  852.07  4945.8  848.09  4953.1  844.59  4955.6  839.59
  5041.8  839.59  5041.9  844.59  5042.2  848.93  5046.2  856.42  5065.6  858.61
  5088.7  858.15  5102.0  855.14  5122.1  857.30  5189.5  858.14  5204.4  861.17
  5220.3  862.69  5318.8  862.23  5367.5  864.24  5510.8  859.57  5604.1  860.89
  5624.7  862.79  5649.7  869.05  5677.5  879.09  5720.1  898.88  5738.5  905.28
#Mann=3,-1,0
  4785.6    0.14       0  4953.1    0.04       0  5041.9    0.14       0
#XS Ineff=2,0
       0                 5231.10    0.00  862.74
Permanent Ineff=
       F       F
Bank Sta=4953.1,5041.9
XS Rating Curve= 0
Exp/Cntr=0.3,0.1

Type RM Length L Ch R = 1,9995,269,269,269
BEGIN DESCRIPTION:
Fisher River 20.0
END DESCRIPTION:
XS GIS Cut Line= 3
      1499850.17       926026.30      1499529.57       926079.39
      1499241.70       925977.31
#Sta/Elev= 30
  4838.0  922.14  4858.5  915.98  4891.0  891.70  4899.0  887.52  4908.9  879.18
  4930.4  863.59  4952.2  853.30  4964.5  845.94  4966.4  838.94  5053.3  838.94
  5053.8  845.94  5054.8  851.22  5060.9  855.68  5069.5  858.39  5081.3  859.91
  5094.5  859.25  5104.4  857.66  5116.4  857.51  5163.0  861.02  5179.8  861.20
  5250.1  859.05  5272.7  860.27  5295.1  866.00  5307.3  870.47  5328.7  880.54
  5352.6  887.58  5364.8  889.55  5396.8  896.32  5453.8  910.50  5468.4  912.59
#Mann=3,-1,0
  4838.0    0.14       0  4964.5    0.04       0  5053.8    0.14       0
#XS Ineff=2,0
       0                 5179.80    0.00  861.20
Permanent Ineff=
       F       F
Bank Sta=4964.5,5053.8
XS Rating Curve= 0
Exp/Cntr=0.3,0.1

Type RM Length L Ch R = 1,9726,233,233,233
BEGIN DESCRIPTION:
Fisher River 19.5
END DESCRIPTION:
XS GIS Cut Line= 3
      1499796.96       925774.56      1499668.96       925774.56
      1499235.85       925945.18
#Sta/Elev= 30
  4786.7  919.07  4828.3  905.38  4853.6  897.73  4868.6  891.52  4886.7  885.19
  4905.4  879.99  4912.4  877.05  4920.2  869.84  4937.6  858.58  4948.7  853.48
  4963.1  843.53  4965.6  838.53  5066.3  838.53  5066.4  843.53  5066.9  847.03
  5068.1  857.87  5069.4  858.22  5095.6  858.26  5111.6  859.16  5154.3  858.67
  5211.0  861.10  5220.2  862.48  5234.5  866.09  5249.1  871.26  5263.5  875.66
  5321.8  896.13  5338.1  902.35  5355.4  907.87  5368.9  910.19  5380.2  910.81
#Mann=3,-1,0
  4786.7    0.14       0  4963.1    0.04       0  5066.4    0.14       0
Bank Sta=4963.1,5066.4
XS Rating Curve= 0
Exp/Cntr=0.3,0.1

Type RM Length L Ch R = 1,9493,299,299,299
BEGIN DESCRIPTION:
Fisher River 19.0
END DESCRIPTION:
XS GIS Cut Line= 4
      1499772.50       925564.84      1499592.86       925552.60
      1499358.05       925648.56      1499217.14       925764.97
#Sta/Elev= 30
  4709.0  936.31  4739.1  928.94  4782.9  915.11  4790.1  912.36  4830.8  893.92
  4842.8  888.02  4884.7  865.85  4914.8  858.04  4932.8  852.50  4937.0  850.55
  4945.9  848.26  4953.1  842.85  4955.6  837.85  5044.4  837.85  5046.9  842.85
  5067.6  846.31  5069.7  847.20  5087.6  858.45  5133.0  857.79  5172.5  858.71
  5204.8  864.65  5214.7  865.60  5222.1  867.12  5225.2  868.50  5245.4  874.14
  5271.6  883.93  5288.5  888.50  5305.0  891.87  5321.3  893.80  5325.5  893.87
#Mann=3,-1,0
  4709.0    0.14       0  4953.1    0.04       0  5046.9    0.14       0
Bank Sta=4953.1,5046.9
XS Rating Curve= 0
Exp/Cntr=0.3,0.1

Type RM Length L Ch R = 1,9194,189,189,189
BEGIN DESCRIPTION:
Fisher River 18.5
END DESCRIPTION:
XS GIS Cut Line= 4
      1499501.68       925220.07      1499386.81       925318.52
      1499091.54       925397.26      1499016.09       925393.98
#Sta/Elev= 30
  4825.5  890.09  4856.5  880.68  4885.2  871.57  4920.9  857.26  4926.4  856.39
  4949.8  849.44  4952.5  842.34  4955.0  837.34  5045.0  837.34  5045.9  842.34
  5046.9  847.95  5059.3  856.41  5065.8  857.12  5074.3  855.96  5080.5  855.53
  5094.3  856.11  5116.0  855.59  5126.8  857.61  5133.3  858.23  5157.1  858.39
  5174.0  860.09  5186.7  861.68  5198.5  864.25  5216.1  870.01  5224.3  873.27
  5244.5  879.30  5257.7  884.99  5276.8  891.69  5336.4  910.30  5357.9  915.70
#Mann=3,-1,0
  4825.5    0.14       0  4952.5    0.04       0  5045.9    0.14       0
Bank Sta=4952.5,5045.9
XS Rating Curve= 0
Exp/Cntr=0.3,0.1

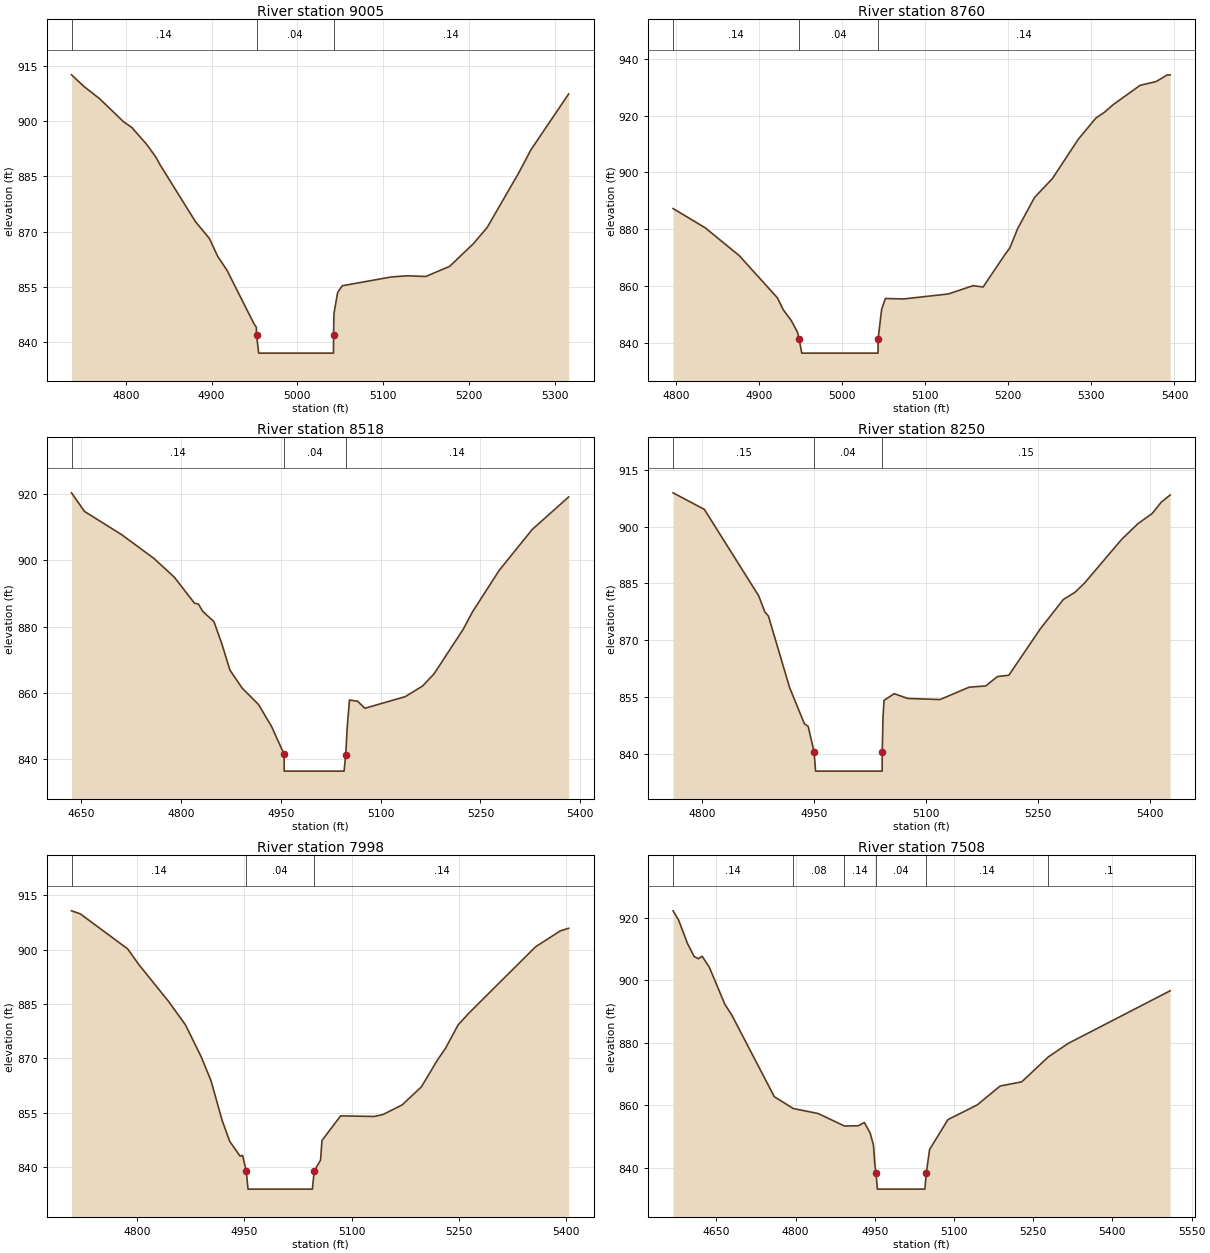
Type RM Length L Ch R = 1,9005,245,245,245
BEGIN DESCRIPTION:
Fisher River 18.0
END DESCRIPTION:
XS GIS Cut Line= 3
      1499560.21       925152.40      1499419.31       925119.73
      1498994.61       925213.65
#Sta/Elev= 30
  4736.8  912.51  4751.2  909.38  4769.7  906.00  4797.6  899.77  4807.0  898.26
  4824.3  893.69  4835.4  890.12  4840.0  888.13  4881.4  872.67  4897.5  868.17
  4907.2  863.31  4918.2  859.47  4949.5  845.03  4952.3  844.06  4952.5  842.06
  4955.0  837.06  5042.2  837.06  5042.3  842.06  5042.8  847.82  5047.0  853.45
  5052.4  855.33  5109.9  857.72  5127.8  858.02  5149.8  857.84  5177.6  860.58
  5205.2  866.70  5221.4  871.13  5258.2  885.93  5272.6  892.26  5316.4  907.33
#Mann=3,-1,0
  4736.8    0.14       0  4952.5    0.04       0  5042.3    0.14       0
Bank Sta=4952.5,5042.3
XS Rating Curve= 0
Exp/Cntr=0.3,0.1

Type RM Length L Ch R = 1,8760,242,242,242
BEGIN DESCRIPTION:
Fisher River 17.5
END DESCRIPTION:
XS GIS Cut Line= 3
      1499422.87       924892.01      1499334.32       924885.46
      1498842.21       925016.68
#Sta/Elev= 30
  4796.8  887.28  4835.4  880.51  4876.4  870.70  4922.4  855.82  4929.2  851.74
  4938.9  847.89  4946.3  843.88  4948.5  841.38  4951.6  836.38  5043.4  836.38
  5043.5  841.38  5047.7  851.75  5052.2  855.61  5074.1  855.45  5127.9  857.20
  5157.7  860.12  5169.8  859.65  5195.9  871.01  5201.8  873.33  5211.4  880.23
  5231.6  891.15  5253.2  897.84  5284.2  911.62  5305.3  919.07  5315.7  921.15
  5326.4  923.87  5358.7  930.64  5378.1  931.99  5391.6  934.34  5394.9  934.29
#Mann=3,-1,0
  4796.8    0.14       0  4948.5    0.04       0  5043.5    0.14       0
Bank Sta=4948.5,5043.5
XS Rating Curve= 0
Exp/Cntr=0.3,0.1

Type RM Length L Ch R = 1,8518,268,268,268
BEGIN DESCRIPTION:
Fisher River 17.0
END DESCRIPTION:
XS GIS Cut Line= 3
      1499519.36       924621.52      1498982.35       924711.36
      1498804.76       924809.34
#Sta/Elev= 30
  4635.3  920.41  4654.8  914.80  4710.7  907.77  4759.2  900.59  4789.8  894.94
  4820.0  887.10  4826.1  886.80  4832.6  884.59  4849.4  881.51  4861.5  874.64
  4873.5  866.84  4891.8  861.43  4916.4  856.47  4936.0  849.84  4954.9  841.45
  4955.0  836.35  5045.0  836.35  5047.5  841.35  5049.7  849.51  5053.1  857.83
  5065.4  857.46  5076.2  855.34  5137.0  858.85  5163.1  862.08  5180.2  865.73
  5224.0  879.17  5237.6  884.30  5278.0  896.95  5327.8  909.34  5382.6  919.17
#Mann=3,-1,0
  4635.3    0.14       0  4954.9    0.04       0  5047.5    0.14       0
Bank Sta=4954.9,5047.5
XS Rating Curve= 0
Exp/Cntr=0.3,0.1

Type RM Length L Ch R = 1,8250,252,252,252
BEGIN DESCRIPTION:
Fisher River 16.5
END DESCRIPTION:
XS GIS Cut Line= 5
      1499258.84       924235.89      1499170.28       924383.49
      1499147.31       924403.17      1498920.94       924501.60
      1498707.69       924544.25
#Sta/Elev= 30
  4760.9  908.99  4802.9  904.60  4875.7  881.74  4884.0  877.46  4888.8  876.37
  4917.2  857.44  4937.0  847.89  4942.1  847.18  4950.1  840.34  4952.0  835.34
  5041.3  835.34  5041.4  840.34  5042.5  849.72  5043.8  854.07  5057.5  855.84
  5075.4  854.58  5118.9  854.28  5157.9  857.55  5180.3  857.89  5195.9  860.37
  5211.2  860.72  5253.1  872.91  5284.2  880.75  5299.8  882.66  5312.3  885.02
  5363.0  896.79  5384.3  900.82  5403.5  903.54  5415.7  906.55  5427.6  908.43
#Mann=3,-1,0
  4760.9    0.15       0  4950.1    0.04       0  5041.4    0.15       0
Bank Sta=4950.1,5041.4
XS Rating Curve= 0
Exp/Cntr=0.3,0.1

Type RM Length L Ch R = 1,7998,490,490,490
BEGIN DESCRIPTION:
Fisher River 16.0
END DESCRIPTION:
XS GIS Cut Line= 3
      1499286.63       924206.01      1499084.45       924161.08
      1498629.15       924336.67
#Sta/Elev= 30
  4708.2  910.72  4720.4  909.90  4786.7  900.21  4802.4  895.87  4843.9  885.71
  4867.5  879.24  4889.1  870.60  4903.2  863.85  4918.7  852.91  4929.4  847.08
  4944.0  842.95  4947.4  843.21  4952.5  838.88  4955.0  833.88  5045.0  833.88
  5047.5  838.88  5056.4  841.88  5058.4  847.32  5084.4  854.10  5131.4  853.95
  5143.5  854.46  5170.5  857.14  5197.4  862.12  5220.1  869.61  5231.1  872.75
  5248.8  879.25  5264.1  882.53  5356.7  900.74  5391.7  905.20  5403.3  905.90
#Mann=3,-1,0
  4708.2    0.14       0  4952.5    0.04       0  5047.5    0.14       0
Bank Sta=4952.5,5047.5
XS Rating Curve= 0
Exp/Cntr=0.3,0.1

Type RM Length L Ch R = 1,7508,492,492,492
BEGIN DESCRIPTION:
Fisher River 15.0
END DESCRIPTION:
XS GIS Cut Line= 4
      1499266.14       923711.87      1499019.11       923689.42
      1498639.33       923779.26      1498486.20       924040.59
#Sta/Elev= 30
  4568.2  922.14  4578.7  919.18  4595.6  911.65  4608.2  907.50  4616.3  906.81
  4623.1  907.62  4636.9  904.09  4666.1  892.30  4680.1  888.57  4759.9  862.67
  4795.8  858.90  4842.8  857.30  4892.7  853.30  4918.7  853.37  4930.3  854.42
  4941.3  851.08  4947.6  847.16  4950.2  841.11  4952.5  838.11  4955.0  833.11
  5045.0  833.11  5047.5  838.11  5053.8  845.77  5088.6  855.35  5144.0  860.05
  5187.5  866.11  5228.3  867.43  5278.5  875.39  5315.9  879.69  5509.4  896.57
#Mann=6,-1,0
  4568.2    0.14       0  4795.8    0.08       0  4892.7    0.14       0
  4952.5    0.04       0  5047.5    0.14       0  5278.5     0.1       0
Bank Sta=4952.5,5047.5
XS Rating Curve= 0
Exp/Cntr=0.3,0.1