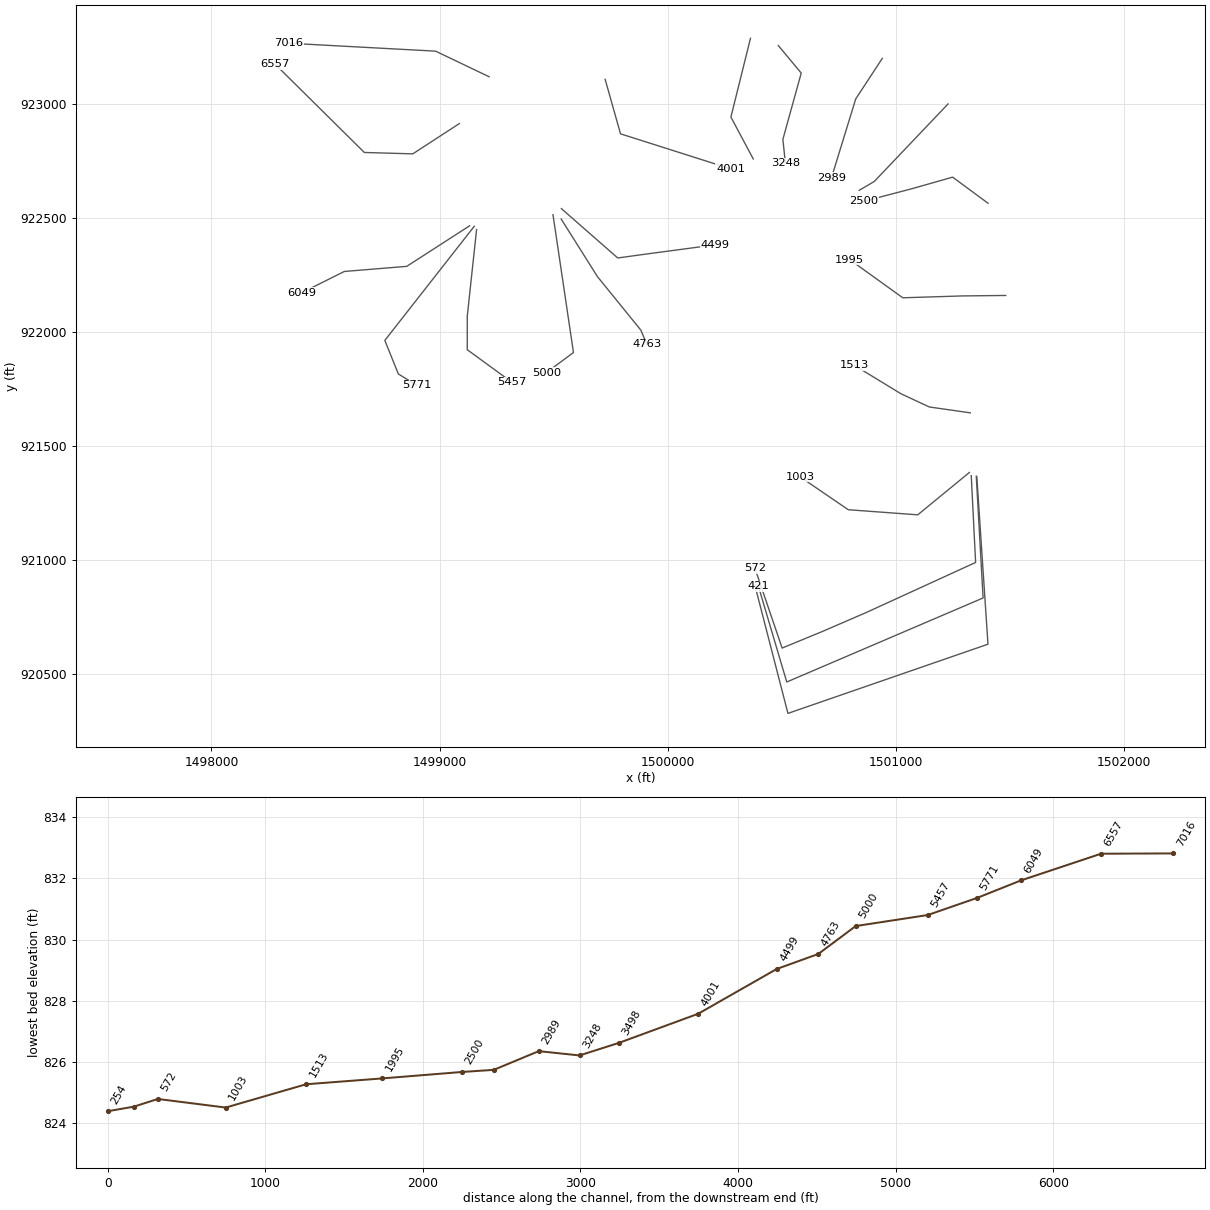
HEC-RAS study Fisher River.prj: Fisher River Limited Detail Study

--- Fisher River.g01 (geometry) --- (continued)

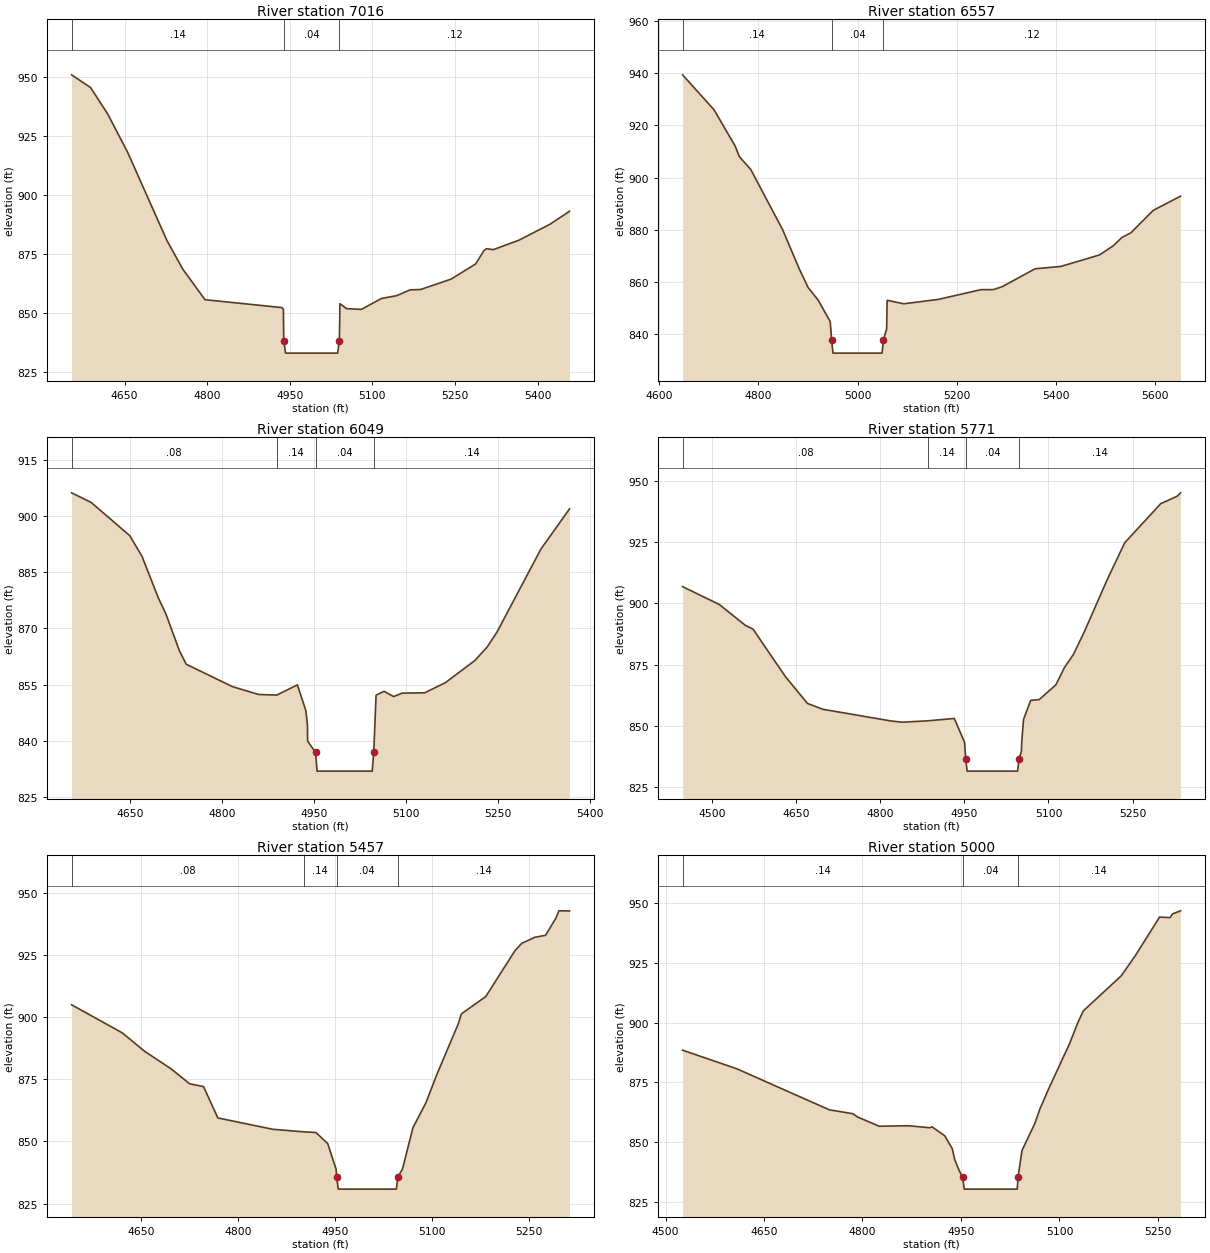
Type RM Length L Ch R = 1,7016,459,459,459
BEGIN DESCRIPTION:
Fisher River 14.0
END DESCRIPTION:
XS GIS Cut Line= 3
      1499217.21       923119.72      1498982.35       923232.04
      1498339.22       923266.75
#Sta/Elev= 30
  4553.6  950.86  4588.1  945.47  4619.2  934.27  4655.4  918.03  4726.8  880.60
  4755.6  868.45  4796.0  855.47  4935.9  852.12  4938.4  851.35  4938.9  840.81
  4939.2  837.81  4942.3  832.81  5036.8  832.81  5040.0  837.81  5040.7  847.91
  5041.0  853.77  5053.4  851.66  5080.0  851.37  5116.5  856.00  5143.8  857.17
  5168.9  859.66  5187.3  859.78  5242.9  864.19  5287.6  870.65  5302.6  876.31
  5307.1  877.10  5319.7  876.72  5365.9  880.68  5423.3  887.57  5458.0  892.99
#Mann=3,-1,0
  4553.6    0.14       0  4939.2    0.04       0  5040.0    0.12       0
Bank Sta=4939.2,5040
XS Rating Curve= 0
Exp/Cntr=0.3,0.1

Type RM Length L Ch R = 1,6557,508,508,508
BEGIN DESCRIPTION:
Fisher River 13.0
END DESCRIPTION:
XS GIS Cut Line= 4
      1499086.47       922914.52      1498882.30       922781.82
      1498669.95       922787.94      1498279.96       923173.86
#Sta/Elev= 30
  4647.1  939.36  4710.4  925.99  4752.9  912.19  4761.8  907.99  4784.6  903.13
  4848.9  880.07  4882.6  865.02  4900.3  857.94  4920.8  853.05  4944.9  844.89
  4947.8  837.80  4950.5  832.80  5049.5  832.80  5052.3  837.80  5058.8  842.14
  5059.7  852.50  5060.1  853.02  5093.3  851.69  5162.9  853.37  5249.0  857.10
  5273.9  857.12  5291.7  858.21  5358.2  865.09  5410.4  866.00  5488.1  870.39
  5515.8  873.87  5533.7  877.12  5551.5  878.85  5596.6  887.46  5651.7  892.90
#Mann=3,-1,0
  4647.1    0.14       0  4947.8    0.04       0  5052.3    0.12       0
Bank Sta=4947.8,5052.3
XS Rating Curve= 0
Exp/Cntr=0.3,0.1

Type RM Length L Ch R = 1,6049,278,278,278
BEGIN DESCRIPTION:
Fisher River 12.0
END DESCRIPTION:
XS GIS Cut Line= 4
      1499131.40       922466.35      1498855.76       922288.71
      1498582.15       922266.25      1498394.27       922172.31
#Sta/Elev= 30
  4554.4  906.13  4586.4  903.57  4649.3  894.72  4669.3  889.22  4695.9  878.16
  4708.5  873.79  4730.5  863.98  4741.5  860.43  4816.8  854.47  4859.5  852.37
  4889.3  852.20  4922.9  854.93  4936.8  848.01  4939.4  844.07  4939.6  839.93
  4952.5  836.93  4955.0  831.93  5045.0  831.93  5047.5  836.93  5051.3  852.18
  5064.3  853.21  5079.9  851.81  5093.9  852.73  5130.6  852.81  5164.5  855.53
  5212.5  861.42  5232.5  865.00  5248.8  869.06  5320.3  891.14  5366.9  901.83
#Mann=4,-1,0
  4554.4    0.08       0  4889.3    0.14       0  4952.5    0.04       0
  5047.5    0.14       0
Bank Sta=4952.5,5047.5
XS Rating Curve= 0
Exp/Cntr=0.3,0.1

Type RM Length L Ch R = 1,5771,314,314,314
BEGIN DESCRIPTION:
Fisher River 11.5
END DESCRIPTION:
XS GIS Cut Line= 4
      1499151.83       922464.32      1498759.79       921964.06
      1498819.01       921817.05      1498898.67       921768.03
#Sta/Elev= 30
  4447.8  906.91  4513.4  899.56  4560.1  890.97  4573.2  889.56  4630.8  870.15
  4670.3  859.08  4698.1  856.67  4819.5  851.89  4839.6  851.39  4885.6  851.97
  4932.1  852.93  4950.5  843.11  4952.5  836.36  4955.0  831.36  5045.0  831.36
  5047.5  836.36  5051.7  839.44  5052.5  843.78  5055.6  852.53  5068.3  860.34
  5083.4  860.63  5113.2  866.69  5128.5  873.77  5144.3  879.06  5164.1  888.50
  5205.1  909.97  5236.0  924.89  5300.2  940.88  5329.6  943.94  5335.4  945.31
#Mann=4,-1,0
  4447.8    0.08       0  4885.6    0.14       0  4952.5    0.04       0
  5047.5    0.14       0
Bank Sta=4952.5,5047.5
XS Rating Curve= 0
Exp/Cntr=0.3,0.1

Type RM Length L Ch R = 1,5457,457,457,457
BEGIN DESCRIPTION:
Fisher River 11.0
END DESCRIPTION:
XS GIS Cut Line= 4
      1499162.04       922450.01      1499121.20       922070.24
      1499121.20       921923.22      1499317.24       921780.28
#Sta/Elev= 30
  4541.7  904.99  4620.3  893.68  4655.0  886.25  4695.7  879.25  4724.6  873.21
  4746.2  872.05  4768.4  859.45  4853.3  854.89  4901.5  853.85  4920.2  853.61
  4938.7  849.10  4951.6  838.83  4952.5  835.80  4955.0  830.80  5045.0  830.80
  5047.5  835.80  5054.4  838.80  5070.7  855.49  5091.0  865.63  5107.5  876.73
  5141.1  897.40  5145.7  901.31  5183.6  908.30  5228.9  926.78  5239.3  929.71
  5259.8  932.15  5276.2  932.93  5292.6  940.02  5296.8  942.79  5313.3  942.74
#Mann=4,-1,0
  4541.7    0.08       0  4901.5    0.14       0  4952.5    0.04       0
  5047.5    0.14       0
Bank Sta=4952.5,5047.5
XS Rating Curve= 0
Exp/Cntr=0.3,0.1

Type RM Length L Ch R = 1,5000,237,237,237
BEGIN DESCRIPTION:
Fisher River 10.0
END DESCRIPTION:
XS GIS Cut Line= 3
      1499496.90       922515.34      1499586.74       921910.97
      1499468.34       921823.19
#Sta/Elev= 30
  4526.0  888.50  4609.1  880.67  4749.5  863.58  4785.3  861.96  4792.7  860.55
  4825.5  856.72  4870.3  856.93  4902.2  856.09  4906.0  856.45  4925.4  852.71
  4936.8  847.29  4940.4  842.83  4947.7  837.94  4952.5  835.44  4955.0  830.44
  5035.7  830.44  5037.0  835.44  5042.9  846.57  5062.5  857.86  5070.3  863.98
  5083.5  872.32  5115.6  891.33  5127.9  899.96  5136.4  904.94  5194.1  919.56
  5215.8  928.10  5252.5  944.11  5268.5  943.91  5272.3  945.46  5284.4  946.73
#Mann=3,-1,0
  4526.0    0.14       0  4952.5    0.04       0  5037.0    0.14       0
Bank Sta=4952.5,5037
XS Rating Curve= 0
Exp/Cntr=0.3,0.1

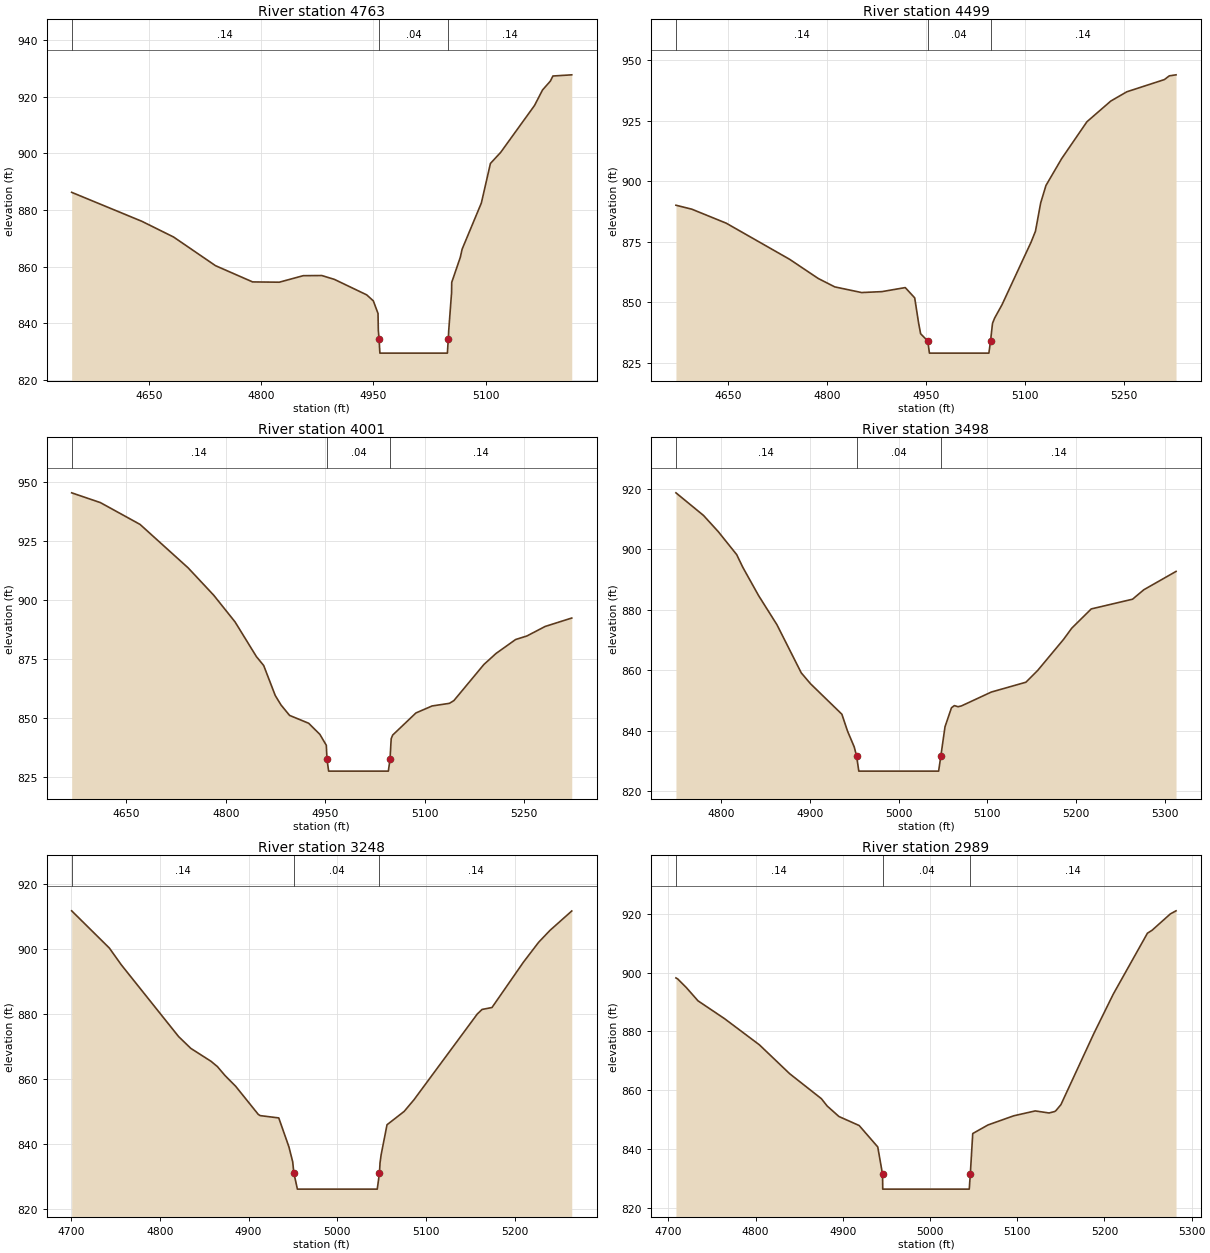
Type RM Length L Ch R = 1,4763,264,264,264
BEGIN DESCRIPTION:
Fisher River 9.5
END DESCRIPTION:
XS GIS Cut Line= 4
      1499532.79       922496.22      1499691.93       922243.57
      1499882.22       922008.99      1499908.47       921946.64
#Sta/Elev= 30
  4546.9  886.25  4640.8  876.02  4683.1  870.49  4739.1  860.38  4788.7  854.65
  4824.3  854.55  4856.4  856.85  4881.2  856.90  4898.1  855.53  4941.2  850.08
  4950.0  847.97  4956.3  843.52  4956.7  837.58  4957.7  834.53  4958.8  829.53
  5049.0  829.53  5050.2  834.53  5050.8  837.53  5054.6  850.94  5054.8  854.49
  5066.3  863.37  5068.7  866.21  5094.4  882.49  5106.5  896.43  5120.2  900.34
  5165.4  916.87  5176.2  922.38  5186.6  925.48  5190.0  927.28  5215.2  927.70
#Mann=3,-1,0
  4546.9    0.14       0  4957.7    0.04       0  5050.2    0.14       0
Bank Sta=4957.7,5050.2
XS Rating Curve= 0
Exp/Cntr=0.3,0.1

Type RM Length L Ch R = 1,4499,498,498,498
BEGIN DESCRIPTION:
Fisher River 9.0
END DESCRIPTION:
XS GIS Cut Line= 4
      1499533.67       922541.89      1499780.71       922325.47
      1499929.77       922345.89      1500205.45       922382.64
#Sta/Elev= 30
  4571.3  890.15  4595.3  888.52  4647.5  882.72  4743.4  867.80  4786.6  859.90
  4811.7  856.41  4852.3  854.07  4883.0  854.45  4918.4  856.12  4932.7  851.88
  4938.6  841.50  4941.7  837.04  4952.5  834.04  4955.0  829.04  5045.0  829.04
  5047.5  834.04  5050.5  841.36  5053.7  843.52  5064.8  849.00  5109.0  874.97
  5115.5  879.40  5123.4  891.10  5131.4  898.31  5155.1  909.38  5193.4  924.64
  5229.6  933.21  5253.9  937.03  5310.7  942.07  5318.1  943.61  5328.3  944.03
#Mann=3,-1,0
  4571.3    0.14       0  4952.5    0.04       0  5047.5    0.14       0
Bank Sta=4952.5,5047.5
XS Rating Curve= 0
Exp/Cntr=0.3,0.1

Type RM Length L Ch R = 1,4001,503,503,503
BEGIN DESCRIPTION:
Fisher River 8.0
END DESCRIPTION:
XS GIS Cut Line= 3
      1499725.57       923108.55      1499792.96       922869.62
      1500274.86       922716.47
#Sta/Elev= 30
  4567.6  945.48  4610.9  941.34  4670.6  932.12  4743.1  913.71  4781.7  902.12
  4813.9  890.80  4846.1  876.10  4857.1  872.31  4874.5  859.62  4883.2  855.61
  4896.1  851.19  4924.9  847.86  4941.8  843.14  4951.5  838.52  4952.5  832.58
  4955.0  827.58  5045.0  827.58  5047.5  832.58  5049.3  841.32  5051.5  842.84
  5086.6  852.23  5111.0  855.19  5137.1  856.30  5143.8  857.46  5189.0  872.74
  5207.4  877.44  5236.9  883.34  5253.9  884.84  5281.4  888.87  5321.5  892.44
#Mann=3,-1,0
  4567.6    0.14       0  4952.5    0.04       0  5047.5    0.14       0
Bank Sta=4952.5,5047.5
XS Rating Curve= 0
Exp/Cntr=0.3,0.1

Type RM Length L Ch R = 1,3498,250,250,250
BEGIN DESCRIPTION:
Fisher River 7.0
END DESCRIPTION:
XS GIS Cut Line= 3
      1500362.65       923288.23      1500276.88       922943.12
      1500374.90       922759.34
#Sta/Elev= 30
  4748.8  918.70  4779.8  911.24  4796.5  905.87  4817.3  898.26  4824.2  894.06
  4842.0  884.70  4862.7  875.06  4890.1  859.14  4900.5  855.55  4935.9  845.46
  4942.3  839.86  4949.8  834.66  4952.5  831.63  4955.0  826.63  5045.0  826.63
  5047.5  831.63  5052.2  841.30  5059.5  847.61  5062.8  848.31  5066.9  847.94
  5070.7  848.20  5104.4  852.79  5143.4  856.04  5156.7  859.94  5186.0  870.26
  5195.1  873.92  5217.1  880.29  5263.7  883.51  5276.3  886.62  5312.7  892.70
#Mann=3,-1,0
  4748.8    0.14       0  4952.5    0.04       0  5047.5    0.14       0
Bank Sta=4952.5,5047.5
XS Rating Curve= 0
Exp/Cntr=0.3,0.1

Type RM Length L Ch R = 1,3248,259,259,259
BEGIN DESCRIPTION:
Fisher River 6.5
END DESCRIPTION:
XS GIS Cut Line= 4
      1500484.59       923256.66      1500585.15       923135.99
      1500504.70       922845.25      1500515.67       922740.97
#Sta/Elev= 30
  4700.6  911.86  4743.1  900.40  4756.4  895.29  4821.1  873.17  4834.9  869.53
  4857.7  865.55  4864.8  863.94  4873.3  861.21  4885.5  857.85  4910.9  849.22
  4913.1  848.84  4934.0  848.13  4945.5  839.18  4949.7  834.62  4951.0  831.22
  4955.0  826.22  5045.0  826.22  5047.5  831.22  5048.1  834.25  5049.4  836.84
  5056.0  846.03  5075.3  850.13  5086.4  853.73  5157.7  880.10  5163.1  881.51
  5174.3  882.11  5209.7  896.05  5226.8  902.16  5239.6  905.83  5264.2  911.81
#Mann=3,-1,0
  4700.6    0.14       0  4951.0    0.04       0  5047.5    0.14       0
Bank Sta=4951,5047.5
XS Rating Curve= 0
Exp/Cntr=0.3,0.1

Type RM Length L Ch R = 1,2989,285,285,285
BEGIN DESCRIPTION:
Fisher River 6.0
END DESCRIPTION:
XS GIS Cut Line= 3
      1500940.49       923200.42      1500824.09       923022.76
      1500717.93       922677.72
#Sta/Elev= 30
  4708.7  898.17  4710.9  897.77  4720.6  894.89  4734.0  890.38  4764.5  884.30
  4804.4  875.42  4839.1  865.60  4875.5  857.10  4882.1  854.62  4895.6  851.05
  4918.8  847.98  4940.1  840.70  4945.6  831.36  4945.8  826.36  5045.0  826.36
  5046.2  831.36  5049.0  845.26  5066.5  848.18  5096.0  851.29  5120.6  852.95
  5136.5  852.25  5142.8  852.73  5144.2  852.99  5150.1  855.08  5187.8  879.22
  5210.1  892.64  5249.3  913.37  5254.6  914.37  5275.6  919.93  5282.1  920.98
#Mann=3,-1,0
  4708.7    0.14       0  4945.6    0.04       0  5046.2    0.14       0
Bank Sta=4945.6,5046.2
XS Rating Curve= 0
Exp/Cntr=0.3,0.1

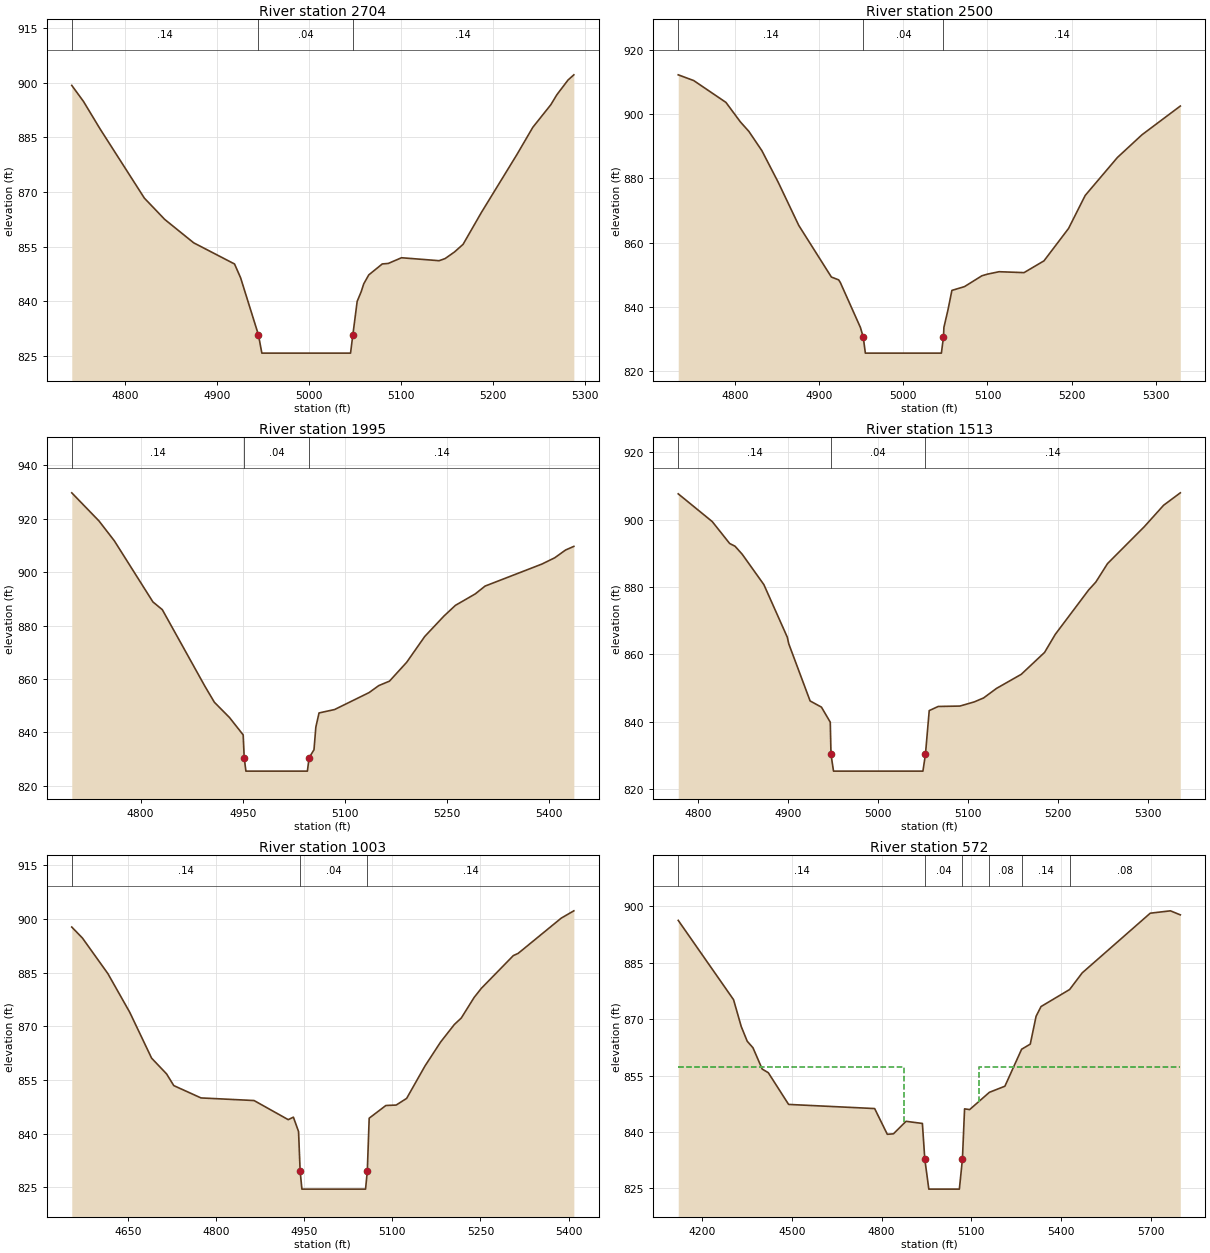
Type RM Length L Ch R = 1,2704,204,204,204
BEGIN DESCRIPTION:
Fisher River 5.5
END DESCRIPTION:
XS GIS Cut Line= 3
      1501228.77       923000.64      1500905.15       922660.56
      1500839.28       922622.14
#Sta/Elev= 30
  4742.2  899.24  4754.9  894.85  4773.1  887.24  4821.1  868.30  4843.2  862.46
  4874.7  856.03  4919.1  850.22  4925.7  846.44  4945.1  830.75  4948.8  825.75
  5045.2  825.75  5047.7  830.75  5052.4  839.95  5056.8  842.63  5059.5  844.74
  5065.0  847.22  5079.7  850.23  5086.2  850.37  5100.6  851.93  5141.5  851.12
  5148.0  851.71  5158.2  853.52  5167.5  855.61  5187.4  864.35  5226.1  880.29
  5243.3  887.73  5262.9  893.94  5269.4  896.66  5281.6  900.72  5287.9  902.14
#Mann=3,-1,0
  4742.2    0.14       0  4945.1    0.04       0  5047.7    0.14       0
Bank Sta=4945.1,5047.7
XS Rating Curve= 0
Exp/Cntr=0.3,0.1

Type RM Length L Ch R = 1,2500,505,505,505
BEGIN DESCRIPTION:
Fisher River 5.0
END DESCRIPTION:
XS GIS Cut Line= 4
      1501404.00       922565.37      1501248.80       922679.73
      1501069.11       922628.68      1500858.80       922573.55
#Sta/Elev= 30
  4732.3  912.24  4750.7  910.46  4789.0  903.67  4806.2  897.60  4816.2  894.68
  4831.7  888.68  4851.1  878.87  4875.6  865.41  4914.4  849.35  4923.1  848.46
  4925.1  847.61  4948.9  833.68  4952.3  830.68  4954.8  825.68  5045.2  825.68
  5047.7  830.68  5048.2  833.68  5053.1  839.21  5057.7  845.19  5072.7  846.37
  5093.4  849.74  5099.9  850.24  5113.8  851.00  5143.5  850.72  5167.2  854.38
  5196.4  864.45  5216.2  874.72  5254.5  886.53  5283.7  893.59  5329.3  902.53
#Mann=3,-1,0
  4732.3    0.14       0  4952.3    0.04       0  5047.7    0.14       0
Bank Sta=4952.3,5047.7
XS Rating Curve= 0
Exp/Cntr=0.3,0.1

Type RM Length L Ch R = 1,1995,482,482,482
BEGIN DESCRIPTION:
Fisher River 4.0
END DESCRIPTION:
XS GIS Cut Line= 4
      1501481.53       922161.10      1501291.68       922159.06
      1501030.32       922150.89      1500797.53       922318.33
#Sta/Elev= 30
  4698.8  929.71  4738.8  919.18  4761.4  911.73  4818.1  888.85  4831.9  885.95
  4894.6  857.23  4908.5  851.25  4930.7  845.54  4950.8  839.04  4952.3  830.47
  4954.8  825.47  5045.2  825.47  5047.7  830.47  5054.9  833.48  5057.6  841.94
  5062.3  847.26  5085.2  848.54  5135.9  854.89  5150.1  857.50  5165.9  859.18
  5191.2  866.25  5217.7  875.90  5245.9  883.54  5262.8  887.56  5291.9  891.84
  5306.4  894.78  5389.9  903.02  5408.9  905.39  5424.6  908.27  5436.9  909.65
#Mann=3,-1,0
  4698.8    0.14       0  4952.3    0.04       0  5047.7    0.14       0
Bank Sta=4952.3,5047.7
XS Rating Curve= 0
Exp/Cntr=0.3,0.1

Type RM Length L Ch R = 1,1513,510,510,510
BEGIN DESCRIPTION:
Fisher River 3.0
END DESCRIPTION:
XS GIS Cut Line= 4
      1501326.39       921646.55      1501146.87       921672.20
      1501022.15       921730.27      1500817.96       921854.83
#Sta/Elev= 30
  4777.7  907.66  4815.5  899.42  4834.9  892.90  4840.8  892.11  4848.8  889.72
  4872.9  880.69  4899.0  865.03  4900.5  863.15  4924.3  846.13  4936.9  844.29
  4946.7  839.82  4947.5  830.28  4950.3  825.28  5049.7  825.28  5052.5  830.28
  5056.7  843.26  5066.7  844.49  5090.8  844.61  5106.8  845.85  5117.2  847.03
  5131.5  849.86  5159.0  854.04  5184.9  860.54  5196.8  865.91  5233.9  879.10
  5241.9  881.45  5254.9  886.94  5295.7  897.88  5317.2  904.26  5335.8  907.96
#Mann=3,-1,0
  4777.7    0.14       0  4947.5    0.04       0  5052.5    0.14       0
Bank Sta=4947.5,5052.5
XS Rating Curve= 0
Exp/Cntr=0.3,0.1

Type RM Length L Ch R = 1,1003,431,431,431
BEGIN DESCRIPTION:
Fisher River 2.0
END DESCRIPTION:
XS GIS Cut Line= 4
      1501322.30       921385.20      1501095.89       921199.50
      1500791.42       921221.85      1500579.09       921366.81
#Sta/Elev= 30
  4553.8  897.74  4572.0  894.66  4615.3  884.73  4652.5  873.94  4689.8  861.11
  4715.3  856.71  4727.6  853.44  4773.9  850.00  4864.3  849.27  4922.5  843.93
  4931.3  844.62  4940.1  840.61  4942.8  829.52  4945.8  824.52  5054.2  824.52
  5057.2  829.52  5060.4  844.34  5088.8  847.88  5106.4  848.01  5124.2  849.87
  5155.5  858.94  5182.2  865.65  5205.5  870.52  5217.2  872.31  5239.1  878.06
  5251.4  880.61  5305.9  889.76  5314.2  890.39  5387.6  900.24  5409.0  902.27
#Mann=3,-1,0
  4553.8    0.14       0  4942.8    0.04       0  5057.2    0.14       0
Bank Sta=4942.8,5057.2
XS Rating Curve= 0
Exp/Cntr=0.5,0.3

Type RM Length L Ch R = 1,572,151,151,151
BEGIN DESCRIPTION:
Railroad - US
END DESCRIPTION:
XS GIS Cut Line= 6
      1501330.47       921370.91      1501349.55       920990.69
      1500869.97       920771.20      1500677.91       920688.15
      1500501.42       920615.48      1500382.03       920965.85
#Sta/Elev= 30
  4120.3  896.25  4305.2  875.17  4331.0  868.01  4351.0  864.11  4370.1  862.39
  4401.0  856.72  4421.4  855.75  4489.3  847.32  4776.9  846.22  4819.2  839.38
  4839.7  839.50  4881.8  842.83  4936.5  842.26  4944.6  832.74  4958.0  824.80
  5060.1  824.80  5070.3  832.74  5077.5  846.14  5094.5  845.95  5160.5  850.54
  5212.3  852.16  5268.2  861.99  5297.1  863.35  5316.6  870.76  5333.1  873.34
  5428.7  877.87  5470.7  882.29  5698.2  898.16  5765.6  898.79  5798.7  897.72
#Mann=6,-1,0
  4120.3    0.14       0  4944.6    0.04       0  5070.3    0.14       0
  5160.5    0.08       0  5268.2    0.14       0  5428.7    0.08       0
#XS Ineff=2,0
    0.00 4875.00  857.20 5125.00    0.00  857.20
Permanent Ineff=
       F       F
Bank Sta=4944.6,5070.3
XS Rating Curve= 0
Exp/Cntr=0.5,0.3

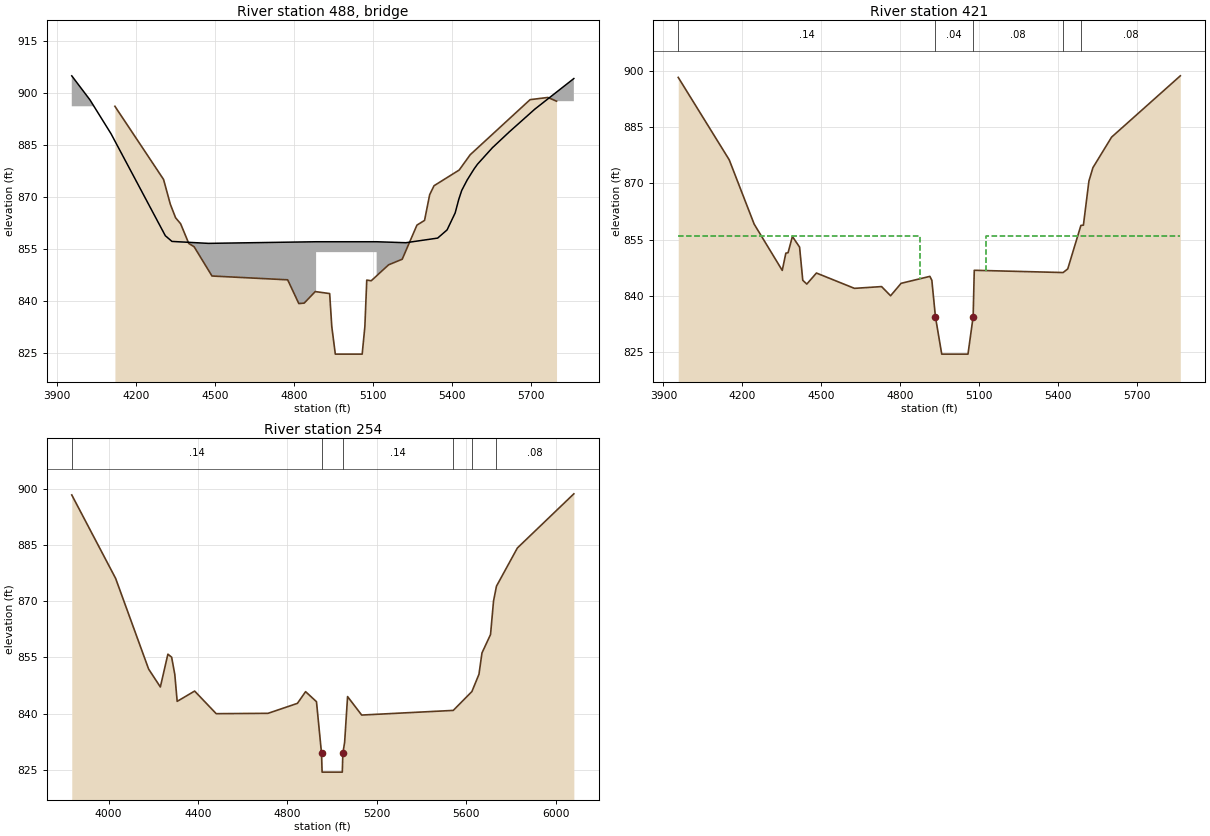
Type RM Length L Ch R =3,488,,,
BEGIN DESCRIPTION:
Railroad - TOR
Structure ID: LDS_FR_01
Approximate Survey Structure
END DESCRIPTION:
Bridge Culvert--1,0,-1,-1,0
Deck Dist Width WeirC Skew NumUp NumDn MinLoCord MaxHiCord MaxSubmerge Is_Ogee
72.5,23,3,,23,23,,,0.95,0,1,1,,,
  3956.4  4025.5  4105.7  4311.9  4337.1  4475.8  4885.0  4885.0  5115.0  5115.0
  5226.0  5346.9  5382.7  5413.5  5427.1  5438.6  5459.1  5484.8  5498.4  5554.7
  5618.8  5716.4  5864.5
  905.03  898.10  888.32  858.94  857.29  856.73  857.20  857.20  857.20  857.20
  856.92  858.25  860.61  865.51  869.40  872.03  875.00  878.12  879.56  884.28
  888.84  895.44  904.25
  804.80  804.80  804.80  804.80  804.80  804.80  804.80  854.20  854.20  804.80
  804.80  804.80  804.80  804.80  804.80  804.80  804.80  804.80  804.80  804.80
  804.80  804.80  804.80
  3956.4  4025.5  4105.7  4311.9  4337.1  4475.8  4885.0  4885.0  5115.0  5115.0
  5226.0  5346.9  5382.7  5413.5  5427.1  5438.6  5459.1  5484.8  5498.4  5554.7
  5618.8  5716.4  5864.5
  905.03  898.10  888.32  858.94  857.29  856.73  857.20  857.20  857.20  857.20
  856.92  858.25  860.61  865.51  869.40  872.03  875.00  878.12  879.56  884.28
  888.84  895.44  904.25
  804.80  804.80  804.80  804.80  804.80  804.80  804.80  854.20  854.20  804.80
  804.80  804.80  804.80  804.80  804.80  804.80  804.80  804.80  804.80  804.80
  804.80  804.80  804.80
Abutment Skew #Up #Dn=,2,2
  4885.0  4910.0
  854.20  842.87
  4885.0  4910.0
  854.20  845.17
Abutment Skew #Up #Dn=,2,2
  5090.0  5115.0
  845.79  854.20
  5090.0  5115.0
  846.51  854.20
BR Coef=1,1,0,1.25,0,,,0.8,0,2,0,
WSPro=,,,, 1 ,,,, 0 ,,,, 0 ,,,,-1 ,-1 ,-1 , 0 , 0 , 0 , 0 , 0
BC Design=,,0,,0,,,,,,

Type RM Length L Ch R = 1,421,167,167,167
BEGIN DESCRIPTION:
Railroad - DS
END DESCRIPTION:
XS GIS Cut Line= 4
      1501352.45       921368.50      1501382.39       920835.12
      1500521.69       920466.70      1500397.11       920887.17
#Sta/Elev= 30
  3956.1  898.22  4149.9  876.29  4244.8  859.16  4351.6  846.84  4365.2  851.42
  4373.7  851.55  4390.2  855.87  4417.5  853.04  4429.6  844.21  4445.0  843.20
  4481.6  846.14  4626.1  842.06  4729.3  842.53  4763.5  840.09  4803.5  843.40
  4912.9  845.25  4920.4  844.20  4934.0  834.49  4958.0  824.55  5057.8  824.55
  5077.4  834.49  5081.7  846.87  5419.5  846.27  5437.1  847.24  5487.1  858.81
  5496.7  858.89  5517.6  870.62  5532.8  874.19  5603.8  882.32  5865.1  898.64
#Mann=5,-1,0
  3956.1    0.14       0  4934.0    0.04       0  5077.4    0.08       0
  5419.5    0.14       0  5487.1    0.08       0
#XS Ineff=2,0
    0.00 4875.00  856.00 5125.00    0.00  856.00
Permanent Ineff=
       F       F
Bank Sta=4934,5077.4
XS Rating Curve= 0
Exp/Cntr=0.5,0.3

Type RM Length L Ch R = 1,254,0,0,0
BEGIN DESCRIPTION:
Fisher River 1.0
END DESCRIPTION:
XS GIS Cut Line= 4
      1501354.77       921367.41      1501403.77       920632.37
      1500526.88       920329.14      1500381.53       920892.38
#Sta/Elev= 30
  3834.9  898.32  4031.1  876.07  4178.8  851.88  4231.2  847.11  4264.9  855.86
  4281.7  855.05  4295.8  850.47  4306.5  843.27  4384.6  846.02  4481.1  839.99
  4712.9  840.08  4844.4  842.74  4881.0  845.86  4929.7  843.19  4952.3  829.40
  4954.8  824.40  5045.2  824.40  5047.7  829.40  5055.7  832.40  5068.8  844.55
  5131.9  839.62  5541.6  840.86  5625.0  845.89  5656.7  850.51  5670.0  856.17
  5708.4  861.10  5721.8  870.03  5734.9  873.99  5828.5  884.18  6081.1  898.62
#Mann=6,-1,0
  3834.9    0.14       0  4952.3    0.04       0  5047.7    0.14       0
  5541.6    0.08       0  5625.0    0.14       0  5734.9    0.08       0
Bank Sta=4952.3,5047.7
XS Rating Curve= 0
Exp/Cntr=0.3,0.1

Chan Stop Cuts=-1