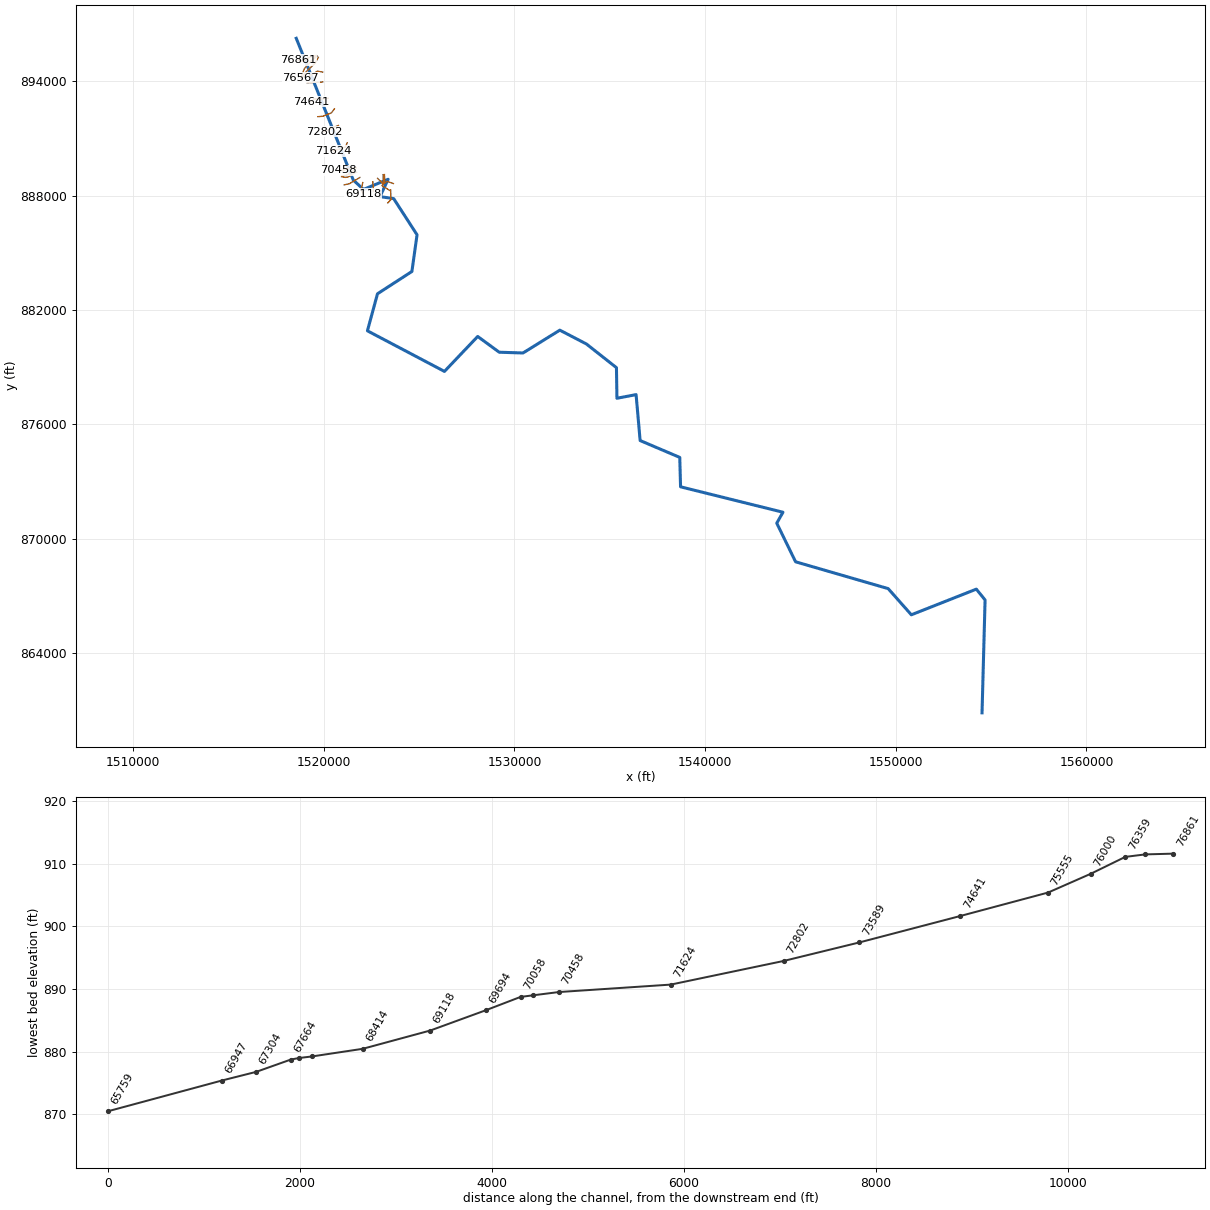
--- Forbush Creek.prj (project) ---

Proj Title=Forbush Creek Limited Detail Study
Current Plan=p01
Default Exp/Contr=0.3,0.1
English Units
Geom File=g01
Flow File=f01
Plan File=p01
Y Axis Title=Elevation
X Axis Title(PF)=Main Channel Distance
X Axis Title(XS)=Station
BEGIN DESCRIPTION:
Forbush Creek
END DESCRIPTION:
DSS Export Rating Curves= 0
DSS Export Rating Curve Sorted= 0
DSS Export Volume Flow Curves= 0
DXF OffsetX= 0
DXF OffsetY= 0
DXF ScaleX= 1
DXF ScaleY= 10

--- Forbush Creek.p01 (plan) ---

Plan Title=Floodway Run
Program Version=3.12
Short Identifier=Floodway
Geom File=g01
Flow File=f01
Subcritical Flow
K Sum by GR= 0
Std Step Tol= 0.01
Critical Tol= 0.01
Num of Std Step Trials= 20
Max Error Tol= 0.3
Flow Tol Ratio= 0.001
Split Flow NTrial= 30
Split Flow Tol= 0.02
Split Flow Ratio= 0.02
Log Output Level= 0
Friction Slope Method= 1
Unsteady Friction Slope Method= 2
Unsteady Bridges Friction Slope Method= 1
Parabolic Critical Depth
Global Vel Dist= 0 , 0 , 0
Global Log Level= 0
CheckData=True
Encroach Param=-1 ,10,10, 2
Encroach River=Forbush Creek
Encroach Reach=Reach-1
Encroach Node=76861
       1    4820    5011
Encroach Node=76567
       1    4928    5060
Encroach Node=76359
       1    4935    5060
Encroach Node=76000
       1    4934    5030
Encroach Node=75555
       1    4913    5063
Encroach Node=74641
       1    4860    5015
Encroach Node=73589
       1    4895    5017
Encroach Node=72802
       1    4960    5100
Encroach Node=71624
       1    4868    5045
Encroach Node=70458
       1    4964    5074
Encroach Node=70184
       1    4950    5130
Encroach Node=70058
       1    4965    5130
Encroach Node=69694
       1    4970    5104
Encroach Node=69118
       1    4968    5040
Encroach Node=68414
       1    4966    5022
Encroach Node=67885
       1    4985    5030
Encroach Node=67749
       1    4960    5030
Encroach Node=67664
       1    4975    5030
Encroach Node=67304
       1    4949    5045
Encroach Node=66947
       1    4973    5038
Encroach Node=65759
       1    4899    5017
Encroach Node=65006
       1    4955    5080
Encroach Node=63907
       1    4910    5007
Encroach Node=63328
       1    4970    5027
Encroach Node=62662
       1    4980    5018
Encroach Node=61870
       1    4960    5018
Encroach Node=60937
       1    4974    5015
Encroach Node=60146
       1    4970    5028
Encroach Node=59666
       1    4978    5078
Encroach Node=58433
       1    4790    5016
Encroach Node=57072
       1    4888    5029
Encroach Node=56156
       1    4800    5064
Encroach Node=55830
       1    4880    5100
Encroach Node=55635
       1    4900    5086
Encroach Node=55049
       1    4925    5120
Encroach Node=54088
       1    4940    5150
Encroach Node=52821
       1    4780    5030
Encroach Node=51370
       1    4780    5030
Encroach Node=50066
       1    4874    5110
Encroach Node=49241
       1    4983    5154
Encroach Node=48638
       1    4920    5040
Encroach Node=48243
       1    4810    5025
Encroach Node=47414
       1    4840    5035
Encroach Node=46494
       1    4875    5040
Encroach Node=45609
       1    4902    5072
Encroach Node=45322
       1    4908    5075
Encroach Node=45165
       1    4908    5125
Encroach Node=44759
       1    4844    5022
Encroach Node=44279
       1    4942    5060
Encroach Node=43540
       1    4960    5030
Encroach Node=42902
       1    4950    5124
Encroach Node=42360
       1    4981    5070
Encroach Node=41368
       1    4870    5025
Encroach Node=40679
       1    4892    5020
Encroach Node=40445
       1    4855    5084
Encroach Node=40280
       1    4841    5081
Encroach Node=40006
       1    4840    5040
Encroach Node=39135
       1    4780    5100
Encroach Node=38320
       1    4900    5140
Encroach Node=37748
       1    4942    5067
Encroach Node=37560
       1    4943    5045
Encroach Node=37414
       1    4943    5045
Encroach Node=37119
       1    4964    5120
Encroach Node=36236
       1    4911    5060
Encroach Node=35964
       1    4920    5110
Encroach Node=35849
       1    4942    5120
Encroach Node=35315
       1    4910    5190
Encroach Node=34461
       1    4922    5176
Encroach Node=33705
       1    4760    5100
Encroach Node=32450
       1    4880    5250
Encroach Node=31427
       1    4830    5030
Encroach Node=30468
       1    4740    5044
Encroach Node=29458
       1    4780    5204
Encroach Node=28343
       1    4960    5188
Encroach Node=27395
       1    4822    5024
Encroach Node=26751
       1    4960    5080
Encroach Node=25863
       1    4970    5055
Encroach Node=24860
       1    4947    5022
Encroach Node=24210
       1    4900    5045
Encroach Node=23879
       1    4940    5058
Encroach Node=23755
       1  4898.5  5101.5
Encroach Node=23206
       1    4640    5050
Encroach Node=22043
       1    4930    5125
Encroach Node=21260
       1    4915    5018
Encroach Node=20462
       1    4930    5040
Encroach Node=19679
       1    4948    5140
Encroach Node=18940
       1  4965.6    5358
Encroach Node=17167
       1    4683    5022
Encroach Node=15453
       1    4520    5033
Encroach Node=13527
       1    4770    5050
Encroach Node=12665
       1    4652    5169
Encroach Node=11033
       1    4460    5030
Encroach Node=9393
       1    4730    5058
Encroach Node=7615
       1    4776    5030
Encroach Node=7331
       1    4860    5086
Encroach Node=7063
       1    4870    5130
Encroach Node=6474
       1    4840    5284
Encroach Node=5583
       1    4580    5300
Encroach Node=3684
       1    4640    5230
Encroach Node=3269
       1    4815    5080
Encroach Node=3062
       1    4810    5150
Encroach Node=2543
       1    4940    5490
BEGIN DESCRIPTION:
Floodway Run
END DESCRIPTION:
Computation Interval=1HOUR
Output Interval=1HOUR
Run HTab= 0
Run UNet= 0
Run PostProcess= 0
UNET Theta= 1
UNET Theta Warmup= 1
UNET ZTol= 0.02
UNET ZSATol= 0.05
UNET MxIter= 20
UNET MaxInSteps= 0
UNET DtIC= 0
UNET DtMin= 0
UNET MaxCRTS= 20
UNET WFStab= 2
UNET SFStab= 1
UNET WFX= 1
UNET SFX= 1
UNET DSS MLevel= 4
UNET DZMax Abort= 100
UNET Convert EG Bridges=-1
UNET Use Existing IB Tables=-1
UNET Froude Reduction=False
UNET Froude Limit= 1
UNET Froude Power= 10
Instantaneous Interval=1HOUR
Write IC File= 0
Echo Input=False
Echo Output=False
Write Detailed= 0
Detailed Automatic Start=False, 10

--- Forbush Creek.f01 (steady flow) ---

Flow Title=Floodway
Number of Profiles=2
Profile Names=100-year,100-FW
River Rch & RM= Forbush Creek,Reach-1,76861
    1679    1679
River Rch & RM= Forbush Creek,Reach-1,74641
    1976    1976
River Rch & RM= Forbush Creek,Reach-1,70458
    2056    2056
River Rch & RM= Forbush Creek,Reach-1,67304
    2471    2471
River Rch & RM= Forbush Creek,Reach-1,58433
    2550    2550
River Rch & RM= Forbush Creek,Reach-1,56156
    3061    3061
River Rch & RM= Forbush Creek,Reach-1,52821
    3117    3117
River Rch & RM= Forbush Creek,Reach-1,50066
    3179    3179
River Rch & RM= Forbush Creek,Reach-1,48638
    3183    3183
River Rch & RM= Forbush Creek,Reach-1,48243
    3361    3361
River Rch & RM= Forbush Creek,Reach-1,45322
    3410    3410
River Rch & RM= Forbush Creek,Reach-1,41368
    3510    3510
River Rch & RM= Forbush Creek,Reach-1,39135
    3537    3537
River Rch & RM= Forbush Creek,Reach-1,35315
    3796    3796
River Rch & RM= Forbush Creek,Reach-1,32450
    3817    3817
River Rch & RM= Forbush Creek,Reach-1,27395
    3819    3819
River Rch & RM= Forbush Creek,Reach-1,23206
    4327    4327
River Rch & RM= Forbush Creek,Reach-1,18940
    4517    4517
River Rch & RM= Forbush Creek,Reach-1,15453
    4749    4749
River Rch & RM= Forbush Creek,Reach-1,12665
    4936    4936
River Rch & RM= Forbush Creek,Reach-1,6474
    9002    9002
Boundary for River Rch & Prof#=Forbush Creek,Reach-1,1
Up Type=0
Dn Type=3
Dn Slope=0.001
Boundary for River Rch & Prof#=Forbush Creek,Reach-1,2
Up Type=0
Dn Type=3
Dn Slope=0.001

--- Forbush Creek.g01 (geometry) ---

Geom Title=Existing Conditions

River Reach=Forbush Creek,Reach-1
Reach XY= 30
      1518560.00       896247.88      1521551.27       888814.72
      1522084.75       888324.59      1523376.80       888856.22
      1522950.60       887946.48      1523668.05       887843.26
      1524893.95       885945.92      1524624.64       884021.91
      1522820.57       882853.78      1522292.18       880911.25
      1526331.77       878782.81      1528074.96       880614.73
      1529202.24       879788.98      1530450.77       879748.55
      1532381.45       880945.85      1533775.05       880221.27
      1535351.41       878978.69      1535376.54       877374.79
      1536381.09       877565.70      1536592.88       875158.25
      1538671.22       874274.01      1538712.89       872732.35
      1544083.63       871398.50      1543757.76       870826.38
      1544744.78       868800.37      1549601.40       867393.38
      1550815.25       866021.00      1554224.13       867366.88
      1554682.19       866798.41      1554522.50       860880.25

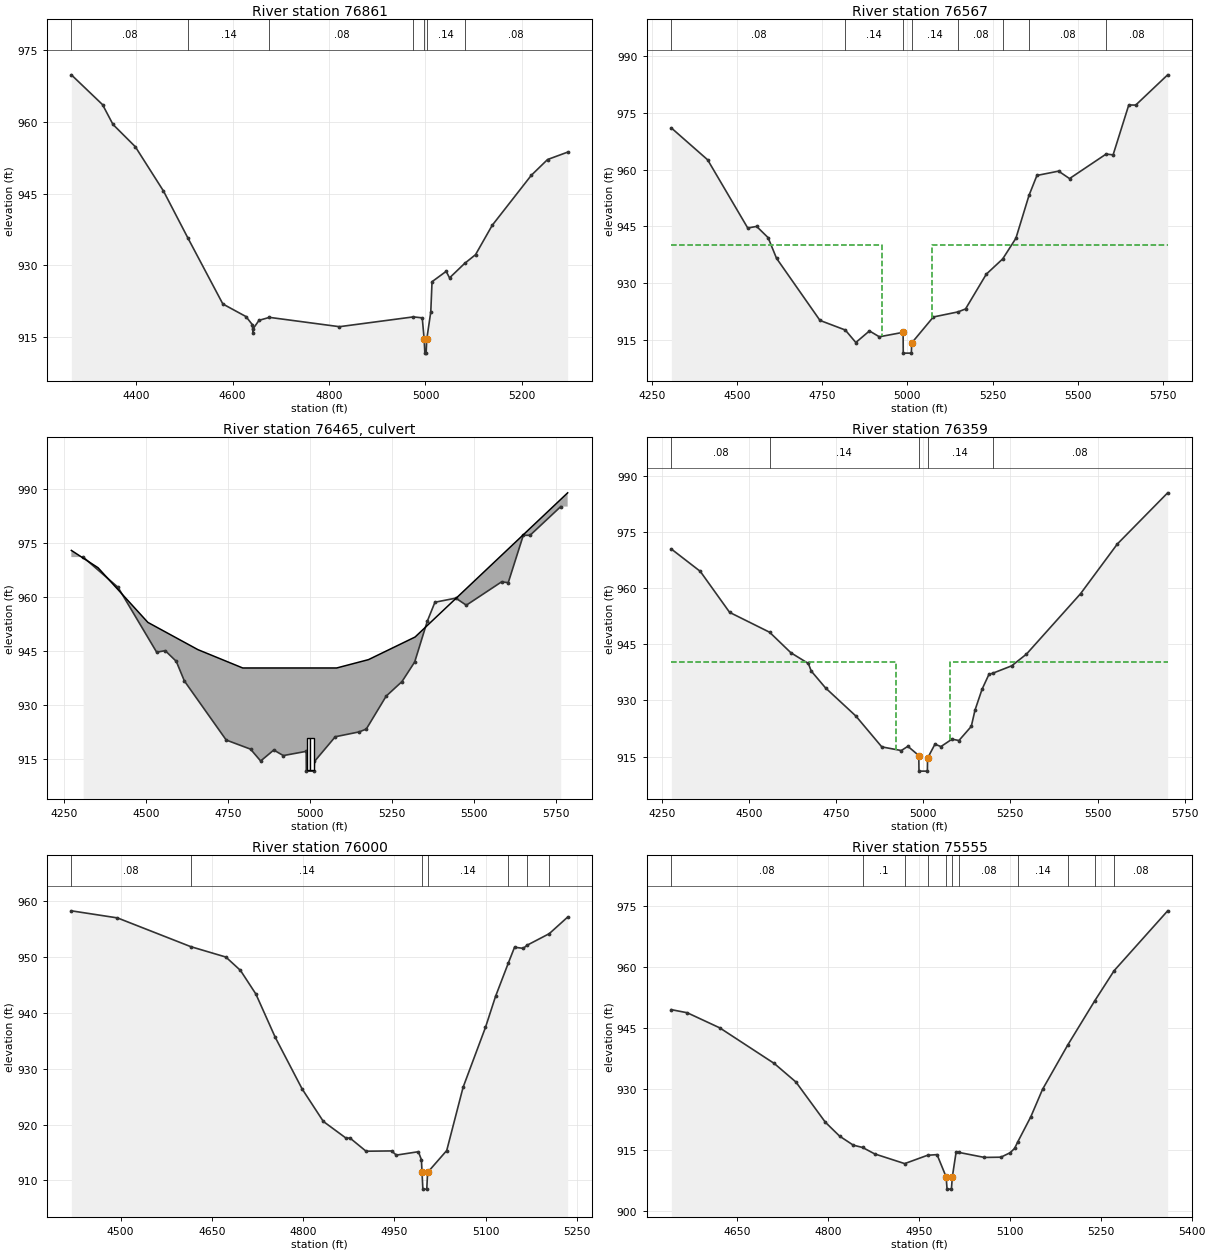
Type RM Length L Ch R = 1,76861,294,294,294
BEGIN DESCRIPTION:
Forbush Creek - 81.0
END DESCRIPTION:
XS GIS Cut Line= 4
      1519613.84       895346.84      1519299.45       895276.26
      1518920.93       895038.89      1518670.71       895109.46
#Sta/Elev= 30
  4265.8  969.84  4330.5  963.60  4352.1  959.46  4398.4  954.80  4456.8  945.53
  4507.6  935.67  4579.9  921.90  4627.8  919.27  4640.9  917.60  4642.5  915.79
  4642.7  916.73  4654.9  918.48  4676.5  919.10  4821.5  917.15  4974.8  919.20
  4993.3  919.00  4997.2  914.62  4998.7  911.62  5001.3  911.62  5002.8  914.62
  5011.0  920.25  5013.6  926.56  5042.9  928.73  5049.9  927.36  5081.0  930.37
  5103.8  932.22  5138.3  938.35  5219.4  948.82  5253.1  952.12  5294.8  953.67
#Mann=7,-1,0
  4265.8    0.08       0  4507.6    0.14       0  4676.5    0.08       0
  4974.8    0.14       0  4997.2    0.05       0  5002.8    0.14       0
  5081.0    0.08       0
Bank Sta=4997.2,5002.8
XS Rating Curve= 0
Exp/Cntr=0.5,0.3

Type RM Length L Ch R = 1,76567,208,208,208
BEGIN DESCRIPTION:
Union Grove Church Road  FC - us
END DESCRIPTION:
XS GIS Cut Line= 4
      1519649.09       895314.75      1519302.66       895022.85
      1518985.09       894657.16      1518799.04       894172.81
#Sta/Elev= 30
  4307.4  971.05  4413.8  962.63  4531.5  944.59  4557.6  945.01  4591.2  942.05
  4616.0  936.58  4743.5  920.15  4817.8  917.61  4848.6  914.31  4888.6  917.37
  4917.6  915.82  4987.4  917.00  4987.8  911.50  5011.6  911.50  5012.6  914.18
  5076.1  921.06  5148.8  922.41  5170.6  923.19  5231.4  932.37  5279.6  936.42
  5318.3  941.87  5356.8  953.23  5380.0  958.49  5443.5  959.63  5475.7  957.66
  5583.1  964.15  5603.5  963.93  5649.5  977.13  5669.9  977.10  5763.6  985.10
#Mann=8,-1,0
  4307.4    0.08       0  4817.8    0.14       0  4987.4    0.05       0
  5012.6    0.14       0  5148.8    0.08       0  5279.6    0.14       0
  5356.8    0.08       0  5583.1    0.08       0
#XS Ineff=2,0
    0.00 4926.50  940.20 5073.50    0.00  940.20
Permanent Ineff=
       F       F
Bank Sta=4987.4,5012.6
XS Rating Curve= 0
Exp/Cntr=0.5,0.3

Type RM Length L Ch R =2,76465,,,
BEGIN DESCRIPTION:
Union Grove Church Road  FC - TOR
Structure ID: LDS_FC_12
Approximate Survey Structure
END DESCRIPTION:
Bridge Culvert--1,0,-1,-1,0
Deck Dist Width WeirC Skew NumUp NumDn MinLoCord MaxHiCord MaxSubmerge Is_Ogee
62,80,3,,9,9,,,0.95,0,1,1,,,
  4271.4  4352.9  4504.6  4657.3  4793.9  5080.4  5177.3  5319.4  5784.7
  972.91  968.08  952.89  945.30  940.20  940.20  942.52  948.81  988.93
  891.50  891.50  891.50  891.50  891.50  891.50  891.50  891.50  891.50
  4271.4  4352.9  4504.6  4657.3  4793.9  5080.4  5177.3  5319.4  5784.7
  972.91  968.08  952.89  945.30  940.20  940.20  942.52  948.81  988.93
  891.10  891.10  891.10  891.10  891.10  891.10  891.10  891.10  891.10
Culvert=2,9,11,80,0.012,0.4,1,8,1,911.7,4994,911.3,4994,Culvert #1,0,62
Culvert Bottom n=0.012
Culvert Bottom Depth=0
Culvert Depth Blocked=0
Culvert=2,9,11,80,0.012,0.4,1,8,1,911.7,5006,911.3,5006,Culvert #2,0,62
Culvert Bottom n=0.012
Culvert Bottom Depth=0
Culvert Depth Blocked=0
BC Design=,,0,,0,,,,,,

Type RM Length L Ch R = 1,76359,359,359,359
BEGIN DESCRIPTION:
Union Grove Church Road  FC - ds
END DESCRIPTION:
XS GIS Cut Line= 4
      1519716.47       895250.61      1519549.66       894945.86
      1519062.07       894474.32      1518840.74       894143.92
#Sta/Elev= 30
  4277.8  970.44  4360.7  964.48  4444.9  953.52  4559.6  948.21  4620.7  942.72
  4670.7  939.86  4679.0  937.84  4719.9  933.34  4806.9  925.83  4881.3  917.58
  4937.3  916.60  4956.1  917.73  4987.4  915.27  4988.0  911.10  5012.1  911.10
  5012.6  914.55  5033.7  918.28  5051.1  917.67  5082.6  919.64  5102.6  919.28
  5138.0  923.05  5148.6  927.38  5168.8  932.96  5188.6  936.95  5199.6  937.26
  5253.8  939.23  5296.2  942.36  5451.3  958.50  5556.8  971.78  5701.2  985.46
#Mann=5,-1,0
  4277.8    0.08       0  4559.6    0.14       0  4987.4    0.05       0
  5012.6    0.14       0  5199.6    0.08       0
#XS Ineff=2,0
    0.00 4922.50  940.20 5077.50    0.00  940.20
Permanent Ineff=
       F       F
Bank Sta=4987.4,5012.6
XS Rating Curve= 0
Exp/Cntr=0.5,0.3

Type RM Length L Ch R = 1,76000,445,445,445
BEGIN DESCRIPTION:
Forbush Creek - 80.0
END DESCRIPTION:
XS GIS Cut Line= 3
      1519947.39       894477.53      1519665.14       894525.64
      1519219.24       894240.13
#Sta/Elev= 30
  4419.0  958.32  4494.8  957.05  4615.4  951.89  4673.0  950.03  4697.0  947.63
  4722.3  943.40  4754.2  935.62  4798.3  926.38  4833.2  920.55  4870.8  917.53
  4876.8  917.59  4903.4  915.21  4945.3  915.26  4953.2  914.51  4989.4  915.12
  4994.4  913.68  4995.4  911.41  4996.8  908.41  5003.2  908.41  5004.6  911.41
  5036.0  915.33  5062.9  926.67  5099.7  937.42  5116.2  942.96  5137.2  948.94
  5147.5  951.79  5161.9  951.59  5167.9  952.14  5204.5  954.22  5234.8  957.20
#Mann=7,-1,0
  4419.0    0.08       0  4615.4    0.14       0  4995.4    0.05       0
  5004.6    0.14       0  5137.2    0.08       0  5167.9    0.14       0
  5204.5    0.08       0
Bank Sta=4995.4,5004.6
XS Rating Curve= 0
Exp/Cntr=0.3,0.1

Type RM Length L Ch R = 1,75555,914,914,914
BEGIN DESCRIPTION:
Forbush Creek - 79.0
END DESCRIPTION:
XS GIS Cut Line= 2
      1519950.65       893957.86      1519132.66       893919.37
#Sta/Elev= 30
  4541.5  949.57  4567.7  948.81  4621.4  945.09  4711.3  936.33  4747.1  931.76
  4795.6  921.87  4819.2  918.44  4841.7  916.23  4857.0  915.66  4877.1  914.07
  4926.5  911.69  4964.2  913.74  4979.9  913.90  4994.9  908.41  4996.4  905.41
  5003.6  905.41  5005.1  908.41  5011.4  914.58  5016.4  914.43  5058.1  913.21
  5085.2  913.27  5100.3  914.35  5107.8  915.42  5112.9  916.99  5134.7  923.25
  5153.9  929.95  5195.4  940.84  5239.8  951.68  5272.1  959.17  5360.4  973.89
#Mann=11,-1,0
  4541.5    0.08       0  4857.0     0.1       0  4926.5    0.08       0
  4964.2    0.14       0  4994.9    0.05       0  5005.1    0.14       0
  5016.4    0.08       0  5112.9    0.14       0  5195.4    0.08       0
  5239.8    0.14       0  5272.1    0.08       0
Bank Sta=4994.9,5005.1
XS Rating Curve= 0
Exp/Cntr=0.3,0.1

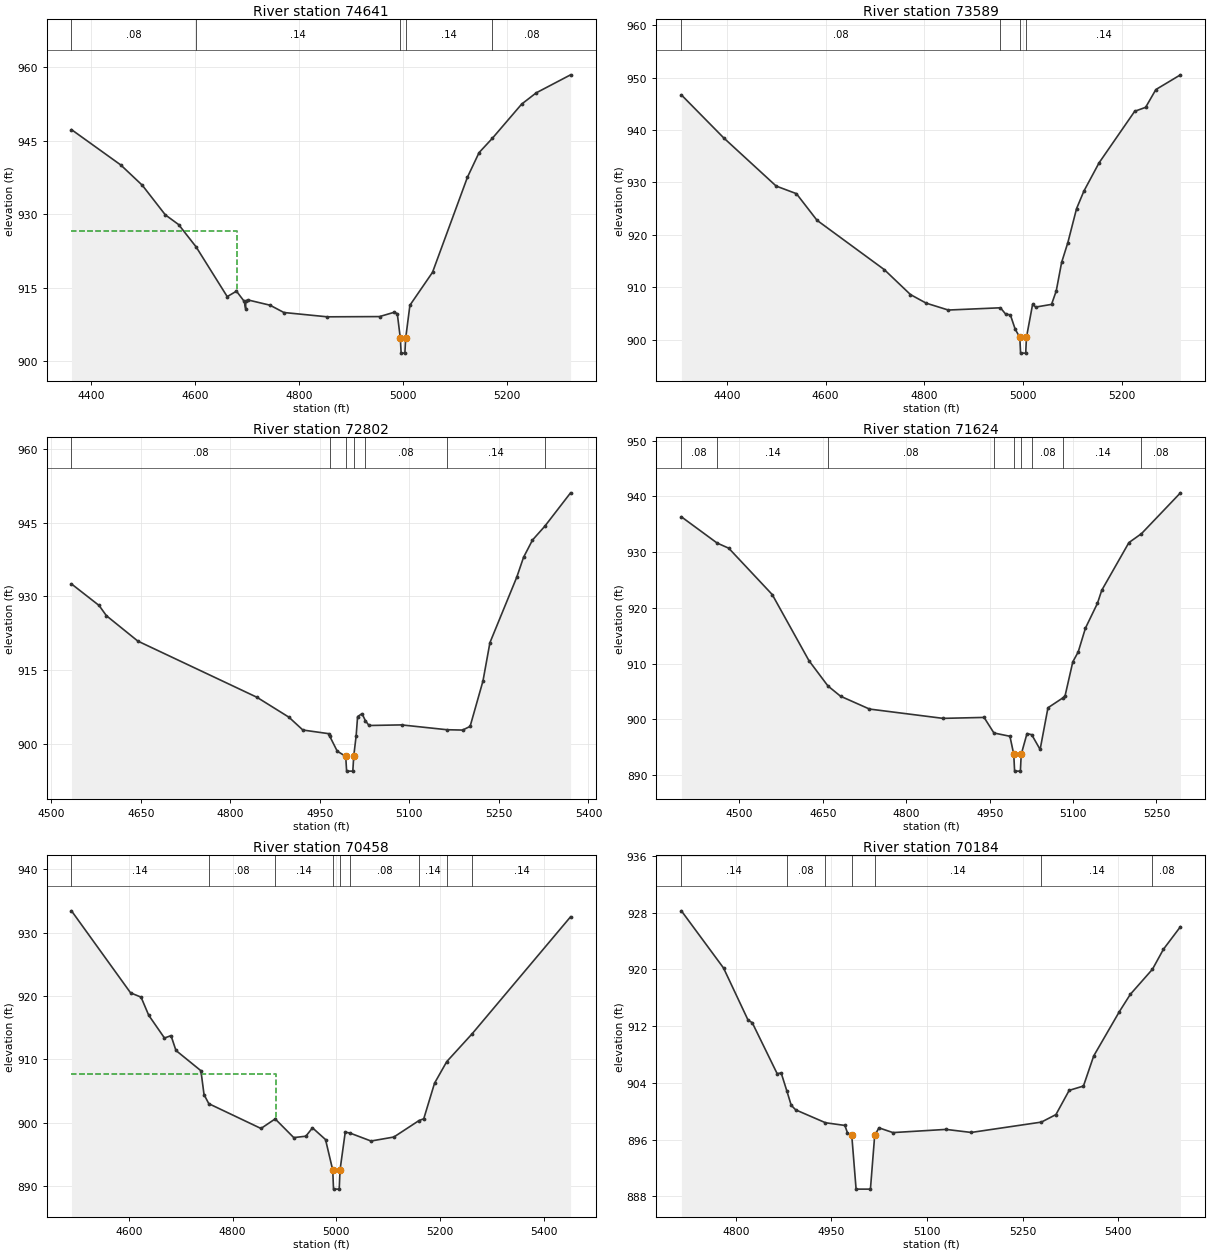
Type RM Length L Ch R = 1,74641,1052,1052,1052
BEGIN DESCRIPTION:
Forbush Creek - 78.0
END DESCRIPTION:
XS GIS Cut Line= 3
      1520239.34       893101.38      1519507.96       893062.89
      1519328.36       892921.77
#Sta/Elev= 30
  4361.8  947.23  4456.6  940.03  4498.2  935.88  4542.4  929.86  4568.1  927.87
  4601.8  923.31  4661.6  913.19  4679.4  914.30  4694.4  912.21  4697.0  910.76
  4697.4  912.27  4701.2  912.52  4744.0  911.44  4770.7  909.95  4854.4  909.07
  4954.8  909.12  4983.5  910.01  4989.0  909.71  4994.9  904.67  4996.4  901.67
  5003.6  901.67  5005.1  904.67  5013.3  911.43  5056.8  918.14  5124.1  937.54
  5146.4  942.54  5171.9  945.45  5228.5  952.44  5256.5  954.73  5322.6  958.40
#Mann=5,-1,0
  4361.8    0.08       0  4601.8    0.14       0  4994.9    0.05       0
  5005.1    0.14       0  5171.9    0.08       0
#XS Ineff=2,0
    0.00 4680.10  926.50               0
Permanent Ineff=
       F       F
Bank Sta=4994.9,5005.1
XS Rating Curve= 0
Exp/Cntr=0.3,0.1

Type RM Length L Ch R = 1,73589,787,787,787
BEGIN DESCRIPTION:
Forbush Creek - 77.0
END DESCRIPTION:
XS GIS Cut Line= 4
      1520560.12       892549.65      1520402.93       892337.93
      1519957.05       892161.50      1519690.81       892139.04
#Sta/Elev= 30
  4308.1  946.71  4393.7  938.52  4500.0  929.32  4541.0  927.87  4582.7  922.79
  4718.9  913.38  4771.9  908.62  4803.8  906.98  4848.5  905.67  4954.0  906.10
  4964.3  904.93  4974.2  904.73  4983.8  902.04  4993.3  900.45  4994.8  897.45
  5005.2  897.45  5006.7  900.45  5019.1  906.73  5025.7  906.24  5057.5  906.75
  5067.0  909.31  5077.9  914.75  5090.5  918.53  5108.2  925.03  5123.1  928.38
  5153.7  933.75  5225.8  943.58  5248.0  944.34  5268.7  947.73  5318.5  950.54
#Mann=4,-1,0
  4308.1    0.08       0  4954.0    0.14       0  4993.3    0.05       0
  5006.7    0.14       0
Bank Sta=4993.3,5006.7
XS Rating Curve= 0
Exp/Cntr=0.3,0.1

Type RM Length L Ch R = 1,72802,1178,1178,1178
BEGIN DESCRIPTION:
Forbush Creek - 76.0
END DESCRIPTION:
XS GIS Cut Line= 2
      1520771.83       891680.33      1520005.17       891346.72
#Sta/Elev= 30
  4533.9  932.52  4580.1  928.15  4592.4  926.07  4645.1  920.91  4844.6  909.50
  4898.1  905.46  4921.5  902.85  4964.8  902.11  4966.5  901.60  4979.1  898.55
  4993.3  897.50  4994.8  894.50  5005.2  894.50  5006.7  897.50  5010.8  901.71
  5013.2  905.58  5020.6  906.17  5026.2  904.76  5032.3  903.77  5086.9  903.89
  5162.8  902.91  5189.1  902.84  5201.7  903.59  5223.2  912.79  5234.9  920.60
  5279.9  933.91  5291.2  937.93  5306.2  941.44  5326.8  944.24  5370.0  951.03
#Mann=7,-1,0
  4533.9    0.08       0  4966.5    0.14       0  4993.3    0.05       0
  5006.7    0.14       0  5026.2    0.08       0  5162.8    0.14       0
  5326.8    0.08       0
Bank Sta=4993.3,5006.7
XS Rating Curve= 0
Exp/Cntr=0.3,0.1

Type RM Length L Ch R = 1,71624,1166,1166,1166
BEGIN DESCRIPTION:
Forbush Creek - 75.0
END DESCRIPTION:
XS GIS Cut Line= 3
      1521230.56       890766.15      1521137.52       890547.98
      1520511.96       890336.25
#Sta/Elev= 30
  4395.5  936.32  4459.7  931.62  4480.7  930.69  4558.9  922.38  4625.0  910.52
  4659.1  905.99  4681.8  904.15  4733.8  901.85  4866.1  900.18  4939.9  900.35
  4957.6  897.56  4986.4  896.97  4993.3  893.72  4994.8  890.72  5005.2  890.72
  5006.7  893.72  5017.1  897.46  5025.6  897.25  5040.7  894.60  5054.8  902.08
  5082.5  903.91  5085.7  904.28  5099.5  910.32  5109.2  912.09  5122.2  916.36
  5143.8  920.81  5151.5  923.14  5200.4  931.70  5223.0  933.30  5293.1  940.62
#Mann=9,-1,0
  4395.5    0.08       0  4459.7    0.14       0  4659.1    0.08       0
  4957.6    0.14       0  4993.3    0.05       0  5006.7    0.14       0
  5025.6    0.08       0  5082.5    0.14       0  5223.0    0.08       0
Bank Sta=4993.3,5006.7
XS Rating Curve= 0
Exp/Cntr=0.3,0.1

Type RM Length L Ch R = 1,70458,274,274,274
BEGIN DESCRIPTION:
Forbush Creek - 74.0
END DESCRIPTION:
XS GIS Cut Line= 4
      1521705.29       889457.33      1521467.92       889479.78
      1521038.07       889325.81      1520771.81       889322.60
#Sta/Elev= 30
  4489.8  933.44  4603.6  920.50  4623.8  919.82  4638.5  916.97  4668.9  913.37
  4681.5  913.75  4691.0  911.41  4739.1  908.21  4745.1  904.44  4754.3  903.01
  4854.8  899.10  4882.1  900.61  4917.9  897.66  4941.2  897.88  4954.0  899.20
  4979.1  897.35  4993.0  892.53  4994.5  889.53  5005.5  889.53  5007.0  892.53
  5017.1  898.53  5026.4  898.37  5066.7  897.12  5110.7  897.75  5159.2  900.35
  5168.3  900.63  5189.1  906.25  5212.6  909.65  5261.7  914.06  5451.1  932.50
#Mann=9,-1,0
  4489.8    0.14       0  4754.3    0.08       0  4882.1    0.14       0
  4993.0    0.05       0  5007.0    0.14       0  5026.4    0.08       0
  5159.2    0.14       0  5212.6    0.08       0  5261.7    0.14       0
#XS Ineff=2,0
    0.00 4884.50  907.75               0
Permanent Ineff=
       F       F
Bank Sta=4993,5007
XS Rating Curve= 0
Exp/Cntr=0.5,0.3

Type RM Length L Ch R = 1,70184,126,126,126
BEGIN DESCRIPTION:
Private Drive 2  FC - us
END DESCRIPTION:
XS GIS Cut Line= 4
      1521641.11       889354.66      1521243.37       889091.64
      1521111.85       889059.56      1520941.82       889043.52
#Sta/Elev= 30
  4714.7  928.28  4780.9  920.20  4819.3  912.86  4825.9  912.49  4864.9  905.31
  4871.3  905.39  4880.3  902.82  4887.0  900.84  4894.0  900.19  4940.8  898.37
  4971.2  897.99  4975.2  896.96  4982.0  896.60  4988.8  889.00  5011.3  889.00
  5018.0  896.60  5024.7  897.65  5046.6  896.98  5129.9  897.43  5169.4  897.00
  5279.5  898.46  5302.3  899.52  5323.1  902.94  5345.5  903.55  5361.6  907.80
  5401.7  914.03  5419.0  916.49  5453.8  920.04  5471.0  922.86  5497.7  926.04
#Mann=7,-1,0
  4714.7    0.14       0  4880.3    0.08       0  4940.8    0.14       0
  4982.0    0.05       0  5018.0    0.14       0  5279.5    0.14       0
  5453.8    0.08       0
#XS Ineff=2,0
    0.00 4919.80  898.05 5080.30    0.00  896.63
Permanent Ineff=
       F       F
Bank Sta=4982,5018
XS Rating Curve= 0
Exp/Cntr=0.5,0.3

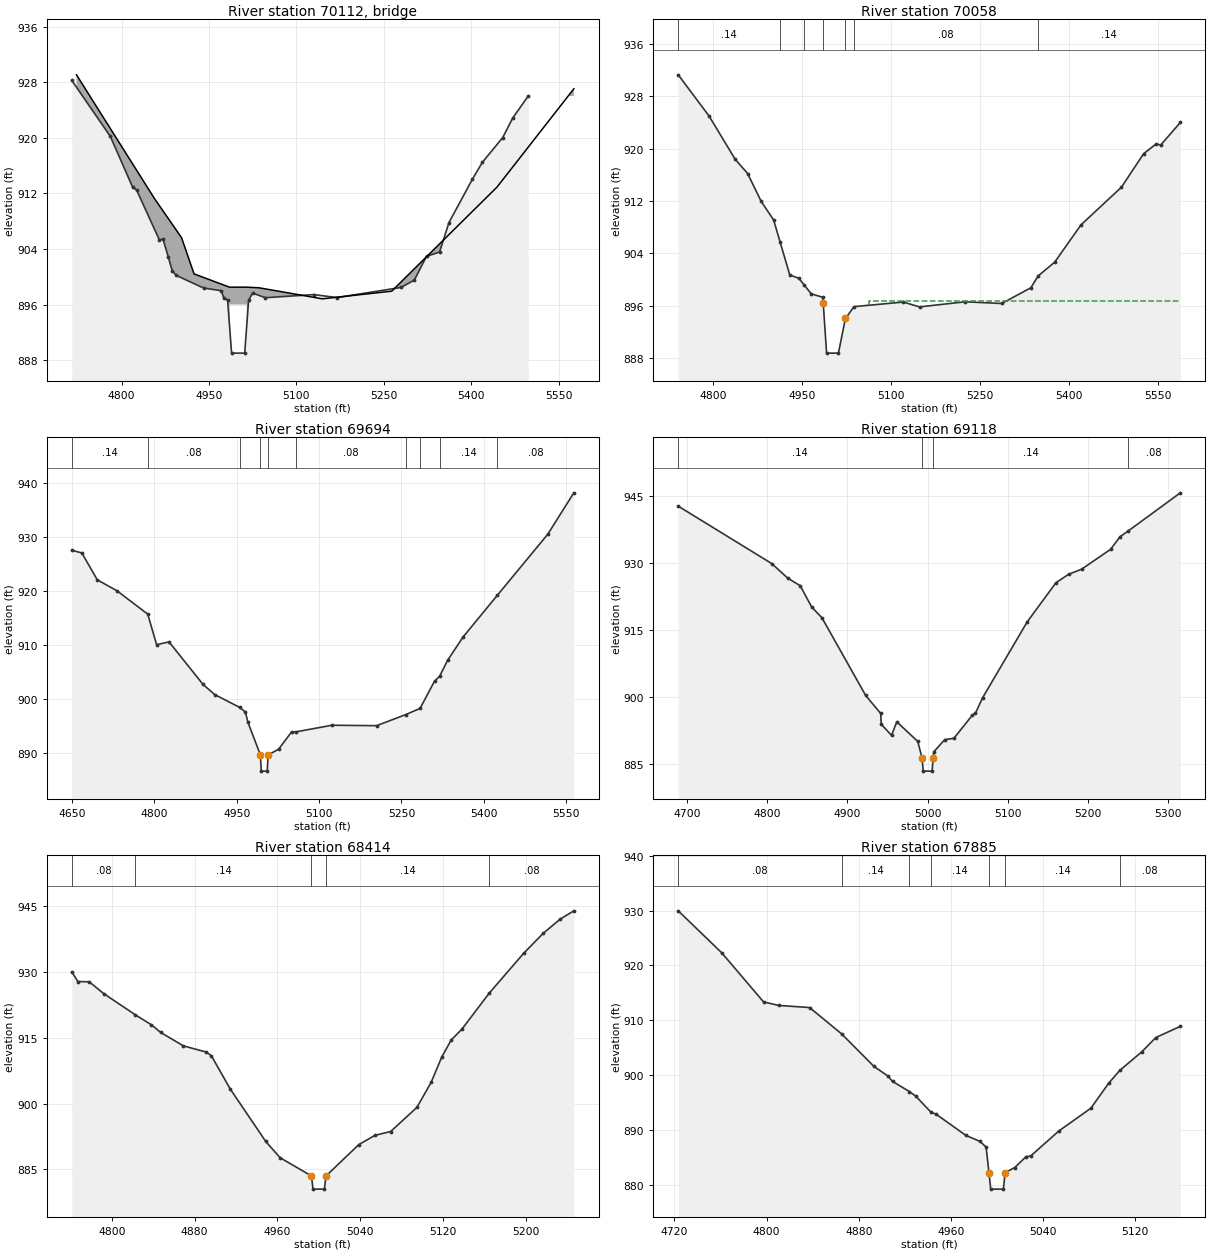
Type RM Length L Ch R =3,70112,,,
BEGIN DESCRIPTION:
Private Drive 2  FC - TOR
Structure ID: LDS_FC_10
Approximate Survey Structure
END DESCRIPTION:
Bridge Culvert--1,0,-1,-1,0
Deck Dist Width WeirC Skew NumUp NumDn MinLoCord MaxHiCord MaxSubmerge Is_Ogee
65.5,13,3,,13,13,,,0.95,0,1,1,,,
  4722.8  4856.0  4903.0  4924.4  4985.3  4985.3  5014.8  5014.8  5035.7  5144.4
  5263.4  5444.0  5575.8
  929.08  911.33  905.62  900.41  898.50  898.50  898.50  898.50  898.41  896.82
  897.92  912.91  927.07
  869.00  869.00  869.00  869.00  869.00  896.00  896.00  869.00  869.00  869.00
  869.00  869.00  869.00
  4722.8  4856.0  4903.0  4924.4  4985.3  4985.3  5014.8  5014.8  5035.7  5144.4
  5263.4  5444.0  5575.8
  929.08  911.33  905.62  900.41  898.50  898.50  898.50  898.50  898.41  896.82
  897.92  912.91  927.07
  869.00  869.00  869.00  869.00  869.00  896.00  896.00  869.00  869.00  869.00
  869.00  869.00  869.00
BR Coef=1,1,0,1.25,0,,,0.8,0,2,0,
WSPro=,,,, 1 ,,,, 0 ,,,, 0 ,,,,-1 ,-1 ,-1 , 0 , 0 , 0 , 0 , 0
BC Design=,,0,,0,,,,,,

Type RM Length L Ch R = 1,70058,364,364,364
BEGIN DESCRIPTION:
Private Drive 2  FC - ds
END DESCRIPTION:
XS GIS Cut Line= 4
      1521705.33       889236.01      1521281.87       888979.37
      1521134.31       888953.71      1520935.43       888992.20
#Sta/Elev= 30
  4740.9  931.31  4793.0  925.00  4837.0  918.40  4858.0  916.22  4881.0  911.94
  4901.9  909.12  4912.7  905.79  4929.2  900.71  4944.4  900.19  4953.1  899.22
  4965.4  897.82  4984.5  897.30  4985.7  896.35  4991.3  888.75  5011.3  888.75
  5023.1  894.05  5037.7  895.86  5120.7  896.56  5148.2  895.82  5225.2  896.60
  5287.0  896.34  5336.2  898.75  5348.3  900.54  5376.4  902.67  5420.9  908.38
  5489.0  914.12  5526.5  919.25  5547.1  920.70  5555.6  920.60  5588.4  924.02
#Mann=7,-1,0
  4740.9    0.14       0  4912.7    0.08       0  4953.1    0.14       0
  4985.7    0.05       0  5023.1    0.14       0  5037.7    0.08       0
  5348.3    0.14       0
#XS Ineff=2,0
    0.00 4937.80  897.78 5062.30    0.00  896.79
Permanent Ineff=
       F       F
Bank Sta=4985.7,5023.1
XS Rating Curve= 0
Exp/Cntr=0.5,0.3

Type RM Length L Ch R = 1,69694,576,576,576
BEGIN DESCRIPTION:
Forbush Creek - 73.0
END DESCRIPTION:
XS GIS Cut Line= 3
      1521894.58       888950.51      1521352.44       888626.51
      1521076.58       888562.36
#Sta/Elev= 30
  4649.3  927.58  4667.6  927.08  4695.8  922.09  4731.7  920.06  4787.7  915.73
  4803.9  910.06  4826.5  910.58  4888.5  902.69  4909.6  900.82  4955.2  898.43
  4965.6  897.59  4970.3  895.65  4993.0  889.61  4994.5  886.61  5005.5  886.61
  5007.0  889.61  5026.2  890.68  5050.0  893.91  5057.0  893.88  5123.2  895.12
  5204.8  895.04  5257.4  897.08  5283.9  898.24  5310.3  903.31  5319.5  904.20
  5334.2  907.18  5362.2  911.48  5424.4  919.19  5516.6  930.55  5564.1  938.23
#Mann=10,-1,0
  4649.3    0.14       0  4787.7    0.08       0  4955.2    0.14       0
  4993.0    0.05       0  5007.0    0.14       0  5057.0    0.08       0
  5257.4    0.14       0  5283.9    0.08       0  5319.5    0.14       0
  5424.4    0.08       0
Bank Sta=4993,5007
XS Rating Curve= 0
Exp/Cntr=0.3,0.1

Type RM Length L Ch R = 1,69118,704,704,704
BEGIN DESCRIPTION:
Forbush Creek - 72.0
END DESCRIPTION:
XS GIS Cut Line= 3
      1522048.54       888684.29      1521958.71       888315.36
      1522067.79       888093.99
#Sta/Elev= 30
  4688.8  942.70  4805.6  929.83  4825.4  926.59  4841.0  924.89  4855.3  920.13
  4868.1  917.72  4922.7  900.33  4941.5  896.29  4942.1  893.88  4955.0  891.39
  4961.5  894.43  4987.6  890.05  4993.0  886.39  4994.5  883.39  5005.5  883.39
  5007.0  886.39  5007.6  887.70  5021.3  890.43  5032.8  890.74  5055.8  895.91
  5059.7  896.36  5068.5  899.79  5124.3  916.81  5160.1  925.55  5175.9  927.45
  5192.1  928.58  5228.2  933.02  5240.2  935.87  5249.5  937.04  5315.3  945.68
#Mann=4,-1,0
  4688.8    0.14       0  4993.0    0.05       0  5007.0    0.14       0
  5249.5    0.08       0
Bank Sta=4993,5007
XS Rating Curve= 0
Exp/Cntr=0.3,0.1

Type RM Length L Ch R = 1,68414,529,529,529
BEGIN DESCRIPTION:
Forbush Creek - 71.0
END DESCRIPTION:
XS GIS Cut Line= 2
      1522577.81       888729.19      1522603.48       888244.77
#Sta/Elev= 30
  4761.4  930.03  4767.3  927.82  4778.3  927.76  4792.2  925.08  4822.8  920.23
  4838.3  917.96  4847.4  916.20  4869.2  913.15  4891.2  911.74  4896.2  910.92
  4914.5  903.31  4948.8  891.35  4962.7  887.63  4993.0  883.47  4994.5  880.47
  5005.5  880.47  5007.0  883.47  5038.8  890.64  5054.4  892.74  5069.5  893.61
  5094.9  899.12  5108.6  904.81  5118.8  910.56  5127.9  914.45  5138.4  916.97
  5164.6  925.13  5198.0  934.26  5217.0  938.84  5233.4  942.07  5246.5  943.95
#Mann=5,-1,0
  4761.4    0.08       0  4822.8    0.14       0  4993.0    0.05       0
  5007.0    0.14       0  5164.6    0.08       0
Bank Sta=4993,5007
XS Rating Curve= 0
Exp/Cntr=0.3,0.1

Type RM Length L Ch R = 1,67885,136,136,136
BEGIN DESCRIPTION:
Forbush Creek - 70.0
END DESCRIPTION:
XS GIS Cut Line= 3
      1522821.63       888906.72      1523068.62       888663.53
      1523093.31       888578.05
#Sta/Elev= 30
  4723.4  929.95  4761.3  922.27  4797.4  913.36  4810.7  912.71  4837.4  912.33
  4865.1  907.54  4893.2  901.61  4905.3  899.85  4909.3  898.88  4924.0  897.02
  4929.3  896.22  4942.8  893.24  4947.0  892.92  4973.0  889.03  4985.2  887.95
  4990.5  886.91  4993.0  882.25  4994.5  879.25  5005.5  879.25  5007.0  882.25
  5015.4  883.19  5025.0  885.14  5029.2  885.29  5053.6  889.84  5081.4  893.99
  5096.8  898.53  5106.5  900.88  5125.7  904.29  5137.8  906.87  5159.0  908.90
#Mann=7,-1,0
  4723.4    0.08       0  4865.1    0.14       0  4924.0    0.08       0
  4942.8    0.14       0  4993.0    0.05       0  5007.0    0.14       0
  5106.5    0.08       0
Bank Sta=4993,5007
XS Rating Curve= 0
Exp/Cntr=0.5,0.3

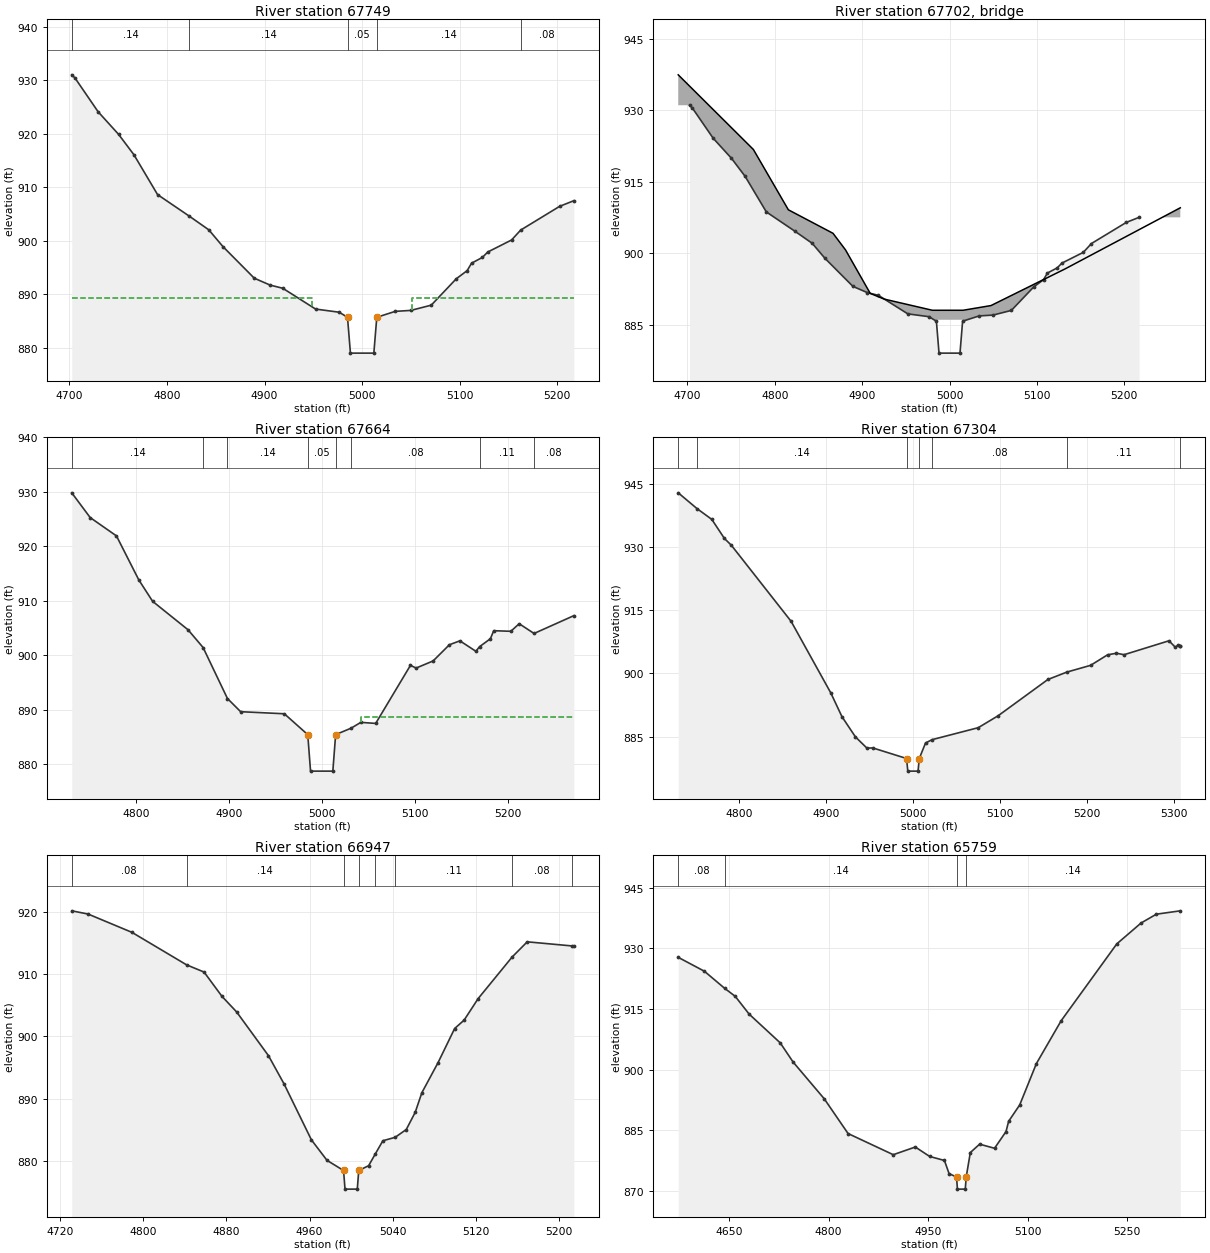
Type RM Length L Ch R = 1,67749,85,85,85
BEGIN DESCRIPTION:
Griffin Road  FC - us
END DESCRIPTION:
XS GIS Cut Line= 3
      1523113.38       889098.41      1523121.72       888698.01
      1523100.02       888586.18
#Sta/Elev= 30
  4702.5  931.05  4705.8  930.46  4729.5  924.14  4750.5  919.91  4766.2  916.10
  4790.4  908.65  4822.9  904.62  4842.9  902.06  4857.4  898.92  4889.5  893.01
  4905.8  891.72  4918.7  891.13  4952.3  887.24  4976.5  886.65  4985.0  885.70
  4988.0  879.00  5012.0  879.00  5015.0  885.70  5033.9  886.81  5049.9  886.99
  5070.8  887.97  5096.4  892.90  5107.6  894.43  5112.1  895.82  5123.2  896.90
  5128.7  897.91  5153.1  900.16  5162.4  902.01  5202.3  906.45  5216.9  907.51
#Mann=5,-1,0
  4702.5    0.14       0  4822.9    0.14       0  4985.0    0.05       0
  5015.0    0.14       0  5162.4    0.08       0
#XS Ineff=2,0
    0.00 4948.50  889.26 5051.50    0.00  889.35
Permanent Ineff=
       F       F
Bank Sta=4985,5015
XS Rating Curve= 0
Exp/Cntr=0.5,0.3

Type RM Length L Ch R =3,67702,,,
BEGIN DESCRIPTION:
Griffin Road  FC - TOR
Structure ID: LDS_FC_09
Approximate Survey Structure
END DESCRIPTION:
Bridge Culvert--1,0,-1,-1,0
Deck Dist Width WeirC Skew NumUp NumDn MinLoCord MaxHiCord MaxSubmerge Is_Ogee
36.5,21,3,,16,16,,,0.95,0,1,1,,,
  4689.6  4775.6  4815.6  4866.7  4881.0  4909.3  4925.2  4980.4  4985.0  4985.0
  5015.0  5015.0  5015.5  5047.5  5132.4  5264.1
  937.44  921.76  909.10  904.16  900.68  891.54  890.35  888.00  888.00  888.00
  888.00  888.00  888.00  888.99  896.70  909.52
  859.00  859.00  859.00  859.00  859.00  859.00  859.00  859.00  859.00  886.00
  886.00  859.00  859.00  859.00  859.00  859.00
  4689.6  4775.6  4815.6  4866.7  4881.0  4909.3  4925.2  4980.4  4985.0  4985.0
  5015.0  5015.0  5015.5  5047.5  5132.4  5264.1
  937.44  921.76  909.10  904.16  900.68  891.54  890.35  888.00  888.00  888.00
  888.00  888.00  888.00  888.99  896.70  909.52
  859.00  859.00  859.00  859.00  859.00  859.00  859.00  859.00  859.00  886.00
  886.00  859.00  859.00  859.00  859.00  859.00
Abutment Skew #Up #Dn=,2,2
  4985.0  4987.0
  886.00  881.23
  4985.0  4987.0
  886.00  880.98
Abutment Skew #Up #Dn=,2,2
  5013.0  5015.0
  881.23  886.00
  5013.0  5015.0
  880.98  886.00
BR Coef=1,1,0,1.25,0,,,0.8,0,2,0,
WSPro=,,,, 1 ,,,, 0 ,,,, 0 ,,,,-1 ,-1 ,-1 , 0 , 0 , 0 , 0 , 0
BC Design=,,0,,0,,,,,,

Type RM Length L Ch R = 1,67664,360,360,360
BEGIN DESCRIPTION:
Griffin Road  FC - ds
END DESCRIPTION:
XS GIS Cut Line= 3
      1523185.12       889103.44      1523200.14       888739.72
      1523116.71       888584.56
#Sta/Elev= 30
  4731.1  929.84  4750.9  925.30  4779.2  921.93  4803.2  913.86  4818.1  909.92
  4856.2  904.70  4872.4  901.44  4898.6  892.08  4912.8  889.66  4959.8  889.28
  4985.0  885.45  4988.0  878.75  5012.0  878.75  5015.0  885.45  5031.7  886.64
  5042.1  887.70  5058.1  887.51  5095.5  898.17  5101.6  897.67  5119.9  898.98
  5137.4  901.95  5148.7  902.67  5165.9  900.75  5169.8  901.59  5181.5  903.05
  5185.1  904.53  5203.5  904.42  5212.5  905.81  5228.5  904.02  5271.3  907.29
#Mann=8,-1,0
  4731.1    0.14       0  4872.4    0.08       0  4898.6    0.14       0
  4985.0    0.05       0  5015.0    0.14       0  5031.7    0.08       0
  5169.8    0.11       0  5228.5    0.08       0
#XS Ineff=2,0
    0.00 4957.50  888.84 5042.50    0.00  888.75
Permanent Ineff=
       F       F
Bank Sta=4985,5015
XS Rating Curve= 0
Exp/Cntr=0.5,0.3

Type RM Length L Ch R = 1,67304,357,357,357
BEGIN DESCRIPTION:
Forbush Creek - 69.0
END DESCRIPTION:
XS GIS Cut Line= 3
      1523652.87       888632.20      1523320.20       888749.08
      1523140.37       888614.21
#Sta/Elev= 30
  4730.1  942.91  4751.7  939.16  4768.7  936.60  4783.2  932.07  4791.2  930.45
  4859.9  912.38  4905.5  895.39  4918.4  889.72  4933.9  884.92  4947.1  882.26
  4953.9  882.30  4992.7  879.79  4994.1  876.79  5005.9  876.79  5007.3  879.79
  5014.5  883.47  5022.1  884.27  5075.1  887.11  5098.1  889.96  5155.2  898.56
  5177.0  900.32  5204.3  901.92  5223.9  904.43  5234.1  904.80  5242.8  904.45
  5294.5  907.76  5301.8  906.21  5305.1  906.78  5307.3  906.54  5307.5  906.52
#Mann=7,-1,0
  4730.1    0.08       0  4751.7    0.14       0  4992.7    0.05       0
  5007.3    0.14       0  5022.1    0.08       0  5177.0    0.11       0
  5307.3    0.08       0
Bank Sta=4992.7,5007.3
XS Rating Curve= 0
Exp/Cntr=0.3,0.1

Type RM Length L Ch R = 1,66947,1188,1188,1188
BEGIN DESCRIPTION:
Forbush Creek - 68.0
END DESCRIPTION:
XS GIS Cut Line= 2
      1523468.52       888268.07      1523059.45       888524.30
#Sta/Elev= 30
  4731.4  920.22  4747.1  919.70  4789.3  916.75  4841.8  911.52  4858.6  910.36
  4875.8  906.45  4889.9  903.94  4920.5  896.90  4935.5  892.35  4961.8  883.34
  4976.8  880.04  4992.7  878.41  4994.1  875.41  5005.9  875.41  5007.3  878.41
  5016.8  879.18  5023.4  881.13  5030.5  883.20  5042.3  883.75  5053.0  885.01
  5061.6  887.78  5068.0  890.94  5083.5  895.76  5099.5  901.27  5108.6  902.62
  5122.1  906.09  5154.8  912.79  5169.3  915.23  5212.2  914.57  5214.1  914.53
#Mann=8,-1,0
  4731.4    0.08       0  4841.8    0.14       0  4992.7    0.05       0
  5007.3    0.14       0  5023.4    0.08       0  5042.3    0.11       0
  5154.8    0.08       0  5212.2    0.14       0
Bank Sta=4992.7,5007.3
XS Rating Curve= 0
Exp/Cntr=0.3,0.1

Type RM Length L Ch R = 1,65759,753,753,753
BEGIN DESCRIPTION:
Forbush Creek - 67.0
END DESCRIPTION:
XS GIS Cut Line= 3
      1523509.02       888303.99      1523531.50       887796.00
      1523360.68       887616.19
#Sta/Elev= 30
  4573.4  927.79  4612.8  924.36  4643.3  920.14  4659.3  918.15  4680.3  913.75
  4727.1  906.65  4746.4  901.93  4793.4  892.83  4829.3  884.24  4897.4  879.01
  4930.6  880.91  4952.2  878.58  4974.5  877.58  4981.5  874.33  4992.7  873.50
  4994.1  870.50  5005.9  870.50  5007.3  873.50  5013.5  879.54  5027.5  881.61
  5050.0  880.60  5067.3  884.73  5071.2  887.26  5087.9  891.31  5113.1  901.55
  5150.4  912.13  5234.2  931.12  5270.8  936.28  5293.8  938.46  5329.9  939.29
#Mann=4,-1,0
  4573.4    0.08       0  4643.3    0.14       0  4992.7    0.05       0
  5007.3    0.14       0
Bank Sta=4992.7,5007.3
XS Rating Curve= 0
Exp/Cntr=0.3,0.1