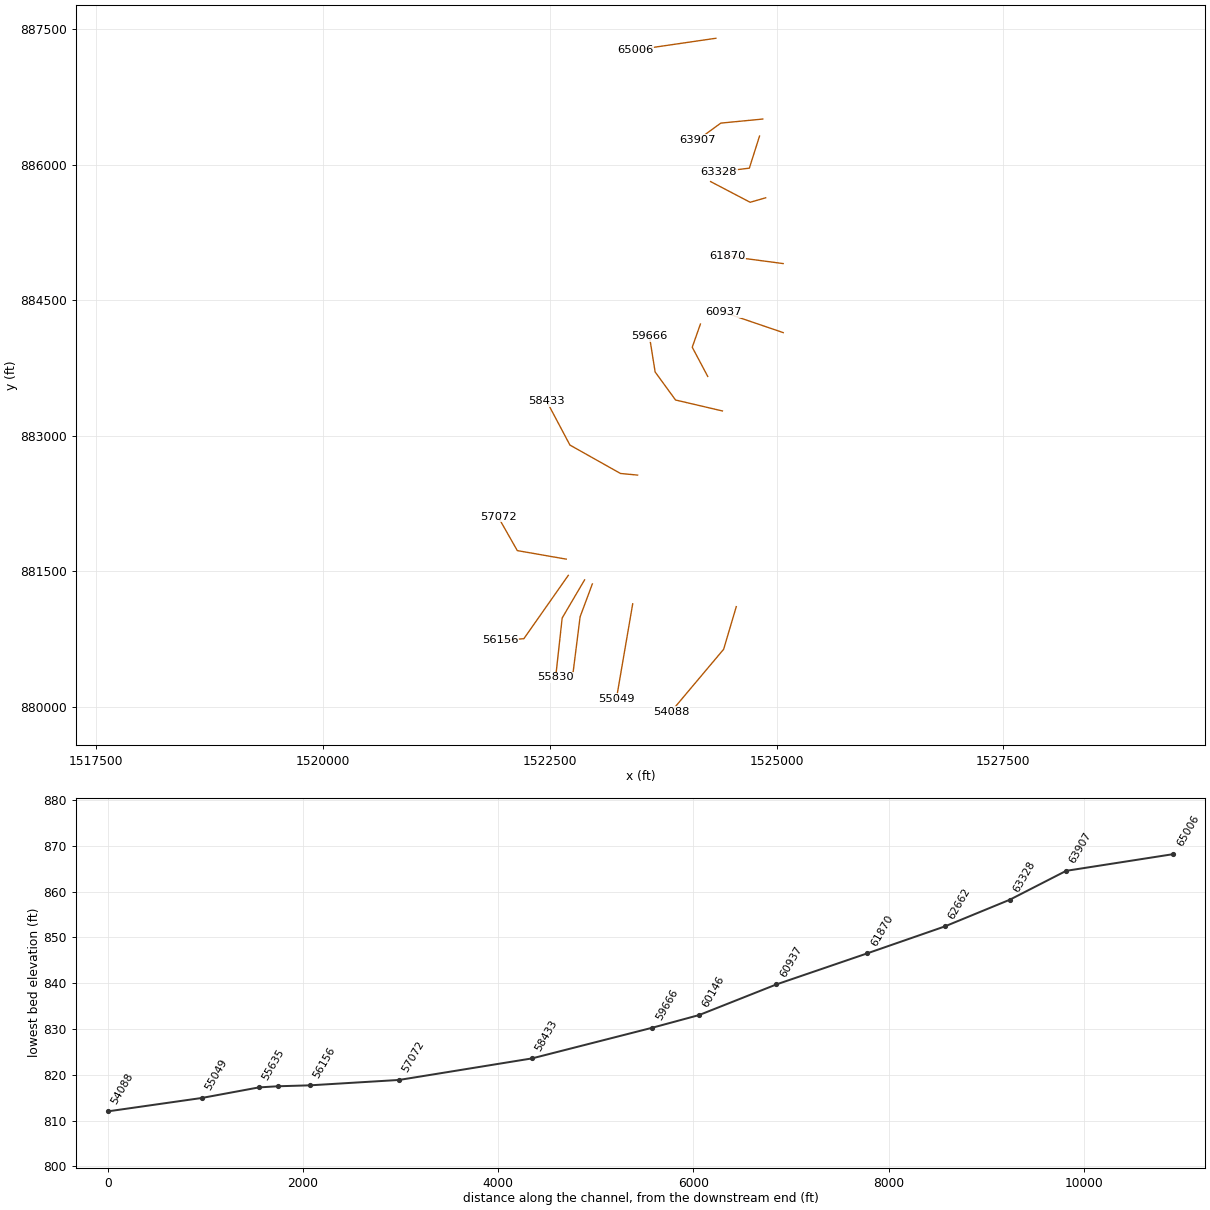
HEC-RAS study Forbush Creek.prj: Forbush Creek Limited Detail Study

--- Forbush Creek.g01 (geometry) --- (continued)

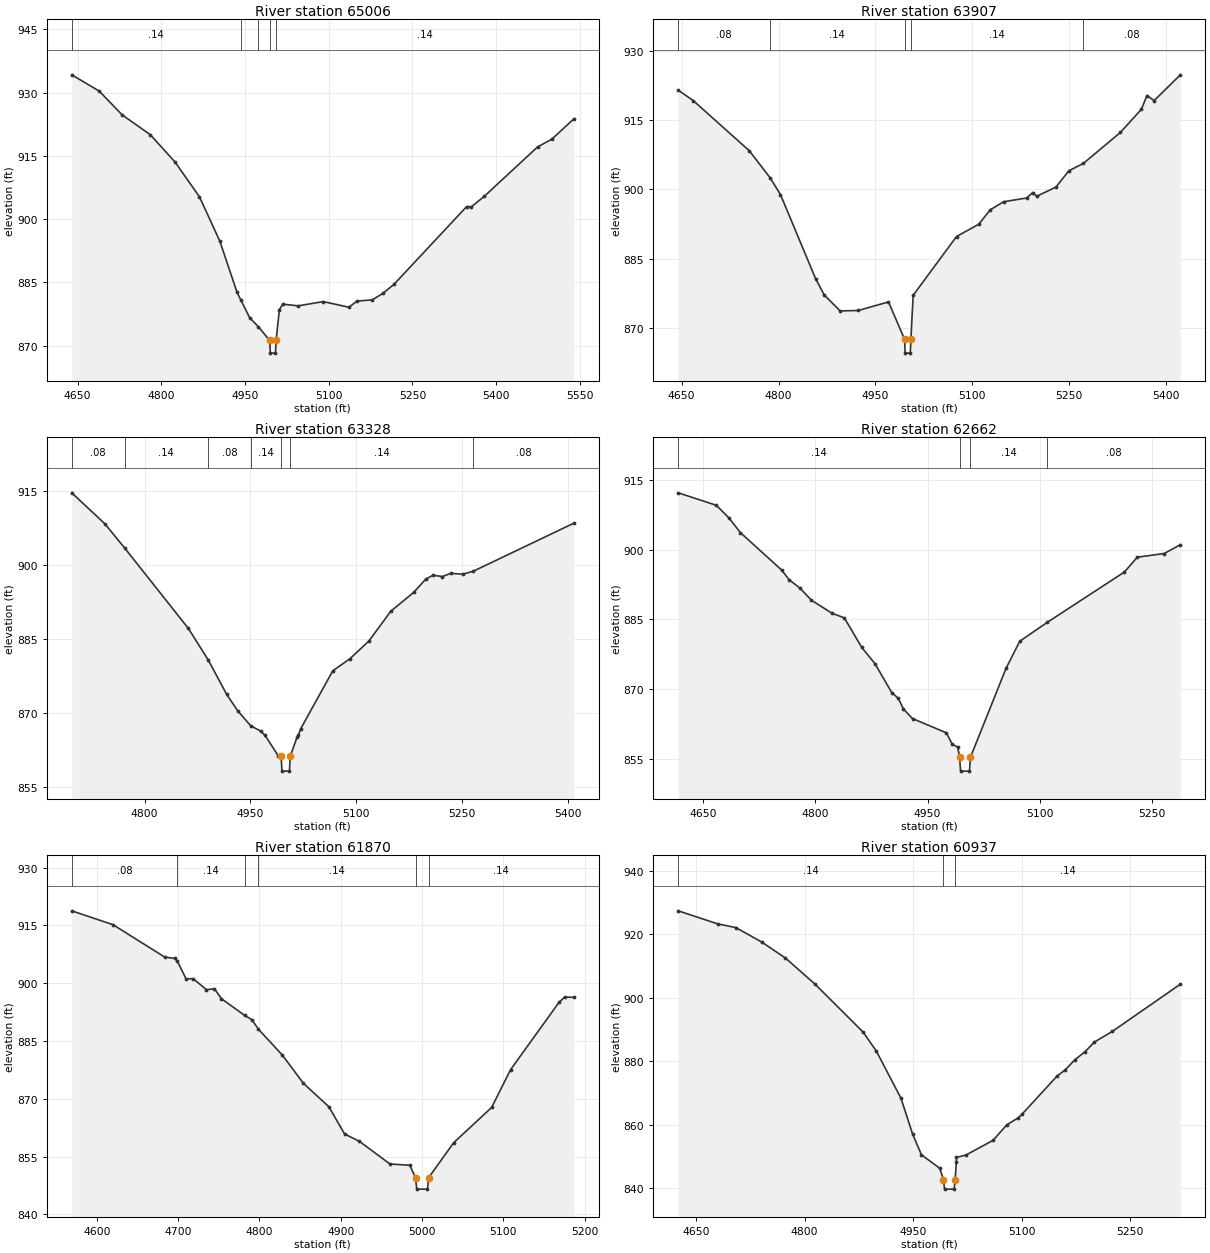
Type RM Length L Ch R = 1,65006,1099,1099,1099
BEGIN DESCRIPTION:
Forbush Creek - 66.0
END DESCRIPTION:
XS GIS Cut Line= 2
      1524331.72       887400.38      1523441.62       887270.01
#Sta/Elev= 30
  4639.6  934.23  4688.9  930.36  4729.8  924.74  4780.4  920.01  4824.8  913.51
  4868.4  905.28  4905.0  894.73  4935.6  882.65  4942.5  880.81  4958.2  876.63
  4973.9  874.45  4994.3  871.19  4995.4  868.19  5004.6  868.19  5005.7  871.19
  5011.6  878.49  5017.6  879.81  5045.5  879.41  5090.2  880.42  5136.3  879.08
  5150.5  880.53  5177.9  880.83  5196.9  882.35  5216.8  884.49  5347.0  902.95
  5355.8  902.92  5379.0  905.43  5474.2  917.12  5499.9  918.98  5539.2  923.78
#Mann=5,-1,0
  4639.6    0.14       0  4942.5    0.08       0  4973.9    0.14       0
  4994.3    0.05       0  5005.7    0.14       0
Bank Sta=4994.3,5005.7
XS Rating Curve= 0
Exp/Cntr=0.3,0.1

Type RM Length L Ch R = 1,63907,579,579,579
BEGIN DESCRIPTION:
Forbush Creek - 65.0
END DESCRIPTION:
XS GIS Cut Line= 3
      1524848.77       886505.74      1524385.67       886460.78
      1524133.91       886276.46
#Sta/Elev= 30
  4644.7  921.46  4667.8  919.23  4754.6  908.37  4786.8  902.53  4803.0  898.86
  4857.3  880.68  4870.7  877.13  4895.4  873.67  4923.5  873.77  4970.2  875.63
  4995.1  867.54  4996.0  864.54  5004.0  864.54  5004.9  867.54  5008.4  877.06
  5075.5  889.78  5110.0  892.45  5127.7  895.56  5148.3  897.31  5184.1  898.13
  5193.5  899.30  5199.7  898.50  5229.4  900.48  5249.3  904.00  5272.1  905.63
  5329.2  912.31  5361.9  917.36  5370.3  920.31  5381.5  919.21  5422.0  924.79
#Mann=5,-1,0
  4644.7    0.08       0  4786.8    0.14       0  4995.1    0.05       0
  5004.9    0.14       0  5272.1    0.08       0
Bank Sta=4995.1,5004.9
XS Rating Curve= 0
Exp/Cntr=0.3,0.1

Type RM Length L Ch R = 1,63328,666,666,666
BEGIN DESCRIPTION:
Forbush Creek - 64.0
END DESCRIPTION:
XS GIS Cut Line= 3
      1524812.76       886316.91      1524700.37       885961.76
      1524363.20       885921.30
#Sta/Elev= 30
  4696.6  914.69  4743.5  908.41  4771.4  903.53  4861.9  887.19  4889.8  880.86
  4916.3  873.80  4931.7  870.51  4950.4  867.42  4964.5  866.34  4970.9  865.45
  4989.6  861.28  4993.5  861.22  4994.7  858.22  5005.3  858.22  5006.5  861.22
  5016.1  865.10  5018.0  865.50  5021.1  866.76  5066.8  878.57  5091.1  881.03
  5118.0  884.62  5149.0  890.65  5181.5  894.48  5198.3  897.12  5208.8  897.97
  5222.4  897.70  5234.0  898.36  5251.2  898.17  5266.2  898.79  5408.7  908.53
#Mann=7,-1,0
  4696.6    0.08       0  4771.4    0.14       0  4889.8    0.08       0
  4950.4    0.14       0  4993.5    0.05       0  5006.5    0.14       0
  5266.2    0.08       0
Bank Sta=4993.5,5006.5
XS Rating Curve= 0
Exp/Cntr=0.3,0.1

Type RM Length L Ch R = 1,62662,792,792,792
BEGIN DESCRIPTION:
Forbush Creek - 63.0
END DESCRIPTION:
XS GIS Cut Line= 3
      1524880.16       885633.57      1524709.36       885584.13
      1524273.28       885813.41
#Sta/Elev= 30
  4617.0  912.19  4667.9  909.51  4684.9  906.77  4699.9  903.66  4755.1  895.60
  4765.0  893.53  4779.8  891.68  4794.8  889.12  4822.2  886.33  4838.9  885.31
  4862.0  878.99  4879.9  875.44  4902.1  869.28  4910.9  868.03  4917.8  865.72
  4929.9  863.68  4975.0  860.63  4982.8  858.22  4990.3  857.52  4992.7  855.39
  4994.1  852.39  5005.9  852.39  5007.3  855.39  5054.7  874.45  5073.1  880.30
  5110.1  884.39  5212.8  895.17  5230.1  898.36  5266.0  899.15  5287.5  901.04
#Mann=4,-1,0
  4617.0    0.14       0  4992.7    0.05       0  5007.3    0.14       0
  5110.1    0.08       0
Bank Sta=4992.7,5007.3
XS Rating Curve= 0
Exp/Cntr=0.3,0.1

Type RM Length L Ch R = 1,61870,933,933,933
BEGIN DESCRIPTION:
Forbush Creek - 62.0
END DESCRIPTION:
XS GIS Cut Line= 3
      1525073.52       884905.28      1524601.47       884968.22
      1524462.10       884990.70
#Sta/Elev= 30
  4569.2  918.78  4620.0  915.17  4683.5  906.77  4696.6  906.41  4699.2  905.63
  4709.7  901.13  4718.5  901.15  4734.8  898.32  4744.7  898.54  4753.2  895.98
  4781.8  891.63  4790.8  890.51  4798.7  888.05  4828.0  881.37  4854.0  874.01
  4885.4  867.91  4904.6  860.86  4923.0  858.92  4960.5  853.05  4984.8  852.73
  4991.9  849.53  4993.4  846.53  5006.6  846.53  5008.1  849.53  5038.8  858.57
  5085.5  867.73  5108.8  877.54  5168.3  895.00  5175.2  896.38  5186.6  896.32
#Mann=6,-1,0
  4569.2    0.08       0  4699.2    0.14       0  4781.8    0.08       0
  4798.7    0.14       0  4991.9    0.05       0  5008.1    0.14       0
Bank Sta=4991.9,5008.1
XS Rating Curve= 0
Exp/Cntr=0.3,0.1

Type RM Length L Ch R = 1,60937,791,791,791
BEGIN DESCRIPTION:
Forbush Creek - 61.0
END DESCRIPTION:
XS GIS Cut Line= 2
      1525073.53       884141.01      1524417.15       884365.80
#Sta/Elev= 30
  4625.4  927.46  4679.7  923.36  4705.1  922.17  4740.5  917.66  4773.6  912.57
  4814.5  904.34  4881.1  889.19  4899.2  883.21  4933.2  868.38  4949.4  856.99
  4961.5  850.55  4986.8  846.29  4991.9  842.73  4993.4  839.73  5006.6  839.73
  5008.1  842.73  5009.7  848.34  5009.8  849.73  5022.9  850.47  5060.5  855.12
  5079.5  860.01  5094.9  862.16  5100.7  863.39  5148.8  875.36  5160.2  877.33
  5173.6  880.53  5187.5  883.04  5200.6  886.11  5225.3  889.45  5319.2  904.32
#Mann=3,-1,0
  4625.4    0.14       0  4991.9    0.05       0  5008.1    0.14       0
Bank Sta=4991.9,5008.1
XS Rating Curve= 0
Exp/Cntr=0.3,0.1

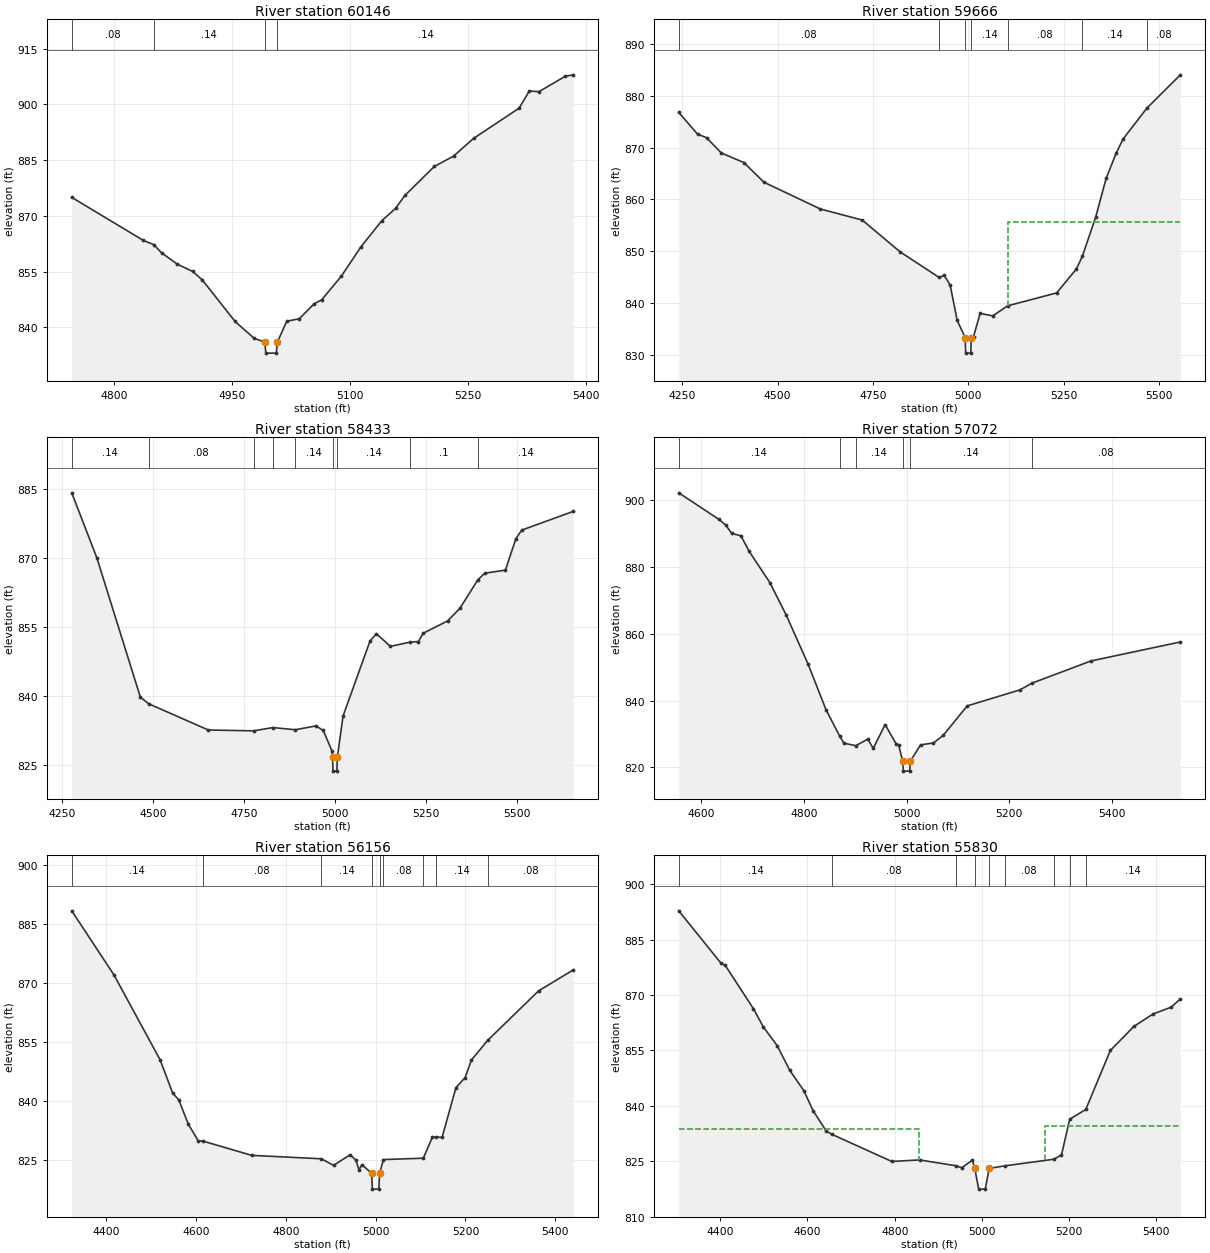
Type RM Length L Ch R = 1,60146,480,480,480
BEGIN DESCRIPTION:
Forbush Creek - 60.0
END DESCRIPTION:
XS GIS Cut Line= 3
      1524241.83       883655.45      1524070.98       883979.17
      1524160.89       884235.41
#Sta/Elev= 30
  4746.6  874.96  4837.5  863.39  4850.8  862.25  4860.7  860.06  4880.6  857.01
  4900.4  855.02  4912.5  852.76  4954.3  841.56  4978.6  837.00  4991.9  836.05
  4993.4  833.05  5006.6  833.05  5008.1  836.05  5019.9  841.62  5035.9  842.31
  5054.4  846.26  5064.4  847.42  5089.1  853.69  5114.4  861.70  5140.8  868.69
  5158.4  872.04  5170.1  875.47  5207.5  883.27  5232.0  886.06  5257.5  890.84
  5315.3  898.95  5328.2  903.56  5340.7  903.42  5373.9  907.53  5384.2  907.93
#Mann=4,-1,0
  4746.6    0.08       0  4850.8    0.14       0  4991.9    0.05       0
  5008.1    0.14       0
Bank Sta=4991.9,5008.1
XS Rating Curve= 0
Exp/Cntr=0.3,0.1

Type RM Length L Ch R = 1,59666,1233,1233,1233
BEGIN DESCRIPTION:
Forbush Creek - 59.0
END DESCRIPTION:
XS GIS Cut Line= 4
      1524403.67       883273.35      1523886.65       883394.73
      1523661.87       883704.93      1523598.92       884100.60
#Sta/Elev= 30
  4241.2  876.82  4290.4  872.63  4314.0  871.93  4352.9  868.97  4412.1  867.12
  4464.3  863.33  4612.3  858.15  4722.1  856.01  4821.2  849.87  4923.2  844.94
  4937.4  845.29  4952.7  843.42  4970.9  836.63  4991.9  833.28  4993.4  830.28
  5006.6  830.28  5008.1  833.28  5013.8  833.44  5031.1  837.96  5064.5  837.49
  5103.1  839.42  5231.7  841.92  5283.2  846.52  5299.2  849.01  5334.3  856.63
  5361.5  864.07  5387.8  868.93  5405.6  871.65  5468.2  877.64  5556.0  884.09
#Mann=7,-1,0
  4241.2    0.08       0  4923.2    0.14       0  4991.9    0.05       0
  5008.1    0.14       0  5103.1    0.08       0  5299.2    0.14       0
  5468.2    0.08       0
#XS Ineff=2,0
       0                 5105.00    0.00  855.54
Permanent Ineff=
       F       F
Bank Sta=4991.9,5008.1
XS Rating Curve= 0
Exp/Cntr=0.3,0.1

Type RM Length L Ch R = 1,58433,1361,1361,1361
BEGIN DESCRIPTION:
Forbush Creek - 58.0
END DESCRIPTION:
XS GIS Cut Line= 4
      1523468.58       882563.03      1523279.74       882581.02
      1522722.27       882895.71      1522466.00       883381.28
#Sta/Elev= 30
  4276.4  884.10  4345.6  869.92  4465.0  839.68  4488.0  838.22  4652.1  832.52
  4776.6  832.34  4829.2  833.05  4891.4  832.58  4947.7  833.41  4967.7  832.45
  4992.1  827.94  4993.4  826.58  4994.6  823.58  5005.4  823.58  5006.6  826.58
  5022.3  835.57  5096.6  851.91  5114.0  853.45  5152.5  850.72  5205.1  851.61
  5229.3  851.76  5242.6  853.56  5309.7  856.24  5343.9  859.02  5392.7  865.16
  5411.9  866.62  5468.7  867.29  5497.3  874.10  5513.5  875.99  5655.3  880.07
#Mann=9,-1,0
  4276.4    0.14       0  4488.0    0.08       0  4776.6    0.14       0
  4829.2    0.08       0  4891.4    0.14       0  4993.4    0.05       0
  5006.6    0.14       0  5205.1     0.1       0  5392.7    0.14       0
Bank Sta=4993.4,5006.6
XS Rating Curve= 0
Exp/Cntr=0.3,0.1

Type RM Length L Ch R = 1,57072,916,916,916
BEGIN DESCRIPTION:
Forbush Creek - 57.0
END DESCRIPTION:
XS GIS Cut Line= 3
      1522681.81       881632.43      1522142.33       881726.84
      1521931.03       882099.99
#Sta/Elev= 30
  4556.6  902.29  4634.5  894.36  4648.2  892.61  4659.6  890.13  4677.5  889.43
  4693.8  884.72  4733.9  875.40  4766.0  865.58  4808.5  850.90  4843.5  837.20
  4869.6  829.45  4878.2  827.25  4901.3  826.51  4924.5  828.46  4935.2  825.71
  4958.4  832.83  4979.8  827.02  4984.8  826.63  4992.5  821.88  4993.9  818.88
  5006.1  818.88  5007.5  821.88  5027.3  826.74  5052.5  827.34  5071.4  829.59
  5118.1  838.43  5220.6  843.22  5244.2  845.24  5358.9  851.89  5533.1  857.59
#Mann=6,-1,0
  4556.6    0.14       0  4869.6    0.08       0  4901.3    0.14       0
  4992.5    0.05       0  5007.5    0.14       0  5244.2    0.08       0
Bank Sta=4992.5,5007.5
XS Rating Curve= 0
Exp/Cntr=0.3,0.1

Type RM Length L Ch R = 1,56156,326,326,326
BEGIN DESCRIPTION:
Forbush Creek - 56.0
END DESCRIPTION:
XS GIS Cut Line= 3
      1522704.31       881452.63      1522214.26       880751.27
      1521953.48       880733.29
#Sta/Elev= 30
  4323.3  888.33  4417.1  872.11  4520.2  850.49  4548.1  842.06  4561.6  840.38
  4583.0  834.16  4605.4  829.90  4614.6  829.92  4724.1  826.27  4879.1  825.40
  4906.4  823.74  4943.3  826.42  4956.5  825.01  4962.7  822.63  4969.9  823.90
  4991.1  821.70  4992.9  817.70  5007.1  817.70  5008.9  821.70  5017.4  825.20
  5106.3  825.55  5126.4  830.88  5134.7  830.96  5148.0  830.82  5178.9  843.44
  5199.4  846.03  5213.3  850.44  5249.8  855.48  5362.8  868.00  5440.3  873.34
#Mann=9,-1,0
  4323.3    0.14       0  4614.6    0.08       0  4879.1    0.14       0
  4991.1    0.05       0  5008.9    0.14       0  5017.4    0.08       0
  5106.3    0.08       0  5134.7    0.14       0  5249.8    0.08       0
Bank Sta=4991.1,5008.9
XS Rating Curve= 0
Exp/Cntr=0.5,0.3

Type RM Length L Ch R = 1,55830,195,195,195
BEGIN DESCRIPTION:
Union Church Road  FC - us
END DESCRIPTION:
XS GIS Cut Line= 3
      1522884.11       881403.14      1522636.86       880980.55
      1522564.93       880324.19
#Sta/Elev= 30
  4304.9  892.77  4400.9  878.72  4411.5  878.00  4476.0  866.31  4498.4  861.44
  4530.4  856.32  4559.4  849.63  4591.5  844.14  4612.9  838.71  4642.5  833.29
  4656.4  832.30  4793.3  824.98  4857.1  825.40  4939.4  823.84  4953.7  823.29
  4978.0  825.33  4983.5  823.10  4992.5  817.50  5007.5  817.50  5016.5  823.10
  5052.5  823.80  5164.1  825.57  5182.3  826.72  5201.1  836.40  5238.0  839.04
  5294.3  855.00  5348.5  861.52  5392.3  864.87  5433.9  866.72  5454.8  868.93
#Mann=9,-1,0
  4304.9    0.14       0  4656.4    0.08       0  4939.4    0.14       0
  4983.5    0.05       0  5016.5    0.14       0  5052.5    0.08       0
  5164.1    0.14       0  5201.1    0.08       0  5238.0    0.14       0
#XS Ineff=2,0
    0.00 4855.00  833.76 5145.00    0.00  834.56
Permanent Ineff=
       F       F
Bank Sta=4983.5,5016.5
XS Rating Curve= 0
Exp/Cntr=0.5,0.3

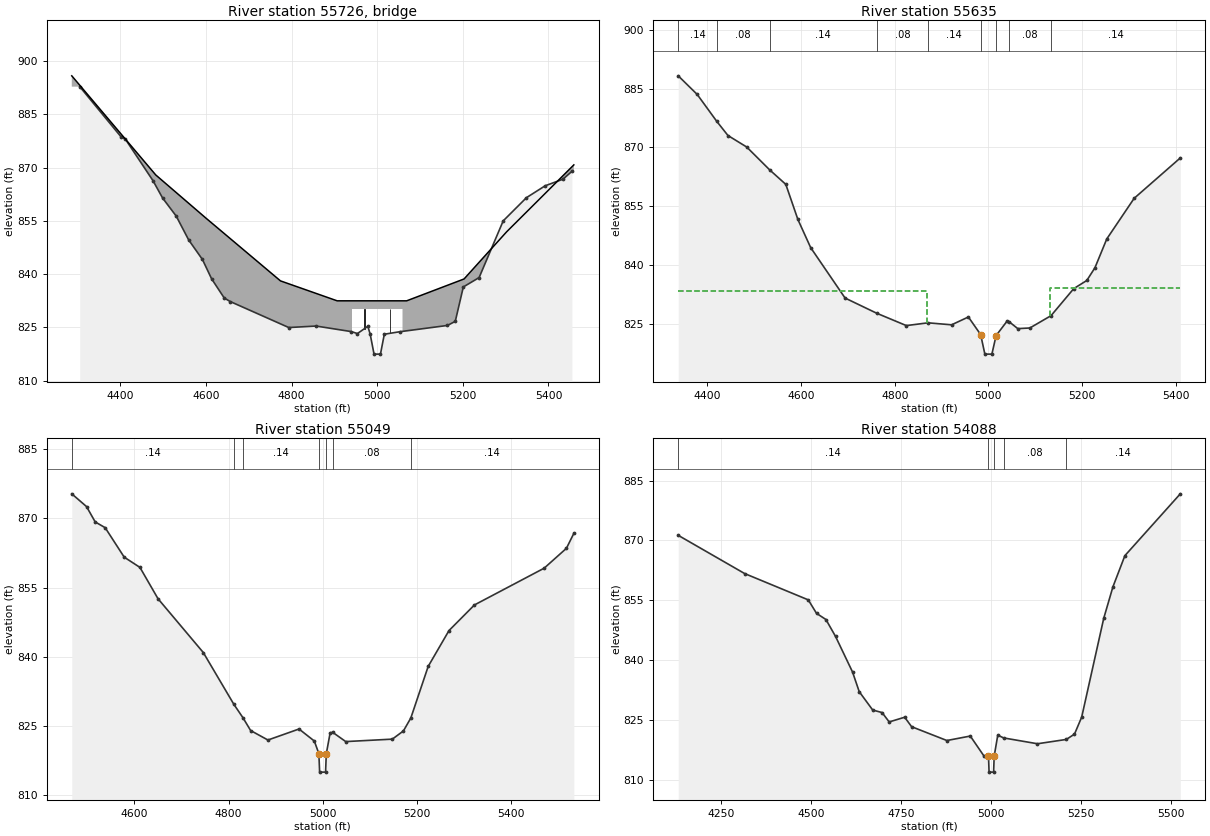
Type RM Length L Ch R =3,55726,,,
BEGIN DESCRIPTION:
Union Cross Church Road  FC - TOR
Structure ID: LDS_FC_08
Approximate Survey Structure
END DESCRIPTION:
Bridge Culvert--1,0,-1,-1,0
Deck Dist Width WeirC Skew NumUp NumDn MinLoCord MaxHiCord MaxSubmerge Is_Ogee
86,36,3,,13,13,,,0.95,0,1,1,,,
  4286.3  4482.5  4599.4  4773.9  4906.3  4941.0  4941.0  5059.0  5059.0  5068.7
  5202.8  5302.2  5459.3
  895.81  867.92  855.81  838.11  832.50  832.50  832.50  832.50  832.50  832.50
  838.65  851.91  870.75
  797.50  797.50  797.50  797.50  797.50  797.50  830.20  830.20  797.50  797.50
  797.50  797.50  797.50
  4286.3  4482.5  4599.4  4773.9  4906.3  4941.0  4941.0  5059.0  5059.0  5068.7
  5202.8  5302.2  5459.3
  895.81  867.92  855.81  838.11  832.50  832.50  832.50  832.50  832.50  832.50
  838.65  851.91  870.75
  797.50  797.50  797.50  797.50  797.50  797.50  830.20  830.20  797.50  797.50
  797.50  797.50  797.50
Pier Skew, UpSta & Num, DnSta & Num=,4970.5,2,4970.5,2,0,0,0,0,0
       1       1
  824.85  830.20
       1       1
  824.38  830.20
Pier Skew, UpSta & Num, DnSta & Num=,5029.5,2,5029.5,2,0,0,0,0,0
       1       1
  823.47  830.20
       1       1
  823.31  830.20
Abutment Skew #Up #Dn=,2,2
  4941.0  4957.0
  830.20  823.63
  4941.0  4957.0
  830.20  826.72
Abutment Skew #Up #Dn=,2,2
  5043.0  5059.0
  823.85  830.20
  5043.0  5059.0
  825.63  830.20
BR Coef=1,1,0,1.25,0,,,0.8,0,2,0,
WSPro=,,,, 1 ,,,, 0 ,,,, 0 ,,,,-1 ,-1 ,-1 , 0 , 0 , 0 , 0 , 0
BC Design=,,0,,0,,,,,,

Type RM Length L Ch R = 1,55635,586,586,586
BEGIN DESCRIPTION:
Union Church Road  FC - ds
END DESCRIPTION:
XS GIS Cut Line= 3
      1522969.53       881358.18      1522834.67       880994.04
      1522749.25       880315.21
#Sta/Elev= 30
  4337.5  888.27  4378.1  883.51  4419.7  876.67  4443.7  873.04  4483.8  870.10
  4532.9  864.26  4567.3  860.57  4593.1  851.61  4620.4  844.43  4693.9  831.56
  4761.4  827.69  4824.8  824.53  4871.0  825.24  4921.4  824.73  4957.3  826.73
  4983.5  822.24  4992.5  817.25  5007.5  817.25  5016.5  821.98  5040.3  825.73
  5044.4  825.51  5062.8  823.76  5088.6  823.92  5133.9  827.07  5182.4  833.97
  5210.2  836.04  5227.6  839.28  5252.9  846.64  5311.4  857.01  5410.0  867.32
#Mann=9,-1,0
  4337.5    0.14       0  4419.7    0.08       0  4532.9    0.14       0
  4761.4    0.08       0  4871.0    0.14       0  4983.5    0.05       0
  5016.5    0.14       0  5044.4    0.08       0  5133.9    0.14       0
#XS Ineff=2,0
    0.00 4868.00  833.41 5132.00    0.00  834.05
Permanent Ineff=
       F       F
Bank Sta=4983.5,5016.5
XS Rating Curve= 0
Exp/Cntr=0.5,0.3

Type RM Length L Ch R = 1,55049,961,961,961
BEGIN DESCRIPTION:
Forbush Creek - 55.0
END DESCRIPTION:
XS GIS Cut Line= 2
      1523414.61       881137.91      1523234.77       880085.87
#Sta/Elev= 30
  4466.8  875.35  4498.2  872.58  4516.6  869.25  4537.8  868.00  4578.3  861.60
  4611.7  859.38  4650.2  852.57  4746.4  840.90  4811.3  829.67  4831.0  826.70
  4847.0  823.97  4883.8  821.91  4949.9  824.30  4982.4  821.69  4992.1  818.94
  4993.7  814.94  5006.3  814.94  5007.9  818.94  5016.1  823.49  5021.6  823.57
  5049.2  821.57  5148.2  822.10  5171.8  823.88  5187.6  826.70  5224.5  837.90
  5268.7  845.67  5322.8  851.23  5471.0  859.21  5518.3  863.52  5534.1  866.77
#Mann=7,-1,0
  4466.8    0.14       0  4811.3    0.08       0  4831.0    0.14       0
  4992.1    0.05       0  5007.9    0.14       0  5021.6    0.08       0
  5187.6    0.14       0
Bank Sta=4992.1,5007.9
XS Rating Curve= 0
Exp/Cntr=0.3,0.1

Type RM Length L Ch R = 1,54088,1267,1267,1267
BEGIN DESCRIPTION:
Forbush Creek - 54.0
END DESCRIPTION:
XS GIS Cut Line= 3
      1524556.52       881106.46      1524417.14       880634.39
      1523837.18       879942.02
#Sta/Elev= 30
  4129.8  871.28  4314.3  861.72  4491.2  855.13  4514.1  851.76  4540.3  850.21
  4567.0  845.98  4614.2  837.08  4632.8  832.16  4670.3  827.56  4696.3  826.93
  4716.1  824.58  4759.1  825.76  4778.4  823.39  4876.4  819.93  4941.5  821.05
  4980.2  815.96  4992.1  816.02  4993.7  812.02  5006.3  812.02  5007.9  816.02
  5017.9  821.28  5034.1  820.58  5128.2  819.12  5208.3  820.20  5231.1  821.53
  5251.1  825.79  5312.4  850.52  5337.9  858.39  5371.2  866.20  5525.2  881.67
#Mann=5,-1,0
  4129.8    0.14       0  4992.1    0.05       0  5007.9    0.14       0
  5034.1    0.08       0  5208.3    0.14       0
Bank Sta=4992.1,5007.9
XS Rating Curve= 0
Exp/Cntr=0.3,0.1