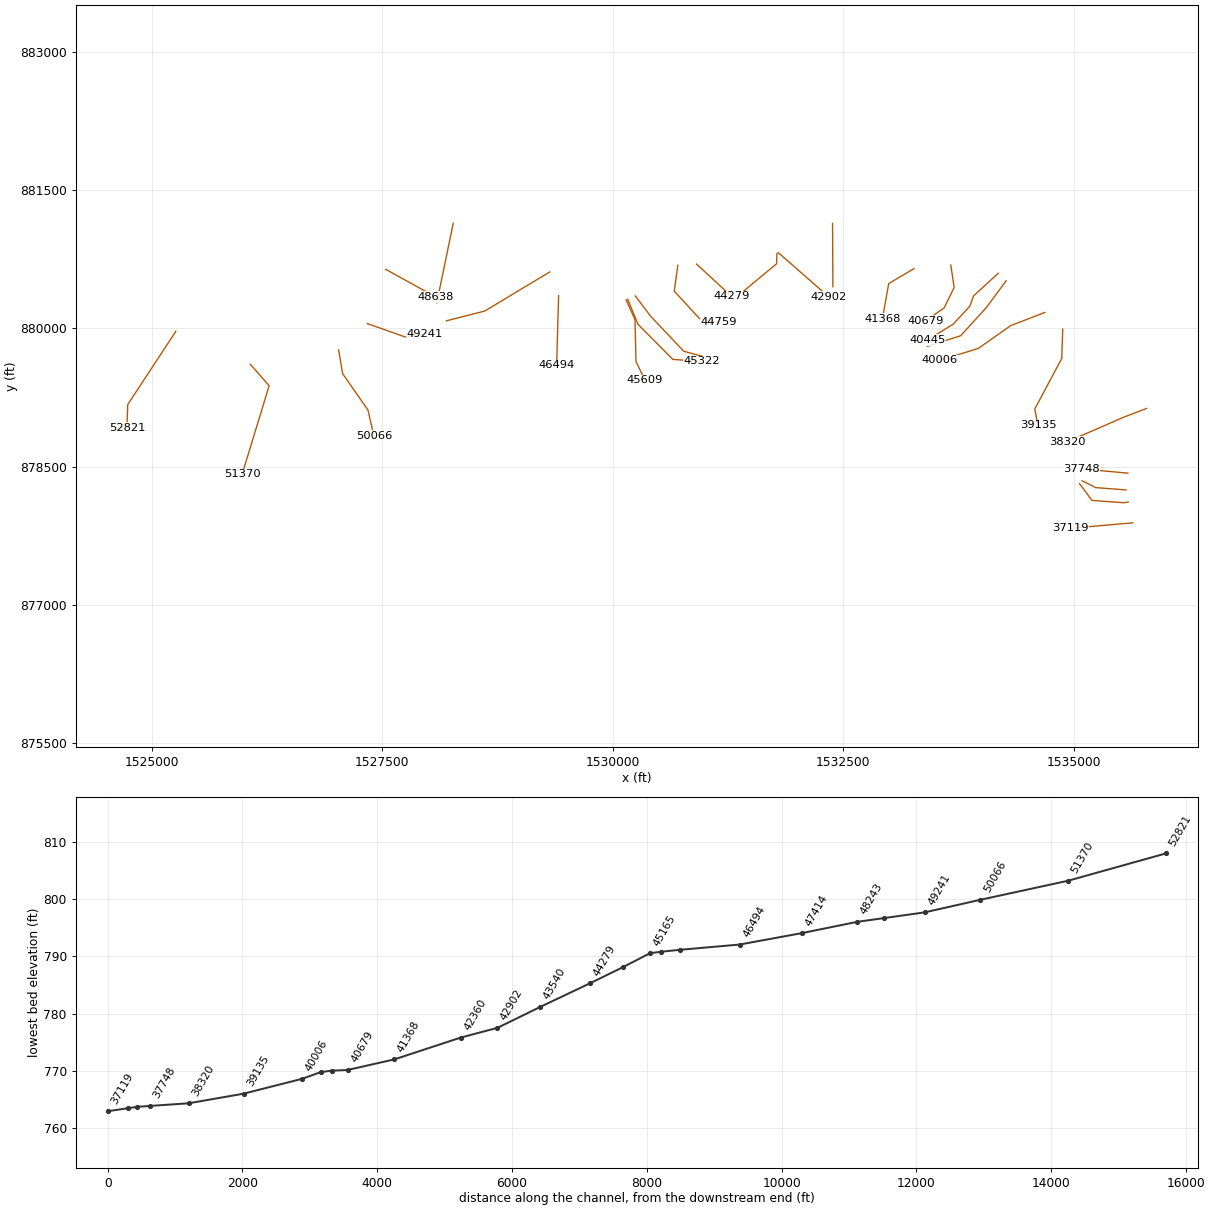
HEC-RAS study Forbush Creek.prj: Forbush Creek Limited Detail Study

--- Forbush Creek.g01 (geometry) --- (continued)

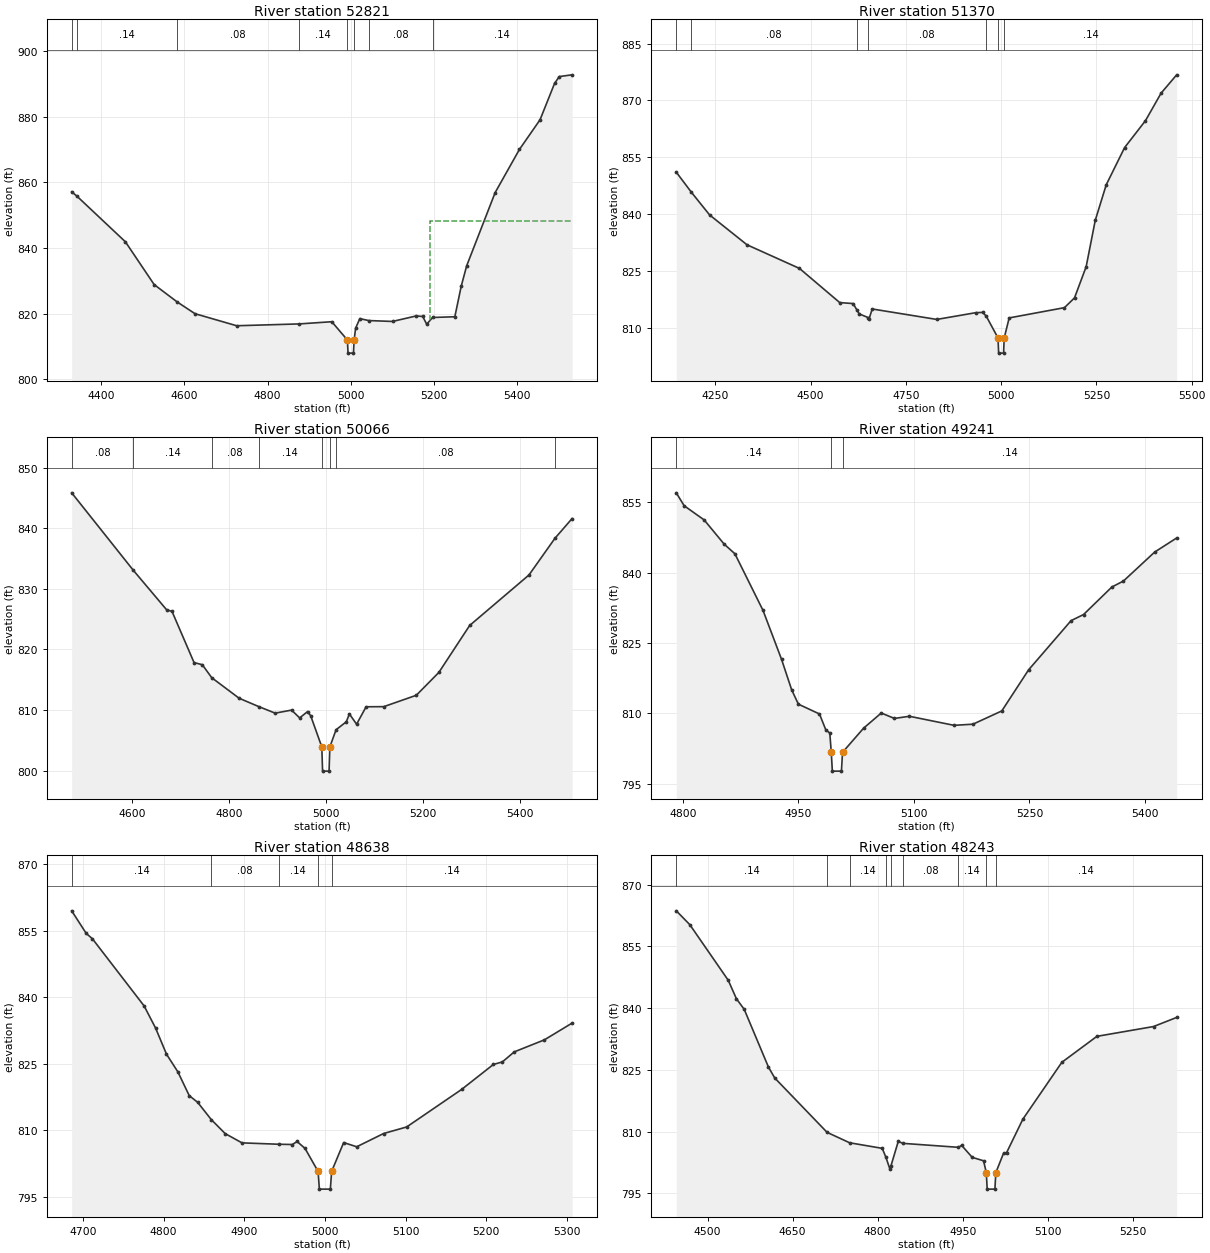
Type RM Length L Ch R = 1,52821,1451,1451,1451
BEGIN DESCRIPTION:
Forbush Creek - 53.0
END DESCRIPTION:
XS GIS Cut Line= 3
      1525262.34       879969.03      1524740.83       879173.29
      1524731.84       878921.56
#Sta/Elev= 30
  4328.9  857.17  4341.7  855.81  4458.1  841.93  4527.3  828.89  4582.5  823.62
  4625.5  820.03  4725.7  816.36  4876.3  816.92  4954.4  817.59  4991.9  812.02
  4993.5  808.02  5006.5  808.02  5008.1  812.02  5011.7  815.63  5021.8  818.53
  5043.4  817.94  5100.4  817.67  5157.4  819.35  5173.1  819.18  5182.6  816.83
  5196.9  818.88  5250.3  819.10  5265.6  828.39  5278.8  834.64  5347.3  856.95
  5405.6  870.07  5455.2  879.11  5490.1  890.18  5501.5  892.27  5532.2  892.80
#Mann=8,-1,0
  4328.9    0.08       0  4341.7    0.14       0  4582.5    0.08       0
  4876.3    0.14       0  4991.9    0.05       0  5008.1    0.14       0
  5043.4    0.08       0  5196.9    0.14       0
#XS Ineff=2,0
       0                 5190.00    0.00  848.29
Permanent Ineff=
       F       F
Bank Sta=4991.9,5008.1
XS Rating Curve= 0
Exp/Cntr=0.3,0.1

Type RM Length L Ch R = 1,51370,1304,1304,1304
BEGIN DESCRIPTION:
Forbush Creek - 52.0
END DESCRIPTION:
XS GIS Cut Line= 3
      1526071.23       879610.30      1526274.77       879378.18
      1525981.91       878417.45
#Sta/Elev= 30
  4147.6  851.03  4187.5  845.69  4235.1  839.73  4333.2  831.85  4470.9  825.61
  4576.5  816.59  4611.6  816.33  4621.0  814.74  4627.7  813.60  4651.1  812.63
  4653.5  812.29  4661.8  814.90  4831.1  812.14  4933.5  813.92  4951.7  814.00
  4961.0  813.00  4991.9  807.24  4993.5  803.24  5006.5  803.24  5008.1  807.24
  5021.2  812.54  5166.2  815.25  5192.6  817.83  5223.2  826.07  5247.1  838.33
  5275.9  847.71  5324.1  857.53  5378.8  864.63  5419.9  871.91  5460.7  876.74
#Mann=7,-1,0
  4147.6    0.14       0  4187.5    0.08       0  4621.0    0.14       0
  4651.1    0.08       0  4961.0    0.14       0  4991.9    0.05       0
  5008.1    0.14       0
Bank Sta=4991.9,5008.1
XS Rating Curve= 0
Exp/Cntr=0.3,0.1

Type RM Length L Ch R = 1,50066,825,825,825
BEGIN DESCRIPTION:
Forbush Creek - 51.0
END DESCRIPTION:
XS GIS Cut Line= 4
      1527028.35       879767.43      1527071.20       879510.33
      1527346.20       879113.90      1527410.48       878831.76
#Sta/Elev= 30
  4475.6  845.87  4602.6  833.09  4671.6  826.54  4682.6  826.29  4728.1  817.83
  4745.1  817.48  4764.6  815.33  4821.1  811.94  4861.3  810.57  4895.4  809.48
  4929.4  809.98  4946.0  808.69  4962.2  809.73  4968.7  809.06  4991.7  803.90
  4993.3  799.90  5006.7  799.90  5008.3  803.90  5021.2  806.74  5042.3  808.05
  5048.6  809.35  5063.5  807.65  5083.1  810.53  5119.6  810.55  5186.7  812.43
  5233.3  816.21  5296.8  823.96  5419.2  832.30  5472.6  838.34  5508.1  841.62
#Mann=8,-1,0
  4475.6    0.08       0  4602.6    0.14       0  4764.6    0.08       0
  4861.3    0.14       0  4991.7    0.05       0  5008.3    0.14       0
  5021.2    0.08       0  5472.6    0.14       0
Bank Sta=4991.7,5008.3
XS Rating Curve= 0
Exp/Cntr=0.3,0.1

Type RM Length L Ch R = 1,49241,603,603,603
BEGIN DESCRIPTION:
Forbush Creek - 50.0
END DESCRIPTION:
XS GIS Cut Line= 3
      1527339.05       880053.18      1527753.34       879906.75
      1527960.48       879942.47
#Sta/Elev= 30
  4791.5  857.01  4801.7  854.26  4827.7  851.23  4853.7  846.07  4867.6  844.02
  4904.1  831.95  4928.1  821.55  4941.3  815.02  4950.0  811.97  4977.4  809.88
  4985.5  806.54  4990.8  805.80  4992.7  801.70  4994.1  797.70  5005.9  797.70
  5007.3  801.70  5034.7  806.86  5057.6  810.08  5074.7  808.93  5094.1  809.39
  5152.1  807.46  5176.6  807.70  5214.1  810.53  5248.8  819.27  5304.0  829.77
  5320.2  831.07  5357.0  836.94  5372.0  838.21  5412.5  844.38  5441.1  847.39
#Mann=3,-1,0
  4791.5    0.14       0  4992.7    0.05       0  5007.3    0.14       0
Bank Sta=4992.7,5007.3
XS Rating Curve= 0
Exp/Cntr=0.3,0.1

Type RM Length L Ch R = 1,48638,395,395,395
BEGIN DESCRIPTION:
Forbush Creek - 49.0
END DESCRIPTION:
XS GIS Cut Line= 2
      1527539.09       880642.45      1528081.91       880342.47
#Sta/Elev= 30
  4686.2  859.51  4704.2  854.42  4711.9  853.20  4776.0  838.04  4790.3  833.01
  4803.7  827.16  4817.8  823.17  4831.9  817.80  4842.3  816.30  4859.2  812.40
  4876.4  809.24  4897.3  807.14  4942.7  806.83  4959.8  806.77  4965.6  807.45
  4975.4  805.89  4991.6  800.70  4993.2  796.70  5006.8  796.70  5008.4  800.70
  5023.3  807.21  5039.5  806.26  5072.8  809.25  5101.4  810.73  5169.5  819.20
  5208.9  824.84  5220.0  825.41  5234.8  827.68  5272.2  830.40  5306.4  834.17
#Mann=5,-1,0
  4686.2    0.14       0  4859.2    0.08       0  4942.7    0.14       0
  4991.6    0.05       0  5008.4    0.14       0
Bank Sta=4991.6,5008.4
XS Rating Curve= 0
Exp/Cntr=0.3,0.1

Type RM Length L Ch R = 1,48243,829,829,829
BEGIN DESCRIPTION:
Forbush Creek - 48.0
END DESCRIPTION:
XS GIS Cut Line= 2
      1528271.20       881142.50      1528092.62       880278.15
#Sta/Elev= 30
  4444.8  863.61  4468.6  860.26  4536.5  846.74  4550.7  842.31  4564.7  839.67
  4607.4  825.67  4618.4  823.04  4710.8  809.83  4750.6  807.30  4808.1  805.95
  4814.6  803.76  4821.3  801.04  4823.6  801.77  4836.3  807.62  4844.8  807.16
  4942.4  806.20  4948.1  806.67  4966.8  803.76  4986.8  802.93  4991.6  800.05
  4993.2  796.05  5006.8  796.05  5008.4  800.05  5022.0  804.74  5027.4  804.90
  5056.1  813.03  5124.9  826.84  5186.7  833.14  5286.6  835.52  5327.4  837.73
#Mann=9,-1,0
  4444.8    0.14       0  4710.8    0.08       0  4750.6    0.14       0
  4814.6    0.05       0  4823.6    0.11       0  4844.8    0.08       0
  4942.4    0.14       0  4991.6    0.05       0  5008.4    0.14       0
Bank Sta=4991.6,5008.4
XS Rating Curve= 0
Exp/Cntr=0.3,0.1

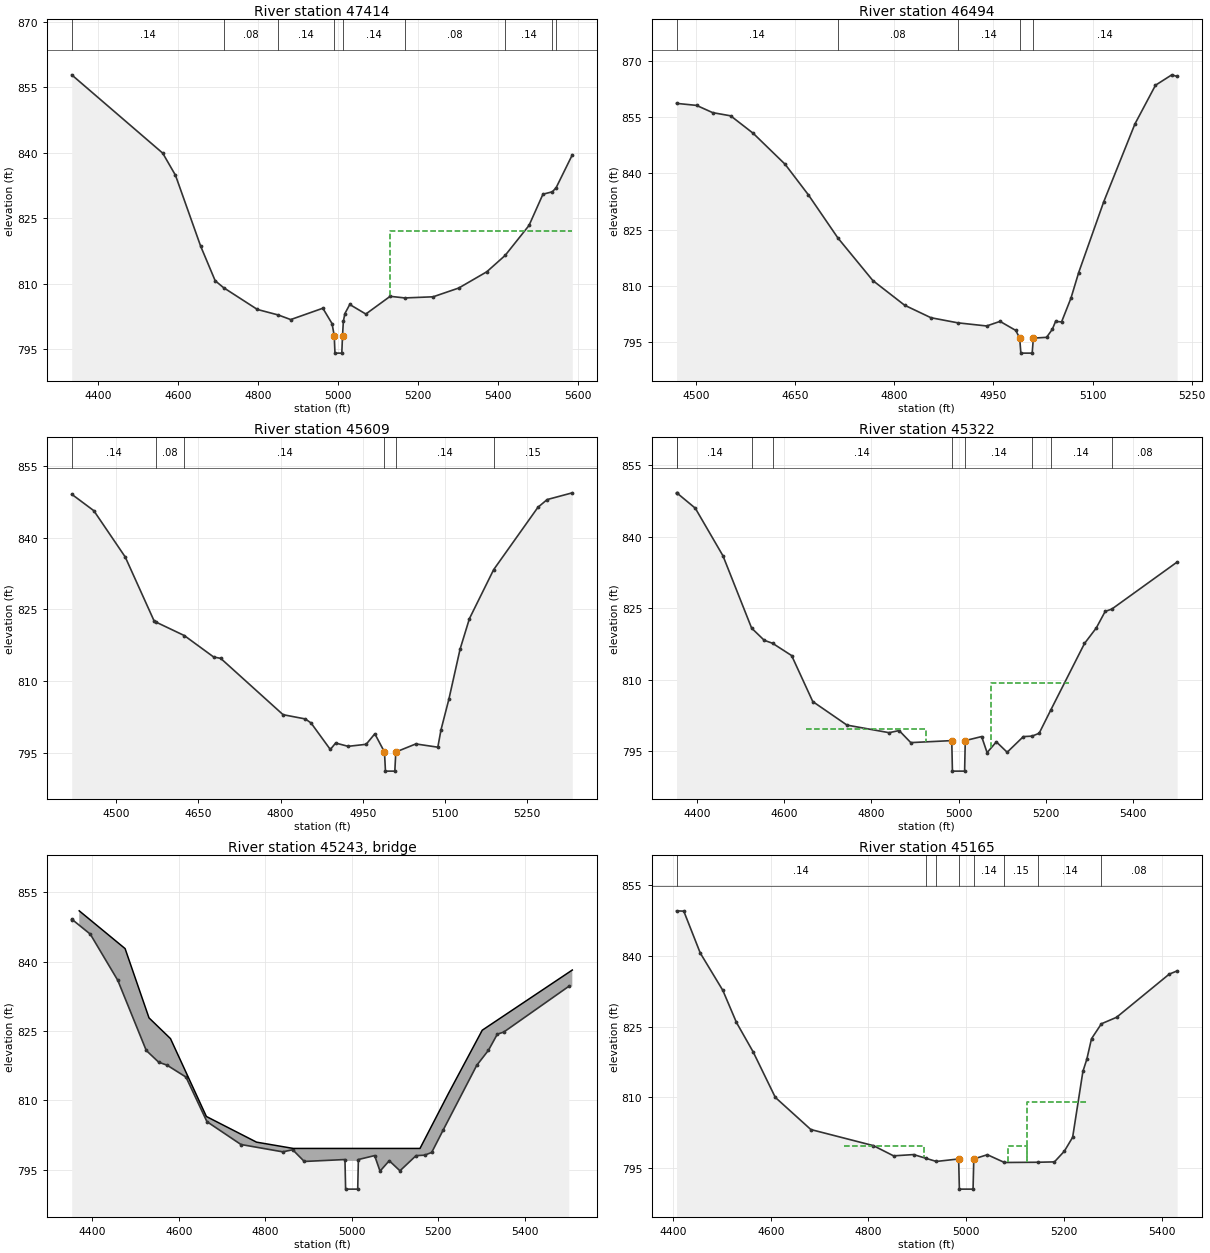
Type RM Length L Ch R = 1,47414,920,920,920
BEGIN DESCRIPTION:
Forbush Creek - 47.0
END DESCRIPTION:
XS GIS Cut Line= 3
      1529317.62       880613.90      1528612.57       880189.28
      1528197.06       880083.52
#Sta/Elev= 30
  4333.2  857.85  4560.8  839.90  4592.7  834.83  4655.7  818.57  4692.0  810.65
  4712.9  809.07  4797.5  804.07  4849.9  802.80  4880.9  801.75  4961.2  804.35
  4984.2  800.83  4989.7  798.06  4991.5  794.06  5008.6  794.06  5010.4  798.06
  5012.5  801.34  5016.3  803.12  5028.5  805.21  5068.7  803.02  5129.5  807.08
  5166.3  806.71  5236.9  806.97  5301.0  808.98  5371.2  812.71  5417.1  816.46
  5476.7  823.32  5511.6  830.49  5535.2  831.04  5544.6  831.99  5585.0  839.51
#Mann=9,-1,0
  4333.2    0.14       0  4712.9    0.08       0  4849.9    0.14       0
  4989.7    0.05       0  5010.4    0.14       0  5166.3    0.08       0
  5417.1    0.14       0  5535.2    0.08       0  5544.6    0.14       0
#XS Ineff=2,0
       0                 5129.50    0.00  822.06
Permanent Ineff=
       F       F
Bank Sta=4989.7,5010.4
XS Rating Curve= 0
Exp/Cntr=0.3,0.1

Type RM Length L Ch R = 1,46494,885,885,885
BEGIN DESCRIPTION:
Forbush Creek - 46.0
END DESCRIPTION:
XS GIS Cut Line= 2
      1529414.05       880356.79      1529392.62       879599.59
#Sta/Elev= 30
  4470.5  858.64  4500.8  858.10  4525.2  856.17  4552.4  855.32  4586.5  850.66
  4634.7  842.42  4669.9  834.28  4714.7  822.75  4767.5  811.42  4815.6  804.84
  4855.4  801.51  4895.9  800.15  4939.7  799.31  4960.0  800.53  4983.8  798.12
  4989.7  796.07  4991.5  792.07  5008.6  792.07  5010.4  796.07  5030.4  796.28
  5039.0  798.40  5044.0  800.51  5053.1  800.40  5067.3  806.73  5079.0  813.56
  5116.8  832.37  5164.1  853.16  5195.2  863.48  5219.9  866.25  5228.0  865.81
#Mann=5,-1,0
  4470.5    0.14       0  4714.7    0.08       0  4895.9    0.14       0
  4989.7    0.05       0  5010.4    0.14       0
Bank Sta=4989.7,5010.4
XS Rating Curve= 0
Exp/Cntr=0.3,0.1

Type RM Length L Ch R = 1,45609,287,287,287
BEGIN DESCRIPTION:
Forbush Creek - 45.0
END DESCRIPTION:
XS GIS Cut Line= 4
      1530146.18       880310.33      1530242.61       880096.04
      1530253.33       879642.47      1530349.74       879438.93
#Sta/Elev= 30
  4418.7  849.10  4459.1  845.65  4516.4  835.97  4569.6  822.47  4572.0  822.37
  4624.3  819.52  4677.9  815.03  4690.7  814.75  4804.6  802.96  4845.2  802.07
  4855.7  801.22  4890.8  795.68  4900.6  797.03  4923.3  796.34  4956.2  796.76
  4972.1  798.96  4989.7  795.15  4991.5  791.15  5008.6  791.15  5010.4  795.15
  5046.9  796.84  5087.1  796.16  5092.9  799.80  5107.4  806.26  5127.7  816.67
  5144.8  823.07  5189.0  833.31  5269.9  846.37  5286.7  847.98  5332.6  849.39
#Mann=6,-1,0
  4418.7    0.14       0  4572.0    0.08       0  4624.3    0.14       0
  4989.7    0.05       0  5010.4    0.14       0  5189.0    0.15       0
Bank Sta=4989.7,5010.4
XS Rating Curve= 0
Exp/Cntr=0.5,0.3

Type RM Length L Ch R = 1,45322,157,157,157
BEGIN DESCRIPTION:
Lace Knoll Road  FC - us
END DESCRIPTION:
XS GIS Cut Line= 4
      1530164.04       880317.47      1530274.76       880046.04
      1530653.33       879663.90      1530971.16       879642.47
#Sta/Elev= 30
  4352.5  849.16  4353.9  849.09  4395.5  845.94  4459.1  835.95  4524.9  820.79
  4553.8  818.24  4573.0  817.61  4616.8  815.03  4665.3  805.39  4743.9  800.45
  4840.7  798.86  4863.6  799.31  4890.4  796.78  4984.5  797.20  4986.0  790.80
  5014.0  790.80  5015.5  797.20  5053.1  798.05  5065.6  794.68  5086.9  796.94
  5111.7  794.76  5148.9  798.04  5168.7  798.14  5185.1  798.73  5212.0  803.64
  5289.3  817.57  5316.4  820.83  5336.9  824.31  5351.7  824.76  5502.1  834.65
#Mann=9,-1,0
  4352.5    0.08       0  4353.9    0.14       0  4524.9    0.08       0
  4573.0    0.14       0  4984.5    0.05       0  5015.5    0.14       0
  5168.7    0.08       0  5212.0    0.14       0  5351.7    0.08       0
#XS Ineff=2,-1
 4650.00 4925.00  799.57 5075.00 5253.10  809.35
Permanent Ineff=
       F       F
Bank Sta=4984.5,5015.5
XS Rating Curve= 0
Exp/Cntr=0.5,0.3

Type RM Length L Ch R =3,45243,,,
BEGIN DESCRIPTION:
Lace Knoll Road  FC - TOR
Structure ID: LDS_FC_07
Approximate Survey Structure
END DESCRIPTION:
Bridge Culvert--1,0,-1,-1,0
Deck Dist Width WeirC Skew NumUp NumDn MinLoCord MaxHiCord MaxSubmerge Is_Ogee
66,26,3,,15,15,,,0.95,0,1,1,,,
  4369.9  4476.0  4531.3  4581.0  4664.0  4780.0  4865.1  4978.5  4978.5  5021.5
  5021.5  5158.0  5224.0  5302.0  5510.3
  850.99  842.82  827.84  823.35  806.51  800.96  799.60  799.60  799.60  799.60
  799.60  799.60  811.52  825.17  838.19
  770.80  770.80  770.80  770.80  770.80  770.80  770.80  770.80  796.90  796.90
  770.80  770.80  770.80  770.80  770.80
  4369.9  4476.0  4531.3  4581.0  4664.0  4780.0  4865.1  4978.5  4978.5  5021.5
  5021.5  5158.0  5224.0  5302.0  5510.3
  850.99  842.82  827.84  823.35  806.51  800.96  799.60  799.60  799.60  799.60
  799.60  799.60  811.52  825.17  838.19
  770.80  770.80  770.80  770.80  770.80  770.80  770.80  770.80  796.90  796.90
  770.80  770.80  770.80  770.80  770.80
Abutment Skew #Up #Dn=,2,2
  4978.5  4984.5
  796.90  797.20
  4978.5  4984.5
  796.90  796.95
Abutment Skew #Up #Dn=,2,2
  5015.5  5021.5
  797.20  796.90
  5015.5  5021.5
  796.95  796.90
BR Coef=1,1,0,1.25,0,,,0.8,0,2,0,
WSPro=,,,, 1 ,,,, 0 ,,,, 0 ,,,,-1 ,-1 ,-1 , 0 , 0 , 0 , 0 , 0
BC Design=,,0,,0,,,,,,

Type RM Length L Ch R = 1,45165,406,406,406
BEGIN DESCRIPTION:
Lace Knoll Road  FC - ds
END DESCRIPTION:
XS GIS Cut Line= 4
      1530246.20       880353.16      1530410.47       880135.32
      1530771.18       879753.18      1530989.05       879692.47
#Sta/Elev= 30
  4407.2  849.58  4422.0  849.51  4455.8  840.61  4501.9  832.71  4529.8  825.90
  4564.0  819.65  4609.3  810.01  4682.0  803.19  4809.9  799.78  4851.3  797.61
  4892.4  797.88  4917.1  797.10  4938.8  796.42  4984.5  796.95  4986.0  790.55
  5014.0  790.55  5015.5  796.95  5043.3  797.85  5078.2  796.20  5146.1  796.25
  5180.6  796.33  5200.9  798.61  5217.8  801.55  5238.8  815.52  5246.8  818.10
  5256.4  822.45  5276.6  825.62  5307.6  826.99  5415.4  836.15  5431.7  836.84
#Mann=8,-1,0
  4407.2    0.14       0  4917.1    0.08       0  4938.8    0.14       0
  4984.5    0.05       0  5015.5    0.14       0  5078.2    0.15       0
  5146.1    0.14       0  5276.6    0.08       0
#XS Ineff=3,-1
 4750.10 4913.50  799.60 5086.50 5125.00  799.60 5125.10 5247.70  808.96
Permanent Ineff=
       F       F       F
Bank Sta=4984.5,5015.5
XS Rating Curve= 0
Exp/Cntr=0.5,0.3

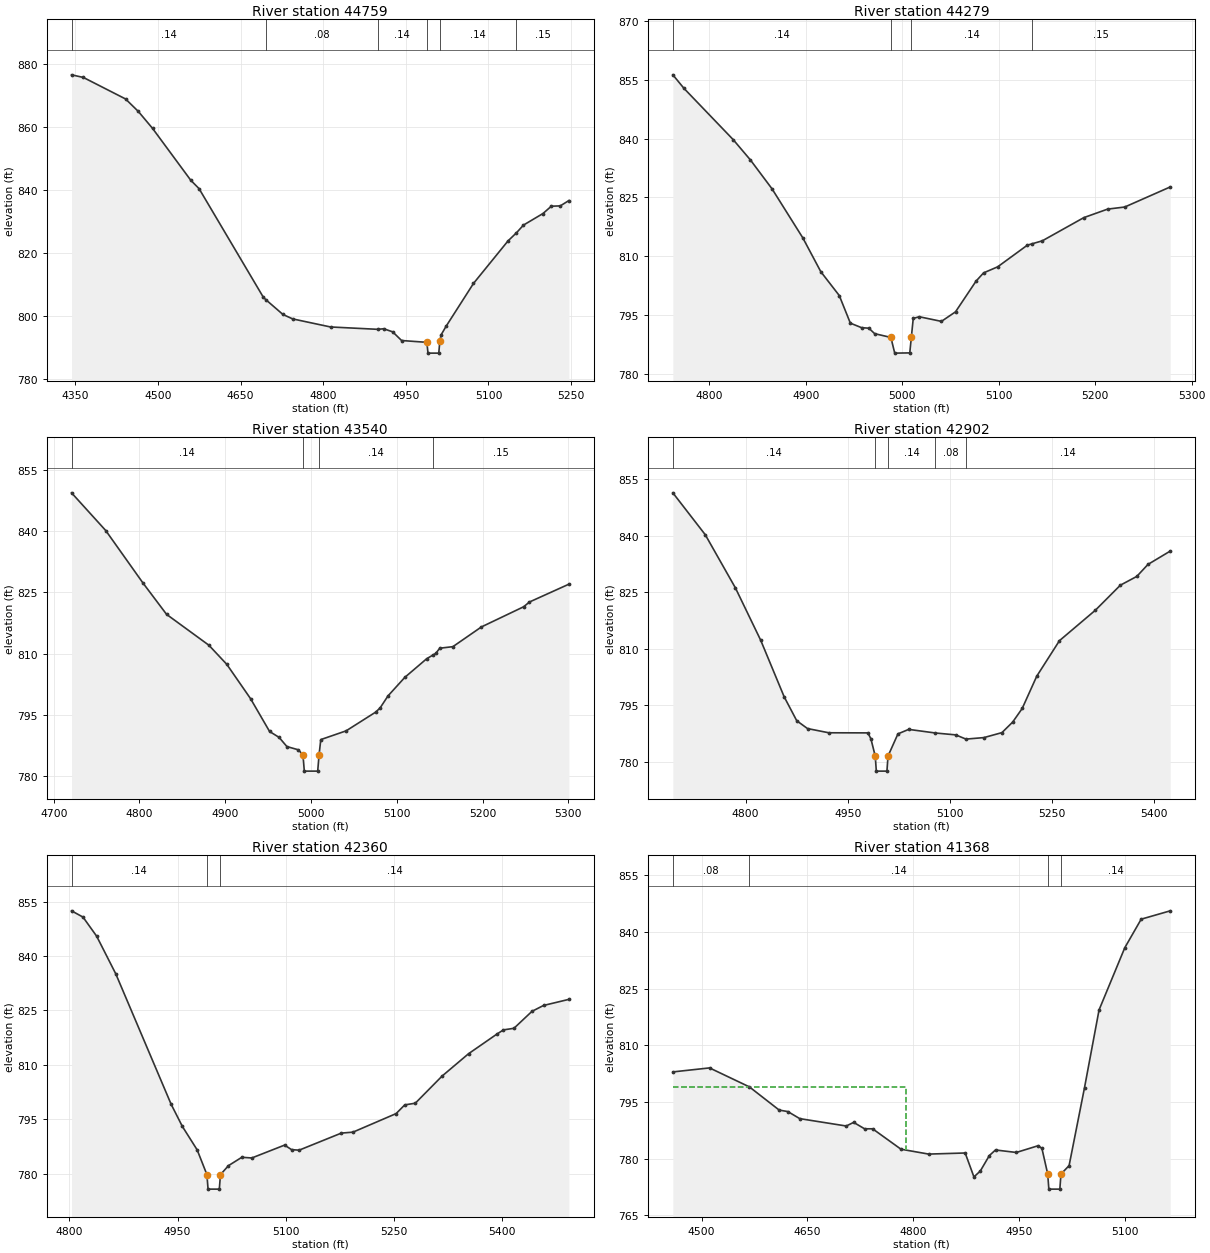
Type RM Length L Ch R = 1,44759,480,480,480
BEGIN DESCRIPTION:
Forbush Creek - 44.0
END DESCRIPTION:
XS GIS Cut Line= 5
      1530706.90       880685.37      1530671.18       880424.61
      1530667.61       880406.75      1530942.61       880106.75
      1531153.30       880067.47
#Sta/Elev= 30
  4343.3  876.59  4364.7  875.76  4441.3  868.92  4464.5  864.95  4490.4  859.54
  4559.7  843.06  4574.8  840.38  4691.5  805.82  4696.6  804.97  4727.0  800.37
  4744.7  798.96  4813.3  796.40  4899.0  795.65  4909.9  795.83  4926.1  794.85
  4942.3  792.09  4988.2  791.51  4990.2  788.08  5009.8  788.08  5011.8  792.08
  5014.3  793.98  5023.0  796.60  5072.8  810.25  5135.5  823.78  5150.7  826.33
  5163.5  828.80  5198.9  832.48  5214.1  834.81  5230.3  834.91  5246.0  836.61
#Mann=6,-1,0
  4343.3    0.14       0  4696.6    0.08       0  4899.0    0.14       0
  4988.2    0.05       0  5011.8    0.14       0  5150.7    0.15       0
Bank Sta=4988.2,5011.8
XS Rating Curve= 0
Exp/Cntr=0.3,0.1

Type RM Length L Ch R = 1,44279,739,739,739
BEGIN DESCRIPTION:
Forbush Creek - 43.0
END DESCRIPTION:
XS GIS Cut Line= 2
      1530910.44       880699.63      1531289.04       880349.61
#Sta/Elev= 30
  4762.2  856.23  4773.8  852.76  4824.8  839.70  4842.6  834.54  4865.0  827.18
  4896.9  814.69  4915.6  806.05  4934.7  799.99  4946.2  792.95  4957.8  791.80
  4965.4  791.66  4971.4  790.27  4988.2  789.31  4992.2  785.31  5007.8  785.37
  5009.4  789.31  5011.4  794.17  5017.7  794.58  5040.6  793.40  5055.2  795.83
  5076.5  803.66  5084.3  805.76  5098.9  807.30  5129.6  812.81  5134.7  813.18
  5145.2  813.93  5188.2  819.84  5212.9  822.01  5230.6  822.54  5277.8  827.66
#Mann=4,-1,0
  4762.2    0.14       0  4988.2    0.05       0  5009.4    0.14       0
  5134.7    0.15       0
Bank Sta=4988.2,5009.4
XS Rating Curve= 0
Exp/Cntr=0.3,0.1

Type RM Length L Ch R = 1,43540,638,638,638
BEGIN DESCRIPTION:
Forbush Creek - 42.0
END DESCRIPTION:
XS GIS Cut Line= 3
      1531781.89       880813.89      1531778.32       880703.18
      1531417.64       880403.20
#Sta/Elev= 30
  4720.8  849.39  4760.7  840.14  4804.0  827.31  4831.6  819.60  4880.9  812.04
  4901.8  807.35  4929.5  798.94  4951.7  790.89  4962.8  789.44  4971.9  787.19
  4985.2  786.40  4990.6  785.17  4992.2  781.17  5007.8  781.17  5009.4  785.17
  5011.4  788.90  5040.9  791.04  5075.5  795.65  5080.6  796.68  5089.8  799.62
  5109.4  804.16  5134.9  808.73  5141.8  809.58  5145.4  810.02  5150.1  811.30
  5165.4  811.68  5198.7  816.52  5247.9  821.46  5254.7  822.63  5300.7  827.00
#Mann=4,-1,0
  4720.8    0.14       0  4990.6    0.05       0  5009.4    0.14       0
  5141.8    0.15       0
Bank Sta=4990.6,5009.4
XS Rating Curve= 0
Exp/Cntr=0.3,0.1

Type RM Length L Ch R = 1,42902,542,542,542
BEGIN DESCRIPTION:
Forbush Creek - 41.0
END DESCRIPTION:
XS GIS Cut Line= 2
      1531796.18       880824.60      1532346.17       880342.47
#Sta/Elev= 30
  4693.0  851.36  4740.7  840.23  4785.0  826.12  4822.1  812.26  4856.7  797.21
  4875.2  790.86  4891.0  788.79  4922.3  787.67  4979.8  787.64  4984.2  786.08
  4990.6  781.49  4992.2  777.49  5007.8  777.49  5009.4  781.49  5024.0  787.38
  5039.8  788.57  5079.1  787.61  5109.0  787.11  5124.0  785.99  5150.4  786.39
  5176.9  787.71  5192.7  790.51  5206.7  794.12  5228.1  802.69  5261.5  812.12
  5314.3  820.20  5351.1  826.85  5375.2  829.17  5391.6  832.35  5424.4  835.90
#Mann=5,-1,0
  4693.0    0.14       0  4990.6    0.05       0  5009.4    0.14       0
  5079.1    0.08       0  5124.0    0.14       0
Bank Sta=4990.6,5009.4
XS Rating Curve= 0
Exp/Cntr=0.3,0.1

Type RM Length L Ch R = 1,42360,992,992,992
BEGIN DESCRIPTION:
Forbush Creek - 40.0
END DESCRIPTION:
XS GIS Cut Line= 2
      1532385.46       881142.49      1532389.03       880453.20
#Sta/Elev= 30
  4803.0  852.44  4818.9  850.71  4837.8  845.46  4864.3  835.09  4941.1  799.14
  4956.6  793.06  4977.1  786.61  4990.6  779.80  4992.2  775.80  5007.8  775.80
  5009.4  779.80  5020.5  782.27  5039.0  784.57  5052.8  784.38  5098.2  787.92
  5108.0  786.67  5118.4  786.53  5176.9  791.23  5193.0  791.49  5252.8  796.60
  5264.8  799.00  5279.4  799.46  5316.5  806.93  5353.2  813.09  5392.2  818.46
  5401.5  819.65  5416.1  820.09  5441.1  824.76  5457.1  826.38  5492.3  828.06
#Mann=3,-1,0
  4803.0    0.14       0  4990.6    0.05       0  5009.4    0.14       0
Bank Sta=4990.6,5009.4
XS Rating Curve= 0
Exp/Cntr=0.3,0.1

Type RM Length L Ch R = 1,41368,689,689,689
BEGIN DESCRIPTION:
Forbush Creek - 39.0
END DESCRIPTION:
XS GIS Cut Line= 3
      1533267.56       880649.59      1532994.39       880487.70
      1532926.39       880106.15
#Sta/Elev= 30
  4459.2  802.97  4511.2  804.03  4567.7  799.01  4609.9  792.88  4622.3  792.47
  4639.1  790.61  4705.0  788.66  4715.5  789.62  4731.0  787.92  4742.4  787.92
  4782.6  782.52  4821.8  781.23  4873.6  781.52  4886.0  775.19  4895.0  776.74
  4907.9  780.85  4916.6  782.32  4946.1  781.66  4977.3  783.46  4982.4  782.72
  4990.6  775.96  4992.2  771.96  5007.8  771.96  5009.4  775.96  5020.9  778.17
  5042.8  798.84  5063.4  819.38  5099.9  835.84  5123.1  843.38  5164.3  845.59
#Mann=4,-1,0
  4459.2    0.08       0  4567.7    0.14       0  4990.6    0.05       0
  5009.4    0.14       0
#XS Ineff=2,0
    0.00 4790.00  798.85               0
Permanent Ineff=
       F       F
Bank Sta=4990.6,5009.4
XS Rating Curve= 0
Exp/Cntr=0.3,0.1

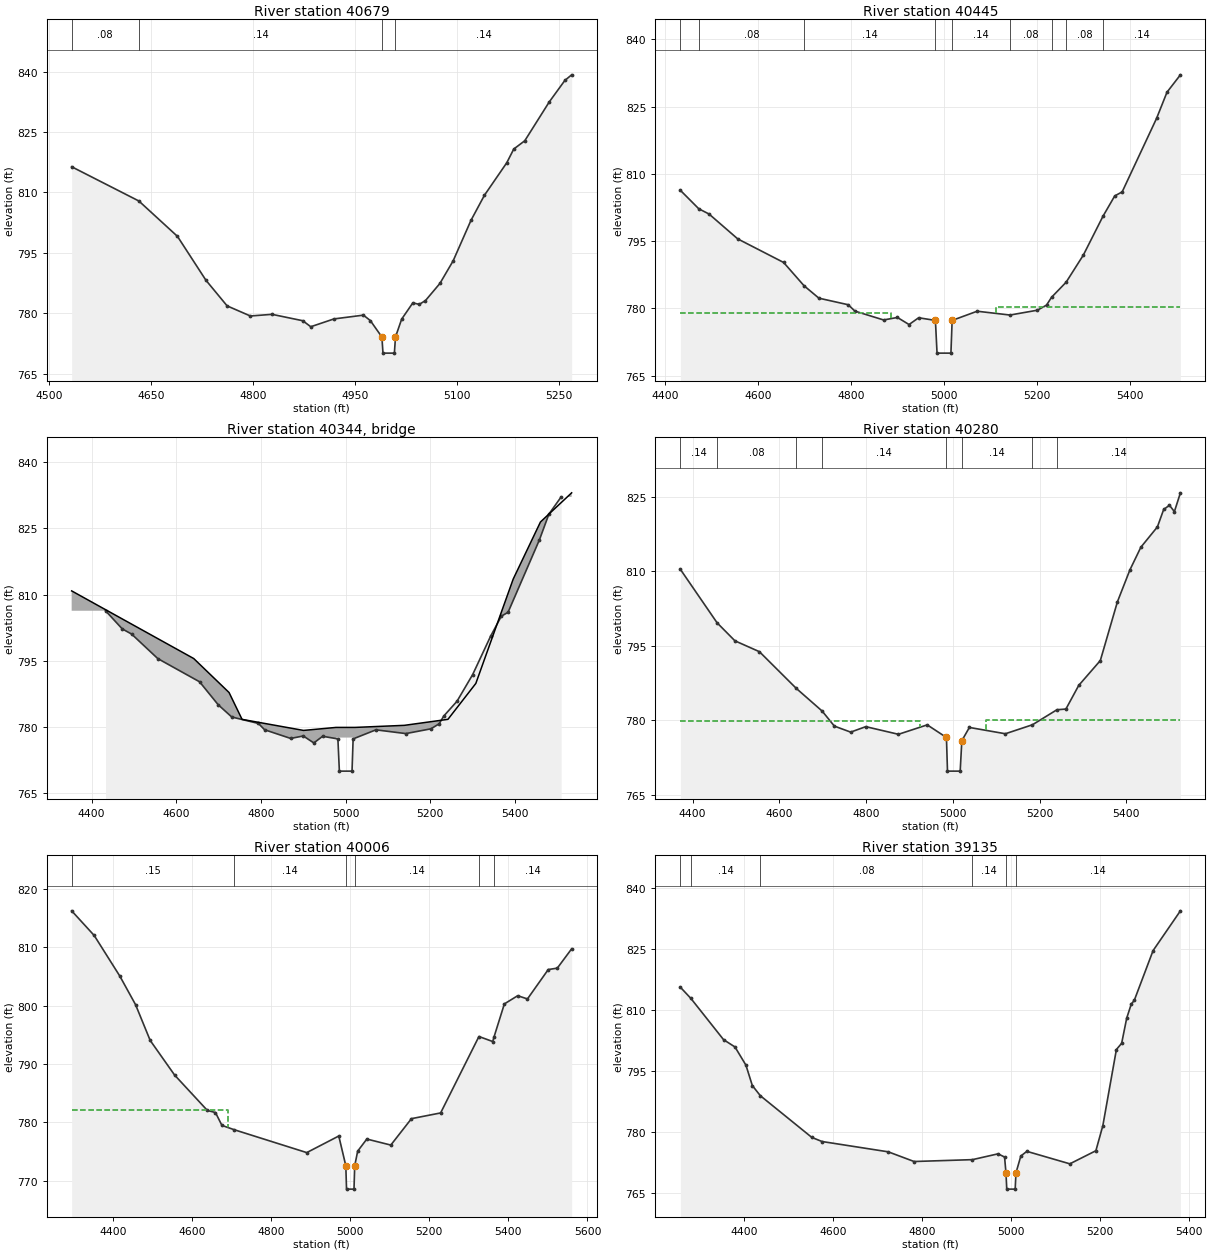
Type RM Length L Ch R = 1,40679,234,234,234
BEGIN DESCRIPTION:
Forbush Creek - 38.0
END DESCRIPTION:
XS GIS Cut Line= 4
      1533667.60       880688.88      1533704.55       880446.15
      1533595.00       880223.28      1533396.14       880085.30
#Sta/Elev= 30
  4533.4  816.39  4632.3  807.89  4689.1  799.11  4731.0  788.22  4762.2  781.85
  4796.4  779.34  4828.3  779.75  4873.6  778.16  4885.3  776.67  4919.4  778.61
  4962.8  779.55  4973.0  778.20  4990.0  774.12  4991.6  770.12  5008.4  770.12
  5010.0  774.12  5019.1  778.56  5035.6  782.61  5044.9  782.22  5054.1  783.16
  5075.4  787.42  5094.9  793.04  5121.2  803.11  5141.0  809.33  5173.8  817.38
  5184.1  820.79  5200.3  822.84  5236.2  832.45  5259.3  837.82  5269.3  839.21
#Mann=4,-1,0
  4533.4    0.08       0  4632.3    0.14       0  4990.0    0.05       0
  5010.0    0.14       0
Bank Sta=4990,5010
XS Rating Curve= 0
Exp/Cntr=0.5,0.3

Type RM Length L Ch R = 1,40445,165,165,165
BEGIN DESCRIPTION:
Hutchins Road  FC - us
END DESCRIPTION:
XS GIS Cut Line= 5
      1534181.91       880599.63      1533914.03       880353.18
      1533874.74       880242.47      1533692.60       880046.04
      1533413.99       879874.59
#Sta/Elev= 30
  4433.0  806.32  4472.5  802.21  4494.6  801.04  4556.4  795.49  4655.2  790.23
  4699.1  785.04  4731.2  782.26  4794.2  780.80  4808.8  779.37  4870.5  777.40
  4900.2  777.96  4925.2  776.38  4945.9  777.89  4982.0  777.30  4985.5  770.00
  5015.4  770.00  5018.0  777.30  5071.9  779.35  5142.6  778.50  5201.7  779.58
  5221.2  780.71  5232.1  782.47  5263.4  785.82  5300.4  791.86  5342.8  800.55
  5368.1  805.08  5384.1  805.98  5458.2  822.39  5480.6  828.22  5509.5  832.10
#Mann=9,-1,0
  4433.0    0.14       0  4472.5    0.08       0  4699.1    0.14       0
  4982.0    0.05       0  5018.0    0.14       0  5142.6    0.08       0
  5232.1    0.14       0  5263.4    0.08       0  5342.8    0.14       0
#XS Ineff=2,0
    0.00 4886.50  779.05 5113.50    0.00  780.26
Permanent Ineff=
       F       F
Bank Sta=4982,5018
XS Rating Curve= 0
Exp/Cntr=0.5,0.3

Type RM Length L Ch R =3,40344,,,
BEGIN DESCRIPTION:
Hutchins Road  FC - TOR
Structure ID: LDS_FC_06
Approximate Survey Structure
END DESCRIPTION:
Bridge Culvert--1,0,-1,-1,0
Deck Dist Width WeirC Skew NumUp NumDn MinLoCord MaxHiCord MaxSubmerge Is_Ogee
91,20,3,,15,15,,,0.95,0,1,1,,,
  4353.0  4641.4  4724.9  4755.6  4900.9  4977.5  4977.5  5022.5  5022.5  5139.1
  5242.0  5307.9  5396.2  5460.6  5534.3
  810.82  795.50  787.80  781.72  779.22  779.90  779.90  779.90  779.90  780.37
  781.73  789.86  813.50  826.43  833.03
  750.00  750.00  750.00  750.00  750.00  750.00  777.60  777.60  750.00  750.00
  750.00  750.00  750.00  750.00  750.00
  4353.0  4641.4  4724.9  4755.6  4900.9  4977.5  4977.5  5022.5  5022.5  5139.1
  5242.0  5307.9  5396.2  5460.6  5534.3
  810.82  795.50  787.80  781.72  779.22  779.90  779.90  779.90  779.90  780.37
  781.73  789.86  813.50  826.43  833.03
  750.00  750.00  750.00  750.00  750.00  750.00  777.60  777.60  750.00  750.00
  750.00  750.00  750.00  750.00  750.00
BR Coef=1,1,0,1.25,0,,,0.8,0,2,0,
WSPro=,,,, 1 ,,,, 0 ,,,, 0 ,,,,-1 ,-1 ,-1 , 0 , 0 , 0 , 0 , 0
BC Design=,,0,,0,,,,,,

Type RM Length L Ch R = 1,40280,274,274,274
BEGIN DESCRIPTION:
Hutchins Road  FC - ds
END DESCRIPTION:
XS GIS Cut Line= 4
      1534267.59       880517.46      1534056.88       880231.75
      1533774.74       879921.04      1533414.01       879806.75
#Sta/Elev= 30
  4371.8  810.34  4456.4  799.59  4497.5  795.97  4554.0  793.78  4639.1  786.39
  4698.6  781.84  4726.8  778.81  4764.4  777.60  4799.3  778.70  4874.6  777.16
  4941.0  779.06  4985.3  776.52  4987.7  769.75  5017.0  769.75  5020.8  775.87
  5038.2  778.54  5121.2  777.27  5183.7  779.08  5240.1  782.10  5260.8  782.24
  5290.4  787.00  5340.2  792.00  5379.6  803.82  5408.5  810.26  5433.7  814.81
  5471.8  818.89  5486.3  822.40  5499.6  823.25  5511.0  821.97  5524.9  825.75
#Mann=8,-1,0
  4371.8    0.14       0  4456.4    0.08       0  4639.1    0.15       0
  4698.6    0.14       0  4985.3    0.05       0  5020.8    0.14       0
  5183.7    0.08       0  5240.1    0.14       0
#XS Ineff=2,0
    0.00 4923.50  779.86 5076.50    0.00  779.97
Permanent Ineff=
       F       F
Bank Sta=4985.3,5020.8
XS Rating Curve= 0
Exp/Cntr=0.5,0.3

Type RM Length L Ch R = 1,40006,871,871,871
BEGIN DESCRIPTION:
Forbush Creek - 37.0
END DESCRIPTION:
XS GIS Cut Line= 4
      1534689.04       880174.62      1534316.49       880030.63
      1533968.97       879785.10      1533549.64       879652.88
#Sta/Elev= 30
  4295.4  816.21  4352.4  811.99  4417.2  805.04  4457.0  800.15  4494.0  794.03
  4555.8  788.10  4638.7  782.04  4659.1  781.69  4675.4  779.49  4706.4  778.75
  4890.0  774.83  4971.0  777.67  4988.8  772.58  4990.6  768.58  5009.5  768.58
  5011.3  772.58  5018.8  775.08  5041.9  777.15  5102.6  776.12  5154.8  780.64
  5228.6  781.62  5325.5  794.70  5360.4  793.84  5363.5  794.59  5389.8  800.28
  5423.5  801.68  5448.2  801.13  5500.8  806.16  5523.7  806.40  5560.0  809.71
#Mann=6,-1,0
  4295.4    0.15       0  4706.4    0.14       0  4988.8    0.05       0
  5011.3    0.14       0  5325.5    0.08       0  5363.5    0.14       0
#XS Ineff=2,0
    0.00 4690.60  782.10               0
Permanent Ineff=
       F       F
Bank Sta=4988.8,5011.3
XS Rating Curve= 0
Exp/Cntr=0.3,0.1

Type RM Length L Ch R = 1,39135,815,815,815
BEGIN DESCRIPTION:
Forbush Creek - 36.0
END DESCRIPTION:
XS GIS Cut Line= 4
      1534881.88       879992.46      1534871.17       879674.61
      1534578.31       879124.61      1534614.02       878946.08
#Sta/Elev= 30
  4257.5  815.60  4281.0  812.86  4354.4  802.72  4380.1  800.92  4404.7  796.44
  4419.0  791.44  4437.0  788.94  4552.6  778.69  4575.5  777.68  4724.4  775.14
  4782.4  772.76  4913.6  773.22  4971.0  774.65  4985.7  773.86  4988.8  769.97
  4990.6  765.97  5009.5  765.97  5011.3  769.97  5022.2  774.11  5035.7  775.26
  5132.3  772.19  5190.8  775.41  5206.4  781.56  5236.9  800.30  5248.7  801.83
  5260.0  807.99  5270.3  811.47  5277.0  812.37  5319.3  824.62  5380.7  834.40
#Mann=6,-1,0
  4257.5    0.15       0  4281.0    0.14       0  4437.0    0.08       0
  4913.6    0.14       0  4988.8    0.05       0  5011.3    0.14       0
Bank Sta=4988.8,5011.3
XS Rating Curve= 0
Exp/Cntr=0.3,0.1

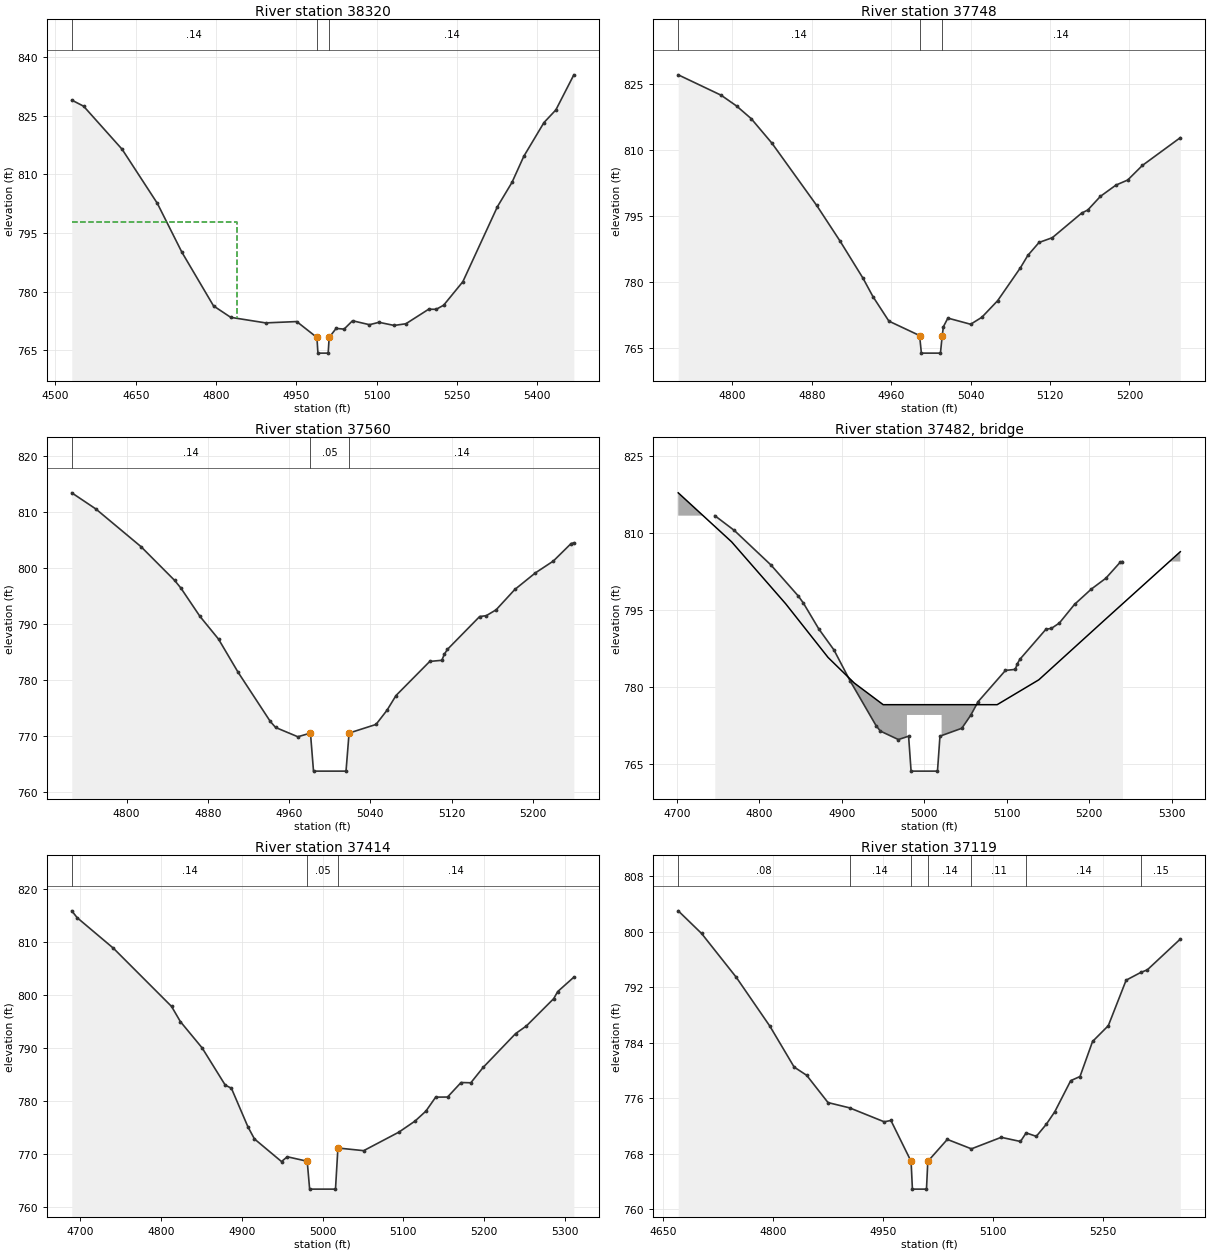
Type RM Length L Ch R = 1,38320,572,572,572
BEGIN DESCRIPTION:
Forbush Creek - 35.0
END DESCRIPTION:
XS GIS Cut Line= 3
      1535792.57       879131.75      1535549.73       879038.90
      1534928.31       878767.47
#Sta/Elev= 30
  4530.5  828.99  4552.7  827.42  4624.7  816.39  4690.4  802.58  4736.3  790.08
  4795.4  776.36  4827.5  773.44  4892.7  772.02  4950.8  772.36  4988.6  768.29
  4990.4  764.29  5009.6  764.29  5011.4  768.29  5024.4  770.61  5039.3  770.43
  5055.1  772.57  5086.7  771.56  5104.6  772.17  5132.8  771.37  5154.8  771.80
  5197.4  775.52  5211.4  775.49  5225.3  776.54  5261.2  782.55  5325.9  801.76
  5353.0  807.94  5375.1  814.62  5412.8  823.25  5435.0  826.48  5468.6  835.45
#Mann=3,-1,0
  4530.5    0.14       0  4988.6    0.05       0  5011.4    0.14       0
#XS Ineff=2,0
    0.00 4840.00  797.76               0
Permanent Ineff=
       F       F
Bank Sta=4988.6,5011.4
XS Rating Curve= 0
Exp/Cntr=0.3,0.1

Type RM Length L Ch R = 1,37748,188,188,188
BEGIN DESCRIPTION:
Forbush Creek - 34.0
END DESCRIPTION:
XS GIS Cut Line= 2
      1535589.01       878428.19      1535085.45       878474.62
#Sta/Elev= 30
  4745.5  827.16  4788.7  822.52  4804.2  820.08  4819.0  817.19  4839.9  811.60
  4885.0  797.43  4908.6  789.29  4931.7  780.84  4941.6  776.70  4957.7  771.11
  4988.6  767.83  4990.4  763.83  5009.6  763.83  5011.4  767.83  5012.6  769.86
  5017.1  771.80  5040.0  770.40  5051.3  771.99  5067.2  775.76  5090.2  783.27
  5097.6  786.06  5108.9  789.01  5122.3  790.10  5151.8  795.69  5158.0  796.40
  5170.8  799.52  5186.4  802.07  5198.2  803.22  5213.0  806.54  5251.2  812.86
#Mann=3,-1,0
  4745.5    0.14       0  4988.6    0.05       0  5011.4    0.14       0
Bank Sta=4988.6,5011.4
XS Rating Curve= 0
Exp/Cntr=0.5,0.3

Type RM Length L Ch R = 1,37560,146,146,146
BEGIN DESCRIPTION:
Private Drive 1  FC - us
END DESCRIPTION:
XS GIS Cut Line= 3
      1535567.64       878246.04      1535239.02       878271.05
      1535092.58       878346.05
#Sta/Elev= 30
  4746.1  813.39  4769.7  810.52  4814.2  803.78  4847.3  797.75  4853.5  796.37
  4872.2  791.33  4890.5  787.26  4909.9  781.30  4941.5  772.54  4946.7  771.47
  4968.6  769.81  4981.0  770.47  4984.0  763.67  5016.0  763.67  5019.0  770.47
  5045.5  772.01  5056.3  774.54  5065.2  777.18  5098.4  783.27  5110.3  783.47
  5112.7  784.54  5115.8  785.42  5147.5  791.29  5154.0  791.44  5163.7  792.49
  5182.1  796.12  5202.3  799.08  5220.0  801.20  5237.5  804.33  5240.2  804.46
#Mann=3,-1,0
  4746.1    0.14       0  4981.0    0.05       0  5019.0    0.14       0
#XS Ineff=2,0
    0.00 4908.00  775.27 5092.00    0.00  776.72
Permanent Ineff=
       F       F
Bank Sta=4981,5019
XS Rating Curve= 0
Exp/Cntr=0.5,0.3

Type RM Length L Ch R =3,37482,,,
BEGIN DESCRIPTION:
Private Drive 1  FC - TOR
Structure ID: LDS_FC_05
Approximate Survey Structure
END DESCRIPTION:
Bridge Culvert--1,0,-1,-1,0
Deck Dist Width WeirC Skew NumUp NumDn MinLoCord MaxHiCord MaxSubmerge Is_Ogee
71,14,3,,14,14,,,0.95,0,1,1,,,
  4701.8  4766.5  4832.0  4883.4  4915.1  4950.2  4979.0  4979.0  5021.0  5021.0
  5088.3  5138.8  5219.0  5310.3
  817.83  808.29  796.24  785.79  780.82  776.60  776.60  776.60  776.60  776.60
  776.60  781.44  793.14  806.37
  743.67  743.67  743.67  743.67  743.67  743.67  743.67  774.60  774.60  743.67
  743.67  743.67  743.67  743.67
  4701.8  4766.5  4832.0  4883.4  4915.1  4950.2  4979.0  4979.0  5021.0  5021.0
  5088.3  5138.8  5219.0  5310.3
  817.83  808.29  796.24  785.79  780.82  776.60  776.60  776.60  776.60  776.60
  776.60  781.44  793.14  806.37
  743.67  743.67  743.67  743.67  743.67  743.67  743.67  774.60  774.60  743.67
  743.67  743.67  743.67  743.67
BR Coef=1,1,0,1.25,0,,,0.8,0,2,0,
WSPro=,,,, 1 ,,,, 0 ,,,, 0 ,,,,-1 ,-1 ,-1 , 0 , 0 , 0 , 0 , 0
BC Design=,,0,,0,,,,,,

Type RM Length L Ch R = 1,37414,295,295,295
BEGIN DESCRIPTION:
Private Drive 1  FC - ds
END DESCRIPTION:
XS GIS Cut Line= 4
      1535592.60       878113.91      1535542.59       878106.76
      1535199.74       878131.76      1535064.04       878313.88
#Sta/Elev= 30
  4689.6  815.94  4696.3  814.64  4741.2  808.87  4813.1  797.90  4824.0  795.04
  4851.0  790.06  4879.5  783.06  4887.2  782.45  4907.7  775.15  4915.7  772.89
  4949.2  768.62  4956.3  769.53  4981.0  768.68  4984.0  763.42  5016.0  763.42
  5019.0  771.18  5050.9  770.68  5094.5  774.18  5114.5  776.27  5127.9  778.14
  5140.0  780.78  5154.7  780.80  5171.4  783.54  5183.5  783.49  5198.7  786.38
  5238.9  792.77  5252.3  794.22  5286.1  799.37  5291.0  800.70  5311.0  803.42
#Mann=3,-1,0
  4689.6    0.14       0  4981.0    0.05       0  5019.0    0.14       0
#XS Ineff=2,0
    0.00 4918.00  771.69 5082.00    0.00  771.46
Permanent Ineff=
       F       F
Bank Sta=4981,5019
XS Rating Curve= 0
Exp/Cntr=0.5,0.3

Type RM Length L Ch R = 1,37119,883,883,883
BEGIN DESCRIPTION:
Forbush Creek - 33.0
END DESCRIPTION:
XS GIS Cut Line= 2
      1535642.58       877888.90      1534960.48       877828.19
#Sta/Elev= 30
  4671.0  803.03  4702.8  799.77  4750.2  793.44  4796.1  786.38  4829.1  780.50
  4846.2  779.31  4875.3  775.38  4904.7  774.62  4951.9  772.61  4961.1  772.80
  4988.6  766.90  4990.4  762.90  5009.6  762.90  5011.4  766.90  5038.0  770.07
  5070.9  768.71  5111.5  770.37  5137.8  769.77  5145.5  771.01  5159.4  770.51
  5173.0  772.25  5184.6  774.06  5206.3  778.54  5219.0  779.14  5236.1  784.19
  5257.6  786.47  5281.9  793.03  5301.8  794.14  5310.8  794.52  5355.8  798.96
#Mann=7,-1,0
  4671.0    0.08       0  4904.7    0.14       0  4988.6    0.05       0
  5011.4    0.14       0  5070.9    0.11       0  5145.5    0.14       0
  5301.8    0.15       0
Bank Sta=4988.6,5011.4
XS Rating Curve= 0
Exp/Cntr=0.3,0.1