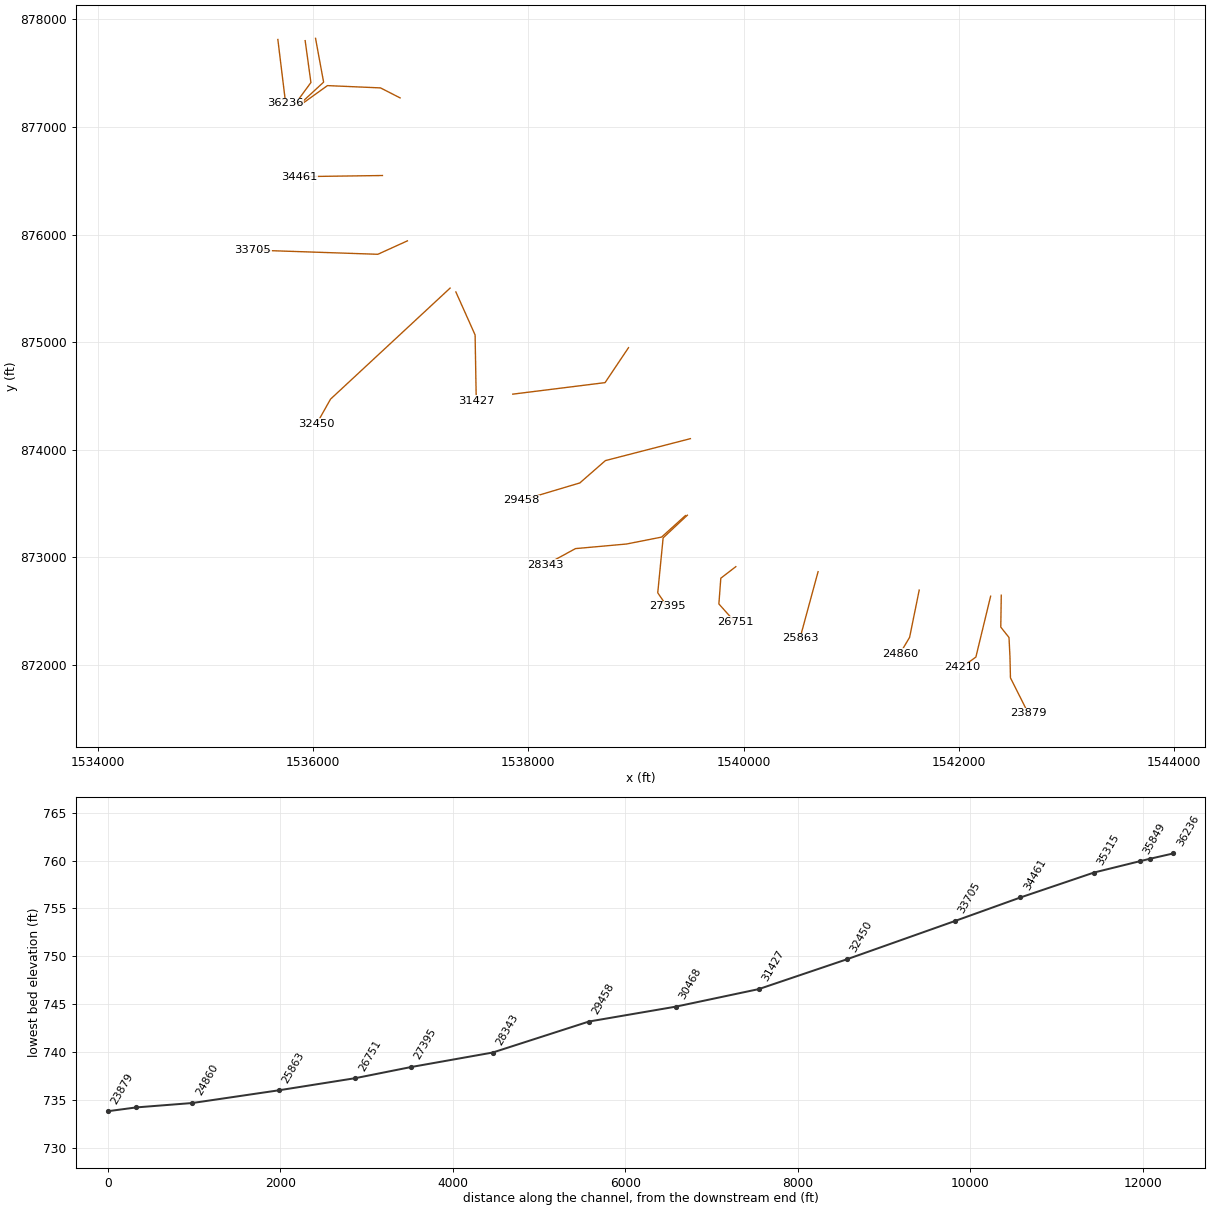
HEC-RAS study Forbush Creek.prj: Forbush Creek Limited Detail Study

--- Forbush Creek.g01 (geometry) --- (continued)

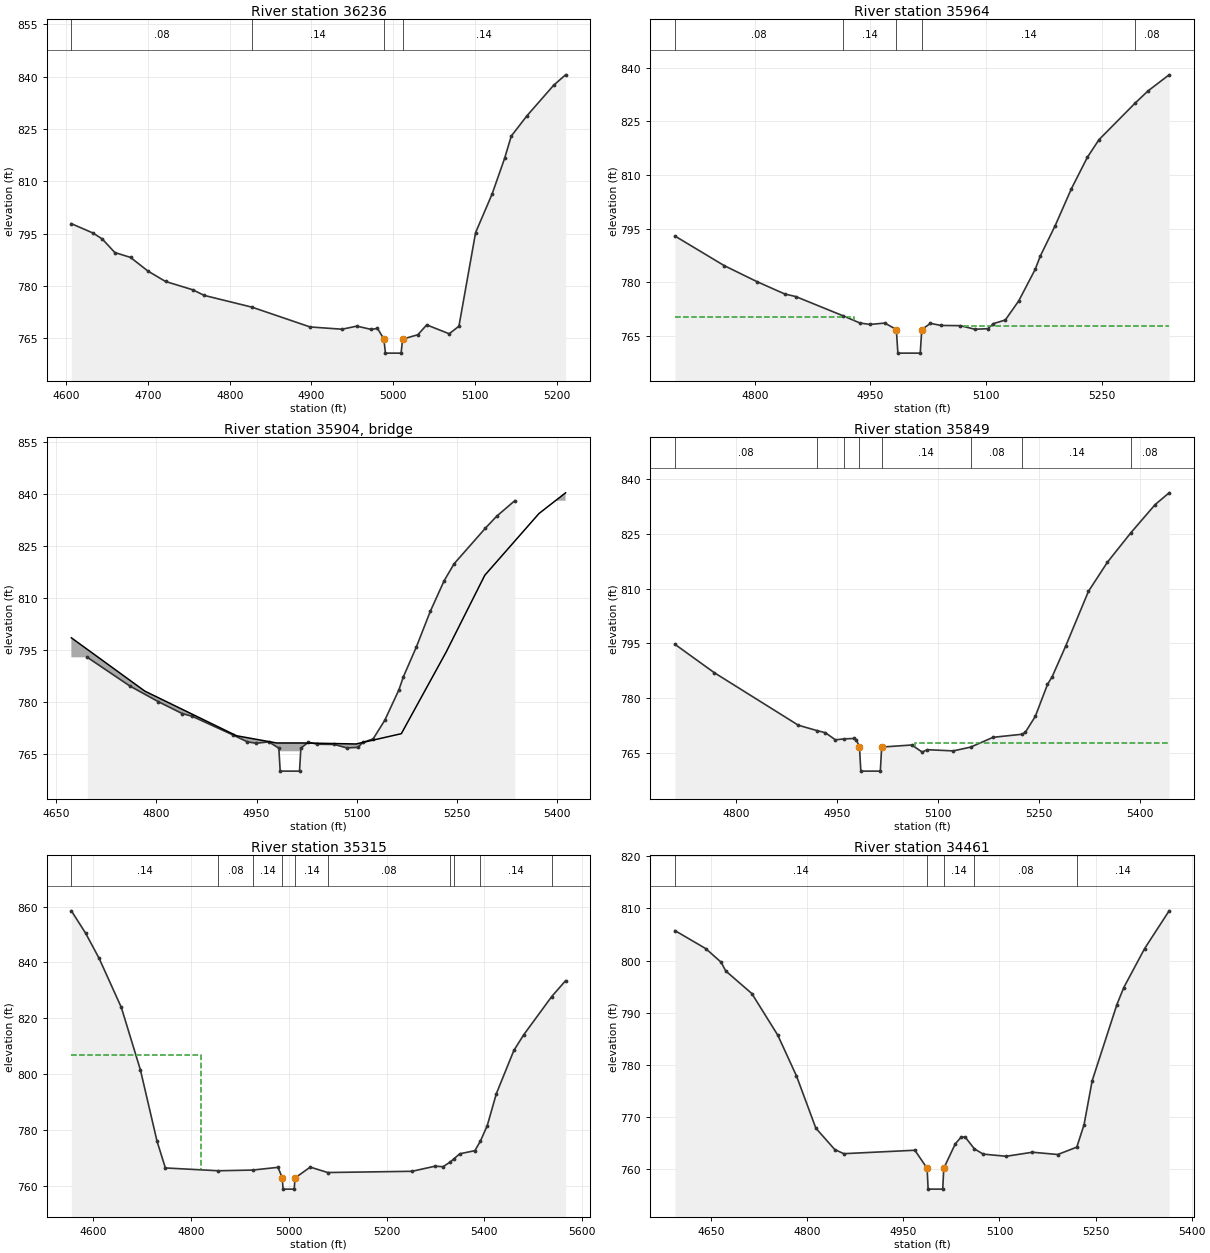
Type RM Length L Ch R = 1,36236,272,272,272
BEGIN DESCRIPTION:
Forbush Creek - 31.0
END DESCRIPTION:
XS GIS Cut Line= 4
      1535674.73       877813.91      1535746.16       877228.19
      1535746.16       877231.76      1535746.16       877221.09
#Sta/Elev= 30
  4606.4  797.86  4633.0  795.16  4644.4  793.42  4659.5  789.59  4678.7  788.19
  4700.2  784.25  4721.5  781.30  4754.7  778.92  4768.9  777.30  4827.3  773.93
  4898.3  768.26  4937.4  767.61  4955.5  768.50  4973.3  767.54  4980.7  767.87
  4988.6  764.76  4990.4  760.76  5009.6  760.76  5011.4  764.76  5030.1  766.04
  5040.9  768.85  5068.4  766.31  5080.3  768.47  5100.7  795.31  5120.9  806.38
  5136.2  816.61  5144.3  822.96  5163.6  828.81  5196.2  837.54  5210.7  840.51
#Mann=4,-1,0
  4606.4    0.08       0  4827.3    0.14       0  4988.6    0.05       0
  5011.4    0.14       0
Bank Sta=4988.6,5011.4
XS Rating Curve= 0
Exp/Cntr=0.5,0.3

Type RM Length L Ch R = 1,35964,115,115,115
BEGIN DESCRIPTION:
Mount Carmel Church Road  FC - us
END DESCRIPTION:
XS GIS Cut Line= 3
      1535928.30       877803.19      1535981.88       877413.91
      1535835.46       877213.93
#Sta/Elev= 30
  4696.4  792.93  4760.3  784.66  4802.6  780.20  4838.8  776.73  4853.1  776.01
  4914.4  770.63  4936.4  768.61  4949.4  768.22  4968.6  768.60  4983.5  766.80
  4985.5  760.20  5014.5  760.20  5016.5  766.80  5027.8  768.52  5041.3  767.94
  5066.6  767.87  5085.4  766.87  5102.1  767.03  5109.3  768.44  5124.8  769.46
  5142.2  774.80  5163.5  783.59  5170.2  787.35  5189.5  795.85  5210.5  806.15
  5231.3  814.97  5246.3  819.86  5293.1  830.07  5310.0  833.51  5337.2  837.98
#Mann=5,-1,0
  4696.4    0.08       0  4914.4    0.14       0  4983.5    0.05       0
  5016.5    0.14       0  5293.1    0.08       0
#XS Ineff=2,0
    0.00 4929.00  770.38 5071.00    0.00  767.76
Permanent Ineff=
       F       F
Bank Sta=4983.5,5016.5
XS Rating Curve= 0
Exp/Cntr=0.5,0.3

Type RM Length L Ch R =3,35904,,,
BEGIN DESCRIPTION:
Mount Carmel Church Road  FC - TOR
Structure ID: LDS_FC_04
Approximate Survey Structure
END DESCRIPTION:
Bridge Culvert--1,0,-1,-1,0
Deck Dist Width WeirC Skew NumUp NumDn MinLoCord MaxHiCord MaxSubmerge Is_Ogee
51,18,3,,13,13,,,0.95,0,1,1,,,
  4672.5  4782.7  4920.0  4980.0  4980.0  5020.0  5020.0  5099.3  5167.1  5234.3
  5292.2  5373.4  5413.3
  798.54  783.20  770.38  768.30  768.30  768.30  768.30  768.01  770.97  794.45
  816.53  834.28  840.24
  740.20  740.20  740.20  740.20  765.90  765.90  740.20  740.20  740.20  740.20
  740.20  740.20  740.20
  4672.5  4782.7  4920.0  4980.0  4980.0  5020.0  5020.0  5099.3  5167.1  5234.3
  5292.2  5373.4  5413.3
  798.54  783.20  770.38  768.30  768.30  768.30  768.30  768.01  770.97  794.45
  816.53  834.28  840.24
  740.20  740.20  740.20  740.20  765.90  765.90  740.20  740.20  740.20  740.20
  740.20  740.20  740.20
BR Coef=1,1,0,1.25,0,,,0.8,-1,2,0,
WSPro=,,,, 1 ,,,, 0 ,,,, 0 ,,,,-1 ,-1 ,-1 , 0 , 0 , 0 , 0 , 0
BC Design=,,0,,0,,,,,,

Type RM Length L Ch R = 1,35849,534,534,534
BEGIN DESCRIPTION:
Mount Carmel Church Road  FC - ds
END DESCRIPTION:
XS GIS Cut Line= 3
      1536024.73       877824.66      1536099.73       877417.48
      1535864.02       877199.62
#Sta/Elev= 30
  4709.0  794.75  4767.4  786.98  4892.6  772.54  4920.8  771.05  4932.9  770.48
  4947.7  768.53  4960.1  768.79  4975.1  768.91  4978.8  768.53  4983.5  766.55
  4985.5  759.95  5014.5  759.95  5016.5  766.55  5061.2  767.12  5076.8  765.18
  5084.4  765.83  5123.0  765.50  5149.0  766.55  5182.2  769.23  5225.9  770.08
  5230.3  770.65  5245.0  774.98  5263.1  783.73  5270.1  785.88  5290.3  794.31
  5324.0  809.27  5352.3  817.29  5387.1  825.35  5423.3  833.10  5444.0  836.31
#Mann=8,-1,0
  4709.0    0.08       0  4920.8    0.08       0  4960.1    0.14       0
  4983.5    0.05       0  5016.5    0.14       0  5149.0    0.08       0
  5225.9    0.14       0  5387.1    0.08       0
#XS Ineff=2,0
    0.00 4934.00  767.00 5066.00    0.00  767.72
Permanent Ineff=
       F       F
Bank Sta=4983.5,5016.5
XS Rating Curve= 0
Exp/Cntr=0.5,0.3

Type RM Length L Ch R = 1,35315,854,854,854
BEGIN DESCRIPTION:
Forbush Creek - 30.0
END DESCRIPTION:
XS GIS Cut Line= 4
      1536810.41       877271.07      1536628.30       877363.91
      1536135.45       877385.34      1535881.90       877203.21
#Sta/Elev= 30
  4556.0  858.49  4585.2  850.45  4612.7  841.46  4658.1  823.86  4697.1  801.46
  4731.1  775.89  4748.1  766.35  4856.3  765.34  4926.2  765.59  4978.3  766.57
  4987.0  762.76  4988.6  758.76  5011.4  758.76  5013.0  762.76  5044.2  766.65
  5079.9  764.71  5252.1  765.15  5299.2  766.98  5315.5  766.80  5330.3  768.50
  5336.9  769.49  5349.7  771.42  5380.7  772.56  5391.9  775.99  5405.8  781.49
  5424.4  792.95  5460.2  808.45  5480.2  814.03  5537.6  827.78  5565.9  833.46
#Mann=10,-1,0
  4556.0    0.14       0  4856.3    0.08       0  4926.2    0.14       0
  4987.0    0.05       0  5013.0    0.14       0  5079.9    0.08       0
  5330.3    0.14       0  5336.9    0.08       0  5391.9    0.14       0
  5537.6    0.08       0
#XS Ineff=2,0
    0.00 4820.00  806.81               0
Permanent Ineff=
       F       F
Bank Sta=4987,5013
XS Rating Curve= 0
Exp/Cntr=0.3,0.1

Type RM Length L Ch R = 1,34461,756,756,756
BEGIN DESCRIPTION:
Forbush Creek - 29.0
END DESCRIPTION:
XS GIS Cut Line= 2
      1536646.13       876549.62      1535874.70       876538.91
#Sta/Elev= 30
  4593.3  805.75  4641.6  802.28  4665.4  799.68  4672.6  798.01  4713.4  793.67
  4753.9  785.68  4783.1  777.86  4813.3  767.85  4842.8  763.75  4856.9  762.95
  4967.9  763.61  4987.0  760.15  4988.6  756.15  5011.4  756.15  5013.0  760.15
  5031.1  764.86  5039.7  766.06  5046.1  766.19  5060.8  763.88  5074.5  762.87
  5110.5  762.45  5151.4  763.23  5191.0  762.79  5220.7  764.21  5232.0  768.51
  5244.7  776.95  5283.3  791.56  5294.0  794.82  5326.6  802.31  5364.8  809.54
#Mann=5,-1,0
  4593.3    0.14       0  4987.0    0.05       0  5013.0    0.14       0
  5060.8    0.08       0  5220.7    0.14       0
Bank Sta=4987,5013
XS Rating Curve= 0
Exp/Cntr=0.3,0.1

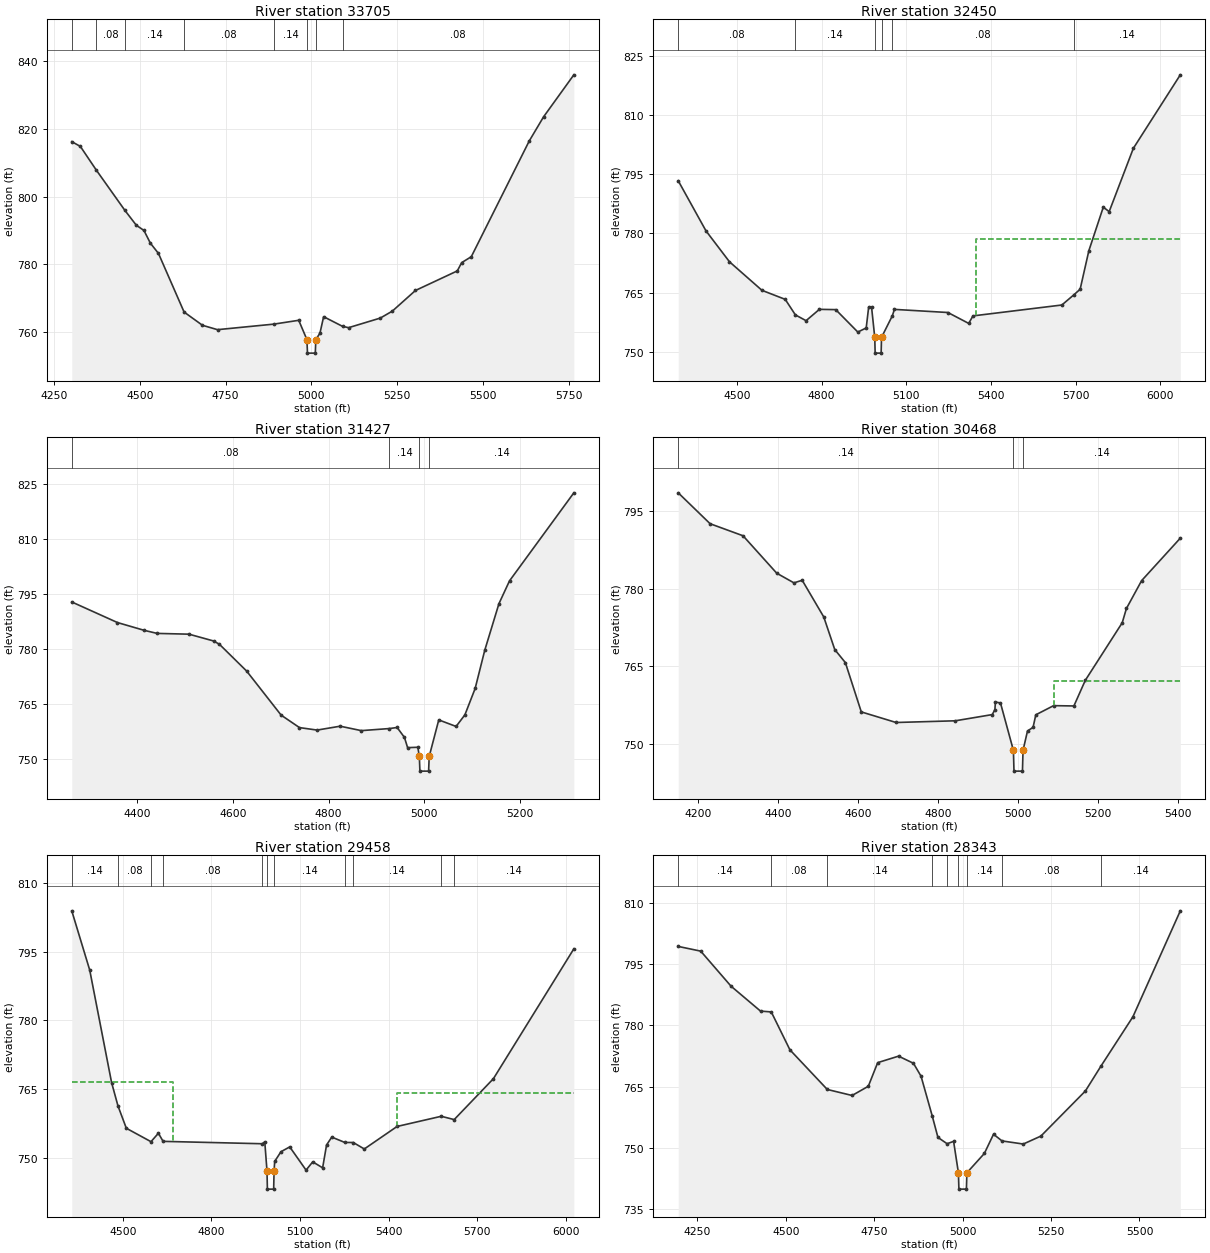
Type RM Length L Ch R = 1,33705,1255,1255,1255
BEGIN DESCRIPTION:
Forbush Creek - 28.0
END DESCRIPTION:
XS GIS Cut Line= 3
      1536878.30       875942.48      1536603.30       875817.48
      1535442.64       875856.77
#Sta/Elev= 30
  4301.6  816.25  4326.6  814.85  4373.1  807.84  4456.6  795.90  4489.8  791.52
  4512.0  789.98  4530.7  786.23  4554.3  783.19  4629.0  765.85  4682.6  761.93
  4726.4  760.64  4890.7  762.28  4963.1  763.41  4987.0  757.70  4988.6  753.70
  5011.4  753.70  5013.0  757.70  5025.0  759.61  5035.7  764.48  5090.8  761.62
  5108.4  761.23  5200.9  764.07  5236.0  766.13  5303.3  772.23  5425.3  778.02
  5438.1  780.47  5466.1  782.22  5635.0  816.46  5676.8  823.60  5765.0  836.02
#Mann=8,-1,0
  4301.6    0.14       0  4373.1    0.08       0  4456.6    0.14       0
  4629.0    0.08       0  4890.7    0.14       0  4987.0    0.05       0
  5013.0    0.14       0  5090.8    0.08       0
Bank Sta=4987,5013
XS Rating Curve= 0
Exp/Cntr=0.3,0.1

Type RM Length L Ch R = 1,32450,1023,1023,1023
BEGIN DESCRIPTION:
Forbush Creek - 27.0
END DESCRIPTION:
XS GIS Cut Line= 3
      1537274.70       875503.17      1536164.02       874471.06
      1536035.47       874242.53
#Sta/Elev= 30
  4291.9  793.35  4390.2  780.66  4473.4  772.83  4588.4  765.60  4670.9  763.31
  4706.9  759.37  4744.7  757.91  4791.9  760.78  4849.7  760.71  4928.0  755.03
  4957.7  756.07  4966.4  761.35  4976.7  761.33  4988.0  753.69  4989.4  749.69
  5010.6  749.69  5012.0  753.69  5050.3  759.15  5057.6  760.77  5247.1  759.98
  5320.8  757.22  5335.8  759.12  5650.7  761.88  5693.9  764.50  5715.5  765.88
  5746.4  775.65  5797.5  786.67  5818.3  785.53  5904.0  801.58  6070.3  820.19
#Mann=6,-1,0
  4291.9    0.08       0  4706.9    0.14       0  4988.0    0.05       0
  5012.0    0.14       0  5050.3    0.08       0  5693.9    0.14       0
#XS Ineff=2,0
       0                 5345.00    0.00  778.68
Permanent Ineff=
       F       F
Bank Sta=4988,5012
XS Rating Curve= 0
Exp/Cntr=0.3,0.1

Type RM Length L Ch R = 1,31427,959,959,959
BEGIN DESCRIPTION:
Forbush Creek - 26.0
END DESCRIPTION:
XS GIS Cut Line= 3
      1537328.30       875467.49      1537506.87       875067.49
      1537517.58       874456.73
#Sta/Elev= 30
  4263.6  792.73  4359.1  787.11  4415.1  784.98  4442.0  784.15  4508.5  783.94
  4559.7  782.09  4572.0  781.19  4628.9  773.88  4701.0  761.85  4739.3  758.45
  4776.1  757.77  4824.3  758.83  4868.5  757.62  4927.3  758.19  4943.3  758.48
  4958.6  755.77  4965.2  752.98  4986.6  753.08  4989.7  750.57  4990.9  746.57
  5009.1  746.57  5010.3  750.57  5030.3  760.55  5066.5  758.76  5084.9  761.93
  5106.3  769.12  5126.4  779.56  5156.0  792.26  5178.1  798.49  5312.5  822.51
#Mann=4,-1,0
  4263.6    0.08       0  4927.3    0.14       0  4989.7    0.05       0
  5010.3    0.14       0
Bank Sta=4989.7,5010.3
XS Rating Curve= 0
Exp/Cntr=0.3,0.1

Type RM Length L Ch R = 1,30468,1010,1010,1010
BEGIN DESCRIPTION:
Forbush Creek - 25.0
END DESCRIPTION:
XS GIS Cut Line= 3
      1538931.87       874949.64      1538714.01       874624.63
      1537856.85       874517.49
#Sta/Elev= 30
  4150.1  798.59  4229.8  792.61  4312.1  790.28  4396.3  783.04  4439.3  781.17
  4460.0  781.67  4513.9  774.57  4541.4  768.26  4567.9  765.74  4607.7  756.20
  4694.7  754.15  4842.8  754.48  4935.1  755.68  4941.7  756.64  4943.0  758.12
  4955.7  757.92  4988.0  748.74  4989.4  744.74  5010.6  744.74  5012.0  748.74
  5023.2  752.51  5037.1  753.21  5044.0  755.64  5088.5  757.41  5139.2  757.35
  5167.7  762.31  5260.0  773.45  5270.5  776.21  5308.5  781.60  5405.2  789.82
#Mann=3,-1,0
  4150.1    0.14       0  4988.0    0.05       0  5012.0    0.14       0
#XS Ineff=2,0
       0                 5088.70    0.00  762.14
Permanent Ineff=
       F       F
Bank Sta=4988,5012
XS Rating Curve= 0
Exp/Cntr=0.3,0.1

Type RM Length L Ch R = 1,29458,1115,1115,1115
BEGIN DESCRIPTION:
Forbush Creek - 24.0
END DESCRIPTION:
XS GIS Cut Line= 4
      1539506.64       874103.83      1538717.20       873899.86
      1538479.22       873692.10      1537935.22       873529.66
#Sta/Elev= 30
  4327.4  803.89  4388.2  790.95  4462.1  766.44  4483.7  761.34  4512.0  756.46
  4595.5  753.53  4620.5  755.37  4636.5  753.60  4972.4  753.08  4980.5  753.50
  4988.0  747.18  4989.4  743.18  5010.6  743.18  5012.0  747.18  5014.1  749.23
  5035.3  751.34  5065.0  752.39  5120.2  747.33  5142.8  749.13  5176.3  747.83
  5189.6  752.81  5207.2  754.53  5251.4  753.36  5280.0  753.35  5317.3  751.94
  5428.2  756.85  5577.7  759.07  5621.5  758.35  5754.3  767.28  6026.4  795.60
#Mann=11,-1,0
  4327.4    0.14       0  4483.7    0.08       0  4595.5    0.14       0
  4636.5    0.08       0  4972.4    0.14       0  4988.0    0.05       0
  5012.0    0.14       0  5251.4    0.08       0  5280.0    0.14       0
  5577.7    0.08       0  5621.5    0.14       0
#XS Ineff=2,0
    0.00 4670.00  766.46 5428.00    0.00  764.25
Permanent Ineff=
       F       F
Bank Sta=4988,5012
XS Rating Curve= 0
Exp/Cntr=0.3,0.1

Type RM Length L Ch R = 1,28343,948,948,948
BEGIN DESCRIPTION:
Forbush Creek - 23.0
END DESCRIPTION:
XS GIS Cut Line= 5
      1539460.41       873388.90      1539239.01       873188.92
      1538914.01       873124.64      1538439.01       873081.78
      1538164.03       872931.79
#Sta/Elev= 30
  4195.7  799.31  4259.3  798.16  4345.1  789.58  4428.4  783.49  4458.8  783.29
  4511.5  774.02  4617.2  764.32  4687.3  762.85  4733.2  765.10  4759.7  770.88
  4818.7  772.47  4860.8  770.73  4882.3  767.57  4914.3  757.74  4930.1  752.59
  4956.0  751.05  4974.4  751.62  4988.0  743.94  4989.4  739.94  5010.6  739.94
  5012.0  743.94  5061.4  748.67  5087.3  753.37  5111.3  751.73  5171.5  750.97
  5221.3  752.92  5347.1  763.95  5391.2  770.05  5481.4  782.09  5615.5  808.02
#Mann=9,-1,0
  4195.7    0.14       0  4458.8    0.08       0  4617.2    0.14       0
  4914.3    0.08       0  4956.0    0.14       0  4988.0    0.05       0
  5012.0    0.14       0  5111.3    0.08       0  5391.2    0.14       0
Bank Sta=4988,5012
XS Rating Curve= 0
Exp/Cntr=0.3,0.1

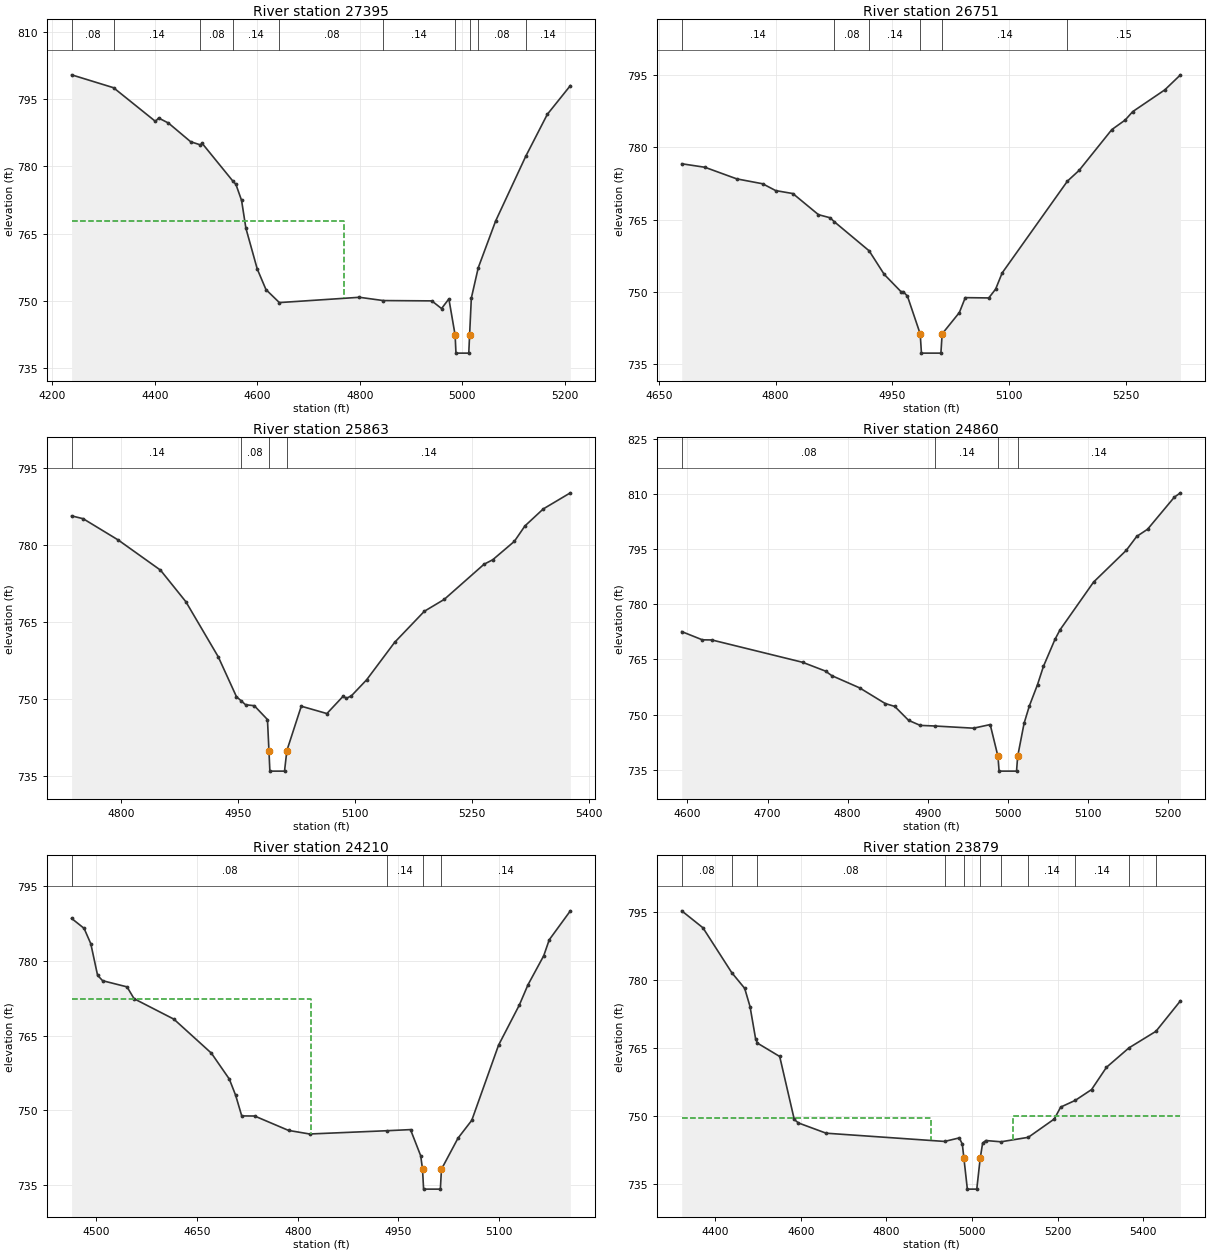
Type RM Length L Ch R = 1,27395,644,644,644
BEGIN DESCRIPTION:
Forbush Creek - 22.0
END DESCRIPTION:
XS GIS Cut Line= 4
      1539478.30       873392.51      1539253.29       873181.78
      1539203.29       872671.07      1539289.01       872546.07
#Sta/Elev= 30
  4237.7  800.37  4319.5  797.50  4401.3  790.00  4407.4  790.76  4426.7  789.63
  4469.9  785.48  4488.8  784.78  4492.6  785.09  4552.7  776.66  4558.2  776.00
  4569.3  772.41  4577.7  766.23  4599.8  757.17  4616.9  752.56  4643.0  749.67
  4799.2  750.85  4845.7  750.12  4940.4  750.05  4959.4  748.34  4973.7  750.49
  4985.9  742.42  4987.5  738.42  5012.5  738.42  5014.1  742.42  5017.5  750.67
  5031.0  757.43  5064.9  767.83  5123.5  782.20  5165.7  791.57  5210.7  797.97
#Mann=10,-1,0
  4237.7    0.08       0  4319.5    0.14       0  4488.8    0.08       0
  4552.7    0.14       0  4643.0    0.08       0  4845.7    0.14       0
  4985.9    0.05       0  5014.1    0.14       0  5031.0    0.08       0
  5123.5    0.14       0
#XS Ineff=2,0
    0.00 4770.00  767.87               0
Permanent Ineff=
       F       F
Bank Sta=4985.9,5014.1
XS Rating Curve= 0
Exp/Cntr=0.3,0.1

Type RM Length L Ch R = 1,26751,888,888,888
BEGIN DESCRIPTION:
Forbush Creek - 21.0
END DESCRIPTION:
XS GIS Cut Line= 4
      1539928.26       872913.91      1539789.00       872806.78
      1539771.15       872567.50      1539921.17       872399.61
#Sta/Elev= 30
  4679.5  776.61  4709.3  775.88  4750.2  773.47  4783.5  772.45  4800.3  771.03
  4822.3  770.42  4855.2  766.03  4870.1  765.39  4875.7  764.54  4920.3  758.52
  4939.7  753.62  4961.5  749.99  4964.1  750.03  4969.5  749.11  4985.9  741.26
  4987.5  737.26  5012.5  737.26  5014.1  741.26  5036.2  745.69  5043.8  748.79
  5074.0  748.73  5082.8  750.56  5091.2  753.92  5175.1  773.01  5190.0  775.22
  5232.1  783.71  5249.2  785.69  5258.9  787.44  5300.2  791.97  5320.3  795.09
#Mann=6,-1,0
  4679.5    0.14       0  4875.7    0.08       0  4920.3    0.14       0
  4985.9    0.05       0  5014.1    0.14       0  5175.1    0.15       0
Bank Sta=4985.9,5014.1
XS Rating Curve= 0
Exp/Cntr=0.3,0.1

Type RM Length L Ch R = 1,25863,1003,1003,1003
BEGIN DESCRIPTION:
Forbush Creek - 20.0
END DESCRIPTION:
XS GIS Cut Line= 2
      1540692.57       872867.48      1540524.72       872249.67
#Sta/Elev= 30
  4736.1  785.74  4751.0  785.18  4795.9  781.04  4850.2  775.16  4882.8  769.00
  4924.4  758.25  4947.7  750.50  4954.1  749.64  4959.4  748.93  4970.6  748.74
  4987.5  746.04  4989.4  739.99  4990.6  735.99  5009.4  735.99  5012.4  739.99
  5030.9  748.64  5063.8  747.21  5084.6  750.58  5088.9  750.20  5095.2  750.66
  5114.8  753.79  5150.8  761.10  5188.9  767.15  5214.4  769.46  5265.4  776.30
  5276.7  777.19  5304.4  780.77  5318.0  783.78  5341.5  787.09  5376.3  790.23
#Mann=4,-1,0
  4736.1    0.14       0  4954.1    0.08       0  4989.4    0.05       0
  5012.4    0.14       0
Bank Sta=4989.4,5012.4
XS Rating Curve= 0
Exp/Cntr=0.3,0.1

Type RM Length L Ch R = 1,24860,650,650,650
BEGIN DESCRIPTION:
Forbush Creek - 19.0
END DESCRIPTION:
XS GIS Cut Line= 3
      1541631.84       872696.03      1541542.57       872256.79
      1541453.28       872106.78
#Sta/Elev= 30
  4592.8  772.58  4618.6  770.34  4630.4  770.31  4743.7  764.24  4772.4  761.84
  4780.1  760.62  4815.0  757.28  4847.0  753.02  4858.8  752.25  4876.1  748.46
  4890.6  747.09  4909.2  746.92  4957.2  746.33  4978.0  747.31  4987.7  738.66
  4989.1  734.66  5010.9  734.66  5012.3  738.66  5020.3  747.64  5026.9  752.38
  5037.1  758.18  5044.5  763.14  5058.9  770.47  5065.2  773.06  5107.1  786.04
  5147.9  794.66  5161.0  798.45  5174.5  800.39  5208.0  809.13  5215.6  810.29
#Mann=4,-1,0
  4592.8    0.08       0  4909.2    0.14       0  4987.7    0.05       0
  5012.3    0.14       0
Bank Sta=4987.7,5012.3
XS Rating Curve= 0
Exp/Cntr=0.3,0.1

Type RM Length L Ch R = 1,24210,331,331,331
BEGIN DESCRIPTION:
Forbush Creek - 18.0
END DESCRIPTION:
XS GIS Cut Line= 3
      1542295.16       872639.66      1542158.16       872073.67
      1542027.87       871979.32
#Sta/Elev= 30
  4463.0  788.56  4481.6  786.56  4491.6  783.47  4501.7  777.14  4509.2  776.05
  4545.6  774.81  4556.1  772.43  4615.4  768.33  4671.3  761.50  4698.0  756.30
  4707.5  753.02  4716.5  748.90  4735.7  748.88  4786.2  745.99  4817.7  745.27
  4933.3  745.93  4968.0  746.15  4983.2  740.89  4985.9  738.20  4987.5  734.20
  5012.5  734.20  5014.1  738.20  5038.7  744.42  5059.3  748.02  5099.2  763.11
  5130.2  771.18  5143.0  775.22  5166.5  781.06  5174.7  784.26  5206.2  790.08
#Mann=4,-1,0
  4463.0    0.08       0  4933.3    0.14       0  4985.9    0.05       0
  5014.1    0.14       0
#XS Ineff=2,0
    0.00 4820.00  772.38               0
Permanent Ineff=
       F       F
Bank Sta=4985.9,5014.1
XS Rating Curve= 0
Exp/Cntr=0.5,0.3

Type RM Length L Ch R = 1,23879,124,124,124
BEGIN DESCRIPTION:
Falcon Road  FC - us
END DESCRIPTION:
XS GIS Cut Line= 6
      1542393.97       872648.59      1542389.48       872352.15
      1542465.84       872255.58      1542474.82       872075.91
      1542479.32       871880.52      1542645.50       871550.41
#Sta/Elev= 30
  4322.1  795.30  4371.7  791.55  4438.8  781.66  4469.1  778.17  4481.6  774.15
  4494.6  767.03  4498.8  766.07  4550.9  763.11  4584.9  749.19  4594.7  748.42
  4659.3  746.16  4935.8  744.34  4970.2  745.12  4977.3  743.73  4981.0  740.60
  4989.0  733.80  5011.0  733.80  5019.0  740.60  5024.7  743.98  5032.1  744.54
  5067.5  744.26  5131.3  745.25  5192.0  749.30  5206.9  751.93  5240.9  753.41
  5279.0  755.80  5313.8  760.72  5366.4  765.02  5429.4  768.68  5486.6  775.42
#Mann=11,-1,0
  4322.1    0.08       0  4438.8    0.14       0  4498.8    0.08       0
  4935.8    0.14       0  4981.0    0.05       0  5019.0    0.14       0
  5067.5    0.08       0  5131.3    0.14       0  5240.9    0.14       0
  5366.4    0.12       0  5429.4    0.08       0
#XS Ineff=2,0
    0.00 4904.50  749.58 5095.50    0.00  750.00
Permanent Ineff=
       F       F
Bank Sta=4981,5019
XS Rating Curve= 0
Exp/Cntr=0.5,0.3

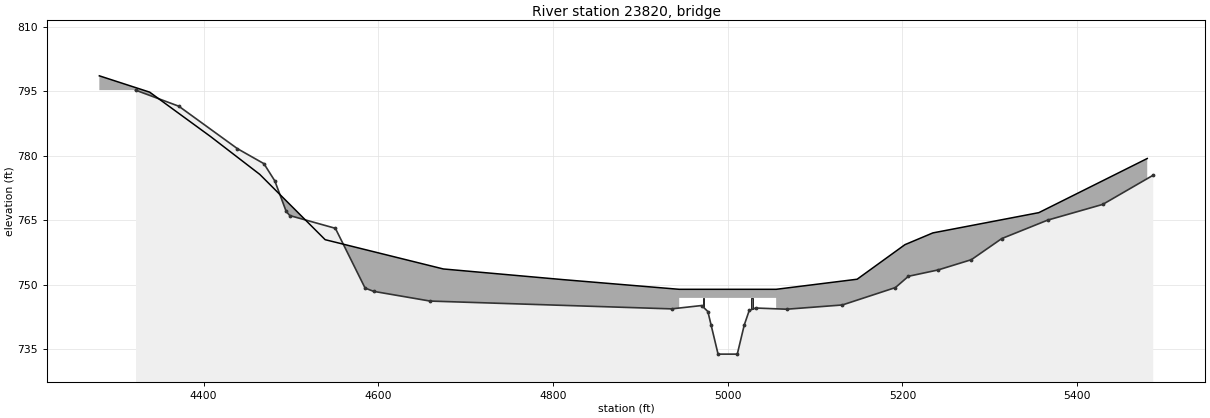
Type RM Length L Ch R =3,23820,,,
BEGIN DESCRIPTION:
Falcon Road  FC - TOR
Structure ID: LDS_FC_03
Approximate Survey Structure
END DESCRIPTION:
Bridge Culvert--1,0,-1,-1,0
Deck Dist Width WeirC Skew NumUp NumDn MinLoCord MaxHiCord MaxSubmerge Is_Ogee
40,38,3,,16,16,,,0.95,0,1,1,,,
  4280.7  4338.3  4408.0  4464.3  4539.2  4674.5  4810.8  4944.5  4944.5  5055.5
  5055.5  5148.2  5202.9  5234.9  5356.2  5480.3
  798.63  794.83  784.49  775.68  760.46  753.64  751.17  748.90  748.90  748.90
  748.90  751.25  759.30  762.04  766.76  779.37
  713.80  713.80  713.80  713.80  713.80  713.80  713.80  713.80  746.90  746.90
  713.80  713.80  713.80  713.80  713.80  713.80
  4280.7  4338.3  4408.0  4464.3  4539.2  4674.5  4810.8  4944.5  4944.5  5055.5
  5055.5  5148.2  5202.9  5234.9  5356.2  5480.3
  798.63  794.83  784.49  775.68  760.46  753.64  751.17  748.90  748.90  748.90
  748.90  751.25  759.30  762.04  766.76  779.37
  713.80  713.80  713.80  713.80  713.80  713.80  713.80  713.80  746.90  746.90
  713.80  713.80  713.80  713.80  713.80  713.80
Pier Skew, UpSta & Num, DnSta & Num=,4972.3,2,4972.3,2,0,0,0,0,0
     1.4     1.4
  744.71  746.90
     1.4     1.4
  741.14  746.90
Pier Skew, UpSta & Num, DnSta & Num=,5027.8,2,5027.8,2,0,0,0,0,0
     1.4     1.4
  744.21  746.90
     1.4     1.4
  741.48  746.90
Abutment Skew #Up #Dn=,2,2
  4944.5  4961.0
  746.90  744.87
  4944.5  4961.0
  746.90  743.05
Abutment Skew #Up #Dn=,2,2
  5039.0  5055.5
  744.14  746.90
  5039.0  5055.5
  742.87  746.90
BR Coef=1,1,0,1.25,0,,,0.8,0,2,0,
WSPro=,,,, 1 ,,,, 0 ,,,, 0 ,,,,-1 ,-1 ,-1 , 0 , 0 , 0 , 0 , 0
BC Design=,,0,,0,,,,,,