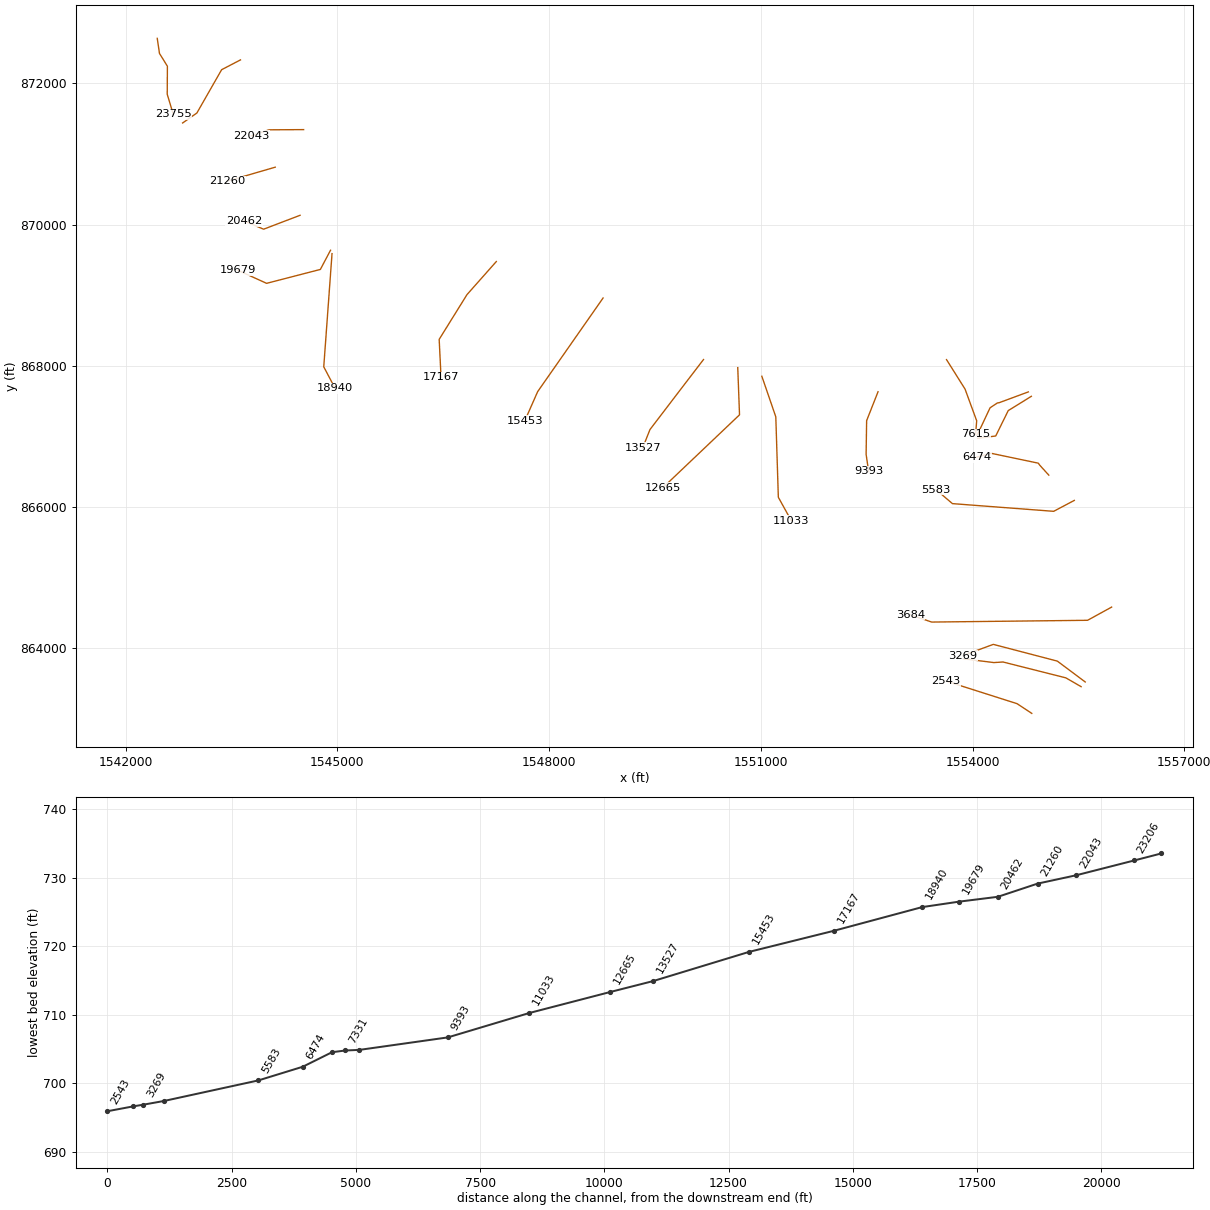
HEC-RAS study Forbush Creek.prj: Forbush Creek Limited Detail Study

--- Forbush Creek.g01 (geometry) --- (continued)

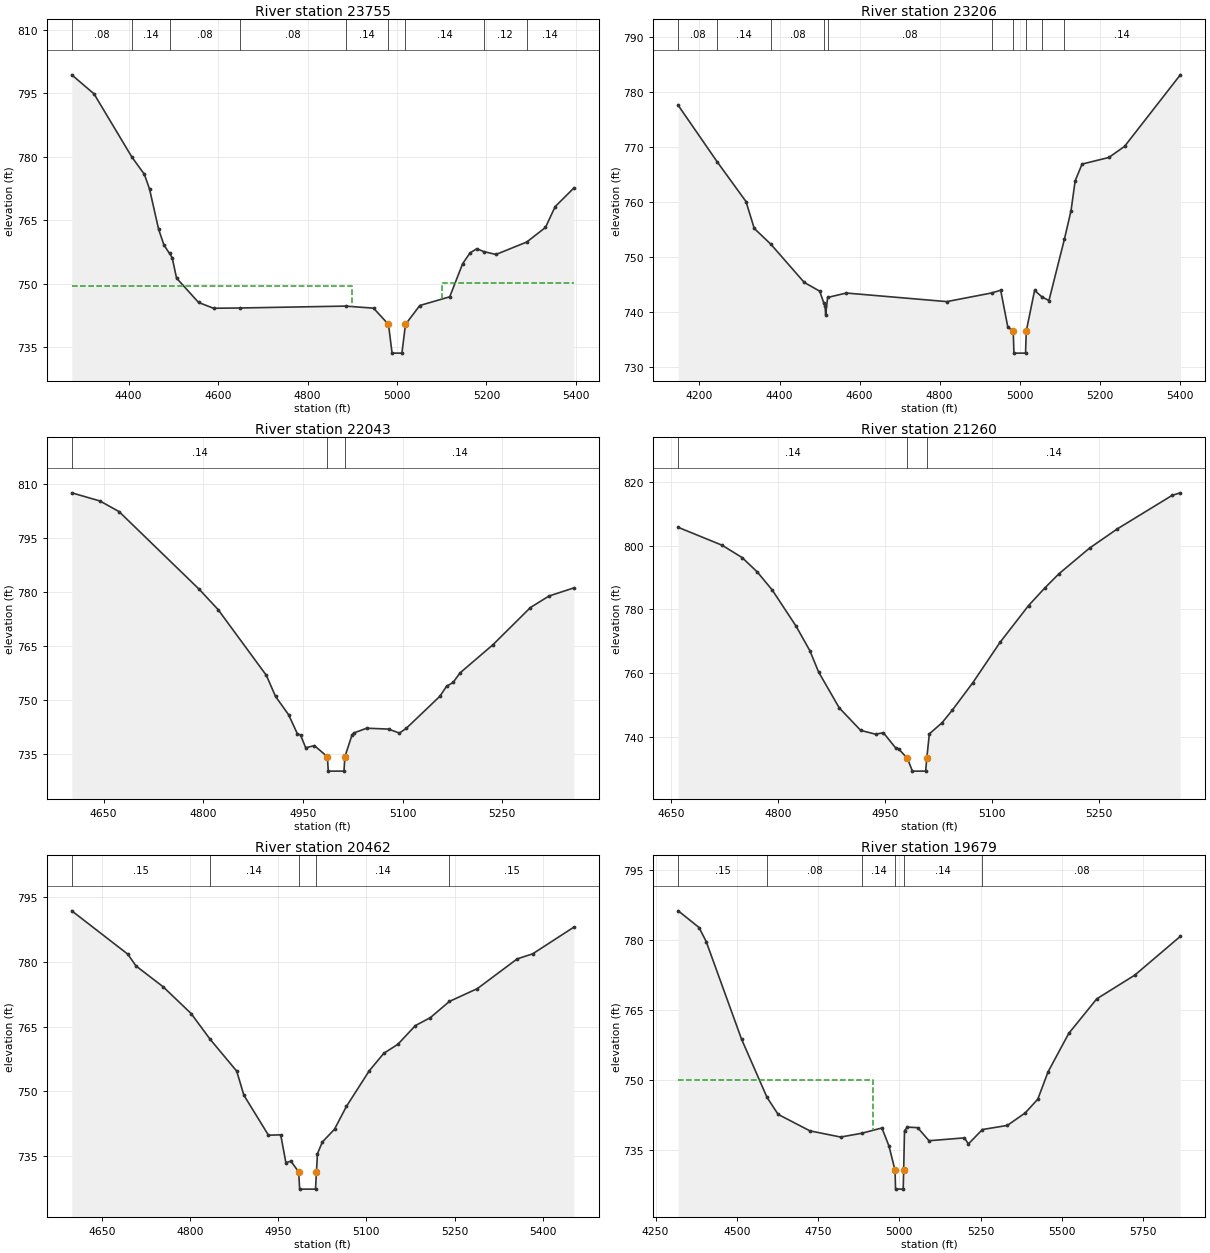
Type RM Length L Ch R = 1,23755,549,549,549
BEGIN DESCRIPTION:
Falcon Road  FC - ds
END DESCRIPTION:
XS GIS Cut Line= 5
      1542447.88       872639.62      1542479.32       872426.27
      1542591.61       872244.35      1542589.36       871846.83
      1542674.70       871563.88
#Sta/Elev= 30
  4272.9  799.41  4322.7  794.90  4407.4  779.93  4435.1  775.89  4446.7  772.41
  4467.1  762.84  4479.0  759.14  4491.4  757.13  4497.3  756.17  4507.2  751.30
  4556.4  745.54  4589.8  744.17  4647.9  744.23  4885.0  744.68  4947.6  744.19
  4981.0  740.35  4989.0  733.55  5011.0  733.55  5019.0  740.35  5051.0  744.82
  5117.9  746.88  5146.8  754.72  5163.4  757.27  5178.5  758.26  5193.6  757.59
  5221.3  756.90  5290.1  759.84  5332.0  763.30  5353.6  768.22  5395.4  772.62
#Mann=9,-1,0
  4272.9    0.08       0  4407.4    0.14       0  4491.4    0.08       0
  4647.9    0.08       0  4885.0    0.14       0  4981.0    0.05       0
  5019.0    0.14       0  5193.6    0.12       0  5290.1    0.14       0
#XS Ineff=2,0
    0.00 4898.50  749.55 5101.50    0.00  750.19
Permanent Ineff=
       F       F
Bank Sta=4981,5019
XS Rating Curve= 0
Exp/Cntr=0.5,0.3

Type RM Length L Ch R = 1,23206,1163,1163,1163
BEGIN DESCRIPTION:
Forbush Creek - 17.0
END DESCRIPTION:
XS GIS Cut Line= 4
      1543626.93       872334.17      1543359.70       872194.94
      1543009.34       871581.82      1542807.23       871440.34
#Sta/Elev= 30
  4146.9  777.63  4244.9  767.28  4316.2  760.12  4336.8  755.22  4378.5  752.33
  4461.6  745.40  4500.3  743.80  4510.4  741.67  4513.7  741.08  4515.1  739.51
  4520.1  742.66  4566.8  743.46  4817.8  741.90  4930.2  743.48  4952.4  743.97
  4970.3  737.23  4983.7  736.52  4985.5  732.52  5014.5  732.52  5016.3  736.52
  5037.1  743.94  5055.6  742.75  5073.0  742.10  5111.5  753.25  5128.1  758.45
  5138.4  763.89  5155.7  766.94  5222.5  768.14  5261.8  770.16  5401.1  783.19
#Mann=10,-1,0
  4146.9    0.08       0  4244.9    0.14       0  4378.5    0.08       0
  4510.4    0.05       0  4520.1    0.08       0  4930.2    0.14       0
  4983.7    0.05       0  5016.3    0.14       0  5055.6    0.08       0
  5111.5    0.14       0
Bank Sta=4983.7,5016.3
XS Rating Curve= 0
Exp/Cntr=0.3,0.1

Type RM Length L Ch R = 1,22043,783,783,783
BEGIN DESCRIPTION:
Forbush Creek - 16.0
END DESCRIPTION:
XS GIS Cut Line= 3
      1544521.72       871346.32      1544030.21       871343.57
      1543780.33       871258.44
#Sta/Elev= 30
  4602.2  807.53  4644.7  805.26  4673.4  802.32  4793.9  780.80  4822.3  775.18
  4895.1  756.90  4908.8  751.08  4928.5  746.00  4941.5  740.80  4946.4  740.38
  4954.2  736.85  4967.3  737.44  4986.8  734.37  4988.2  730.37  5011.8  730.37
  5013.2  734.37  5024.1  740.51  5026.7  740.96  5046.0  742.27  5078.8  742.03
  5095.2  740.92  5105.4  742.21  5156.1  751.12  5166.2  753.91  5176.0  754.95
  5186.3  757.58  5235.8  765.39  5292.4  775.73  5320.2  778.91  5357.7  781.17
#Mann=3,-1,0
  4602.2    0.14       0  4986.8    0.05       0  5013.2    0.14       0
Bank Sta=4986.8,5013.2
XS Rating Curve= 0
Exp/Cntr=0.3,0.1

Type RM Length L Ch R = 1,21260,798,798,798
BEGIN DESCRIPTION:
Forbush Creek - 15.0
END DESCRIPTION:
XS GIS Cut Line= 2
      1544119.82       870814.25      1543443.35       870617.16
#Sta/Elev= 30
  4659.6  805.79  4721.0  800.18  4749.3  796.28  4770.5  791.77  4791.6  786.06
  4824.8  774.78  4844.2  767.06  4856.7  760.25  4885.6  749.02  4915.6  741.96
  4936.5  740.75  4947.5  741.21  4964.7  736.44  4968.8  736.14  4981.3  733.14
  4988.2  729.14  5006.8  729.14  5008.4  733.14  5012.0  740.85  5029.9  744.37
  5044.1  748.29  5073.0  756.94  5111.2  769.63  5151.2  781.19  5174.2  786.77
  5194.0  791.21  5236.8  799.26  5275.6  805.27  5352.8  815.85  5364.2  816.64
#Mann=3,-1,0
  4659.6    0.14       0  4981.3    0.05       0  5008.4    0.14       0
Bank Sta=4981.3,5008.4
XS Rating Curve= 0
Exp/Cntr=0.3,0.1

Type RM Length L Ch R = 1,20462,783,783,783
BEGIN DESCRIPTION:
Forbush Creek - 14.0
END DESCRIPTION:
XS GIS Cut Line= 3
      1544471.41       870132.43      1543954.68       869935.32
      1543677.70       870052.51
#Sta/Elev= 30
  4599.0  791.89  4694.3  781.82  4708.2  779.08  4754.5  774.23  4802.0  768.02
  4834.0  762.09  4879.5  754.64  4891.7  749.04  4933.5  739.75  4954.3  739.84
  4963.1  733.38  4971.6  733.72  4984.9  731.22  4986.5  727.22  5013.5  727.22
  5015.1  731.22  5016.8  735.45  5025.1  738.17  5045.8  741.14  5066.0  746.43
  5104.8  754.70  5129.7  758.79  5153.5  760.87  5183.3  765.22  5208.8  767.07
  5241.2  770.84  5288.8  773.82  5356.4  780.72  5382.8  781.90  5452.8  788.10
#Mann=5,-1,0
  4599.0    0.15       0  4834.0    0.14       0  4984.9    0.05       0
  5015.1    0.14       0  5241.2    0.15       0
Bank Sta=4984.9,5015.1
XS Rating Curve= 0
Exp/Cntr=0.3,0.1

Type RM Length L Ch R = 1,19679,739,739,739
BEGIN DESCRIPTION:
Forbush Creek - 13.0
END DESCRIPTION:
XS GIS Cut Line= 4
      1544902.85       869637.04      1544759.02       869365.36
      1543997.29       869168.27      1543587.10       869354.72
#Sta/Elev= 30
  4319.6  786.19  4383.6  782.61  4405.7  779.59  4514.4  758.67  4592.9  746.17
  4627.0  742.54  4724.6  739.01  4819.2  737.68  4884.3  738.49  4946.3  739.63
  4968.0  735.75  4986.8  730.51  4988.2  726.51  5011.8  726.51  5013.2  730.51
  5015.8  739.05  5024.9  739.81  5056.3  739.69  5091.2  736.89  5200.2  737.50
  5212.3  736.20  5255.5  739.29  5332.1  740.17  5387.0  742.84  5425.9  745.80
  5457.4  751.64  5521.1  759.90  5607.4  767.32  5724.1  772.39  5864.4  780.71
#Mann=6,-1,0
  4319.6    0.15       0  4592.9    0.08       0  4884.3    0.14       0
  4986.8    0.05       0  5013.2    0.14       0  5255.5    0.08       0
#XS Ineff=2,0
    0.00 4920.00  749.83               0
Permanent Ineff=
       F       F
Bank Sta=4986.8,5013.2
XS Rating Curve= 0
Exp/Cntr=0.3,0.1

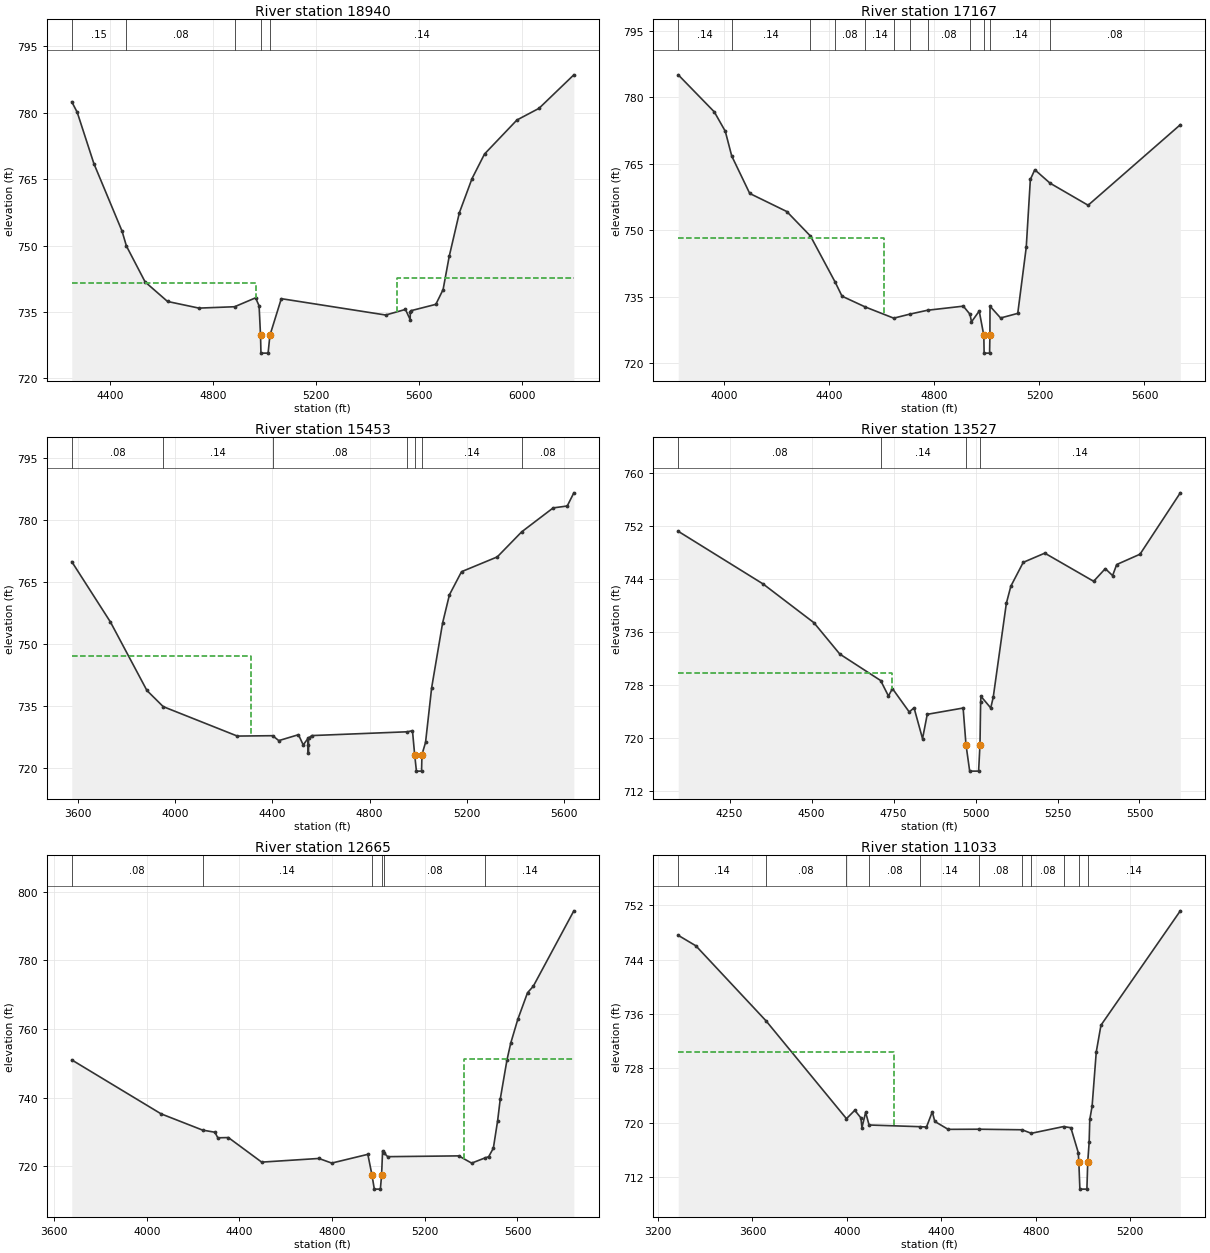
Type RM Length L Ch R = 1,18940,1773,1773,1773
BEGIN DESCRIPTION:
Forbush Creek - 12.0
END DESCRIPTION:
XS GIS Cut Line= 3
      1544924.15       869589.04      1544806.96       867985.72
      1544966.76       867682.11
#Sta/Elev= 30
  4251.1  782.45  4272.3  780.07  4337.0  768.50  4446.4  753.26  4463.4  749.90
  4536.1  741.79  4623.2  737.38  4745.2  735.88  4883.8  736.19  4965.3  738.20
  4978.9  736.39  4984.5  729.72  4986.1  725.72  5013.9  725.72  5020.9  729.72
  5065.2  738.01  5470.8  734.32  5547.5  735.58  5565.9  733.29  5566.4  735.01
  5569.2  735.30  5665.6  736.73  5693.8  740.06  5717.5  747.54  5757.0  757.40
  5806.1  765.10  5854.8  770.66  5980.6  778.33  6066.3  780.96  6201.8  788.53
#Mann=5,-1,0
  4251.1    0.15       0  4463.4    0.08       0  4883.8    0.14       0
  4984.5    0.05       0  5020.9    0.14       0
#XS Ineff=2,0
    0.00 4965.60  741.57 5515.00    0.00  742.71
Permanent Ineff=
       F       F
Bank Sta=4984.5,5020.9
XS Rating Curve= 0
Exp/Cntr=0.3,0.1

Type RM Length L Ch R = 1,17167,1714,1714,1714
BEGIN DESCRIPTION:
Forbush Creek - 11.0
END DESCRIPTION:
XS GIS Cut Line= 4
      1547251.93       869477.20      1546836.46       869008.46
      1546442.28       868374.58      1546468.92       867836.55
#Sta/Elev= 30
  3825.0  785.07  3962.3  776.71  4004.1  772.34  4028.6  766.76  4097.2  758.30
  4238.3  754.22  4328.4  748.69  4422.2  738.32  4448.6  735.12  4537.7  732.67
  4645.5  730.16  4706.7  731.07  4774.4  731.95  4910.4  732.87  4935.8  731.04
  4941.5  729.32  4970.9  731.77  4988.4  726.27  4989.6  722.27  5010.4  722.27
  5011.6  726.27  5012.0  732.86  5052.3  730.20  5117.6  731.24  5149.9  746.12
  5165.6  761.46  5182.5  763.65  5240.6  760.62  5385.5  755.64  5736.5  773.81
#Mann=12,-1,0
  3825.0    0.14       0  4028.6    0.14       0  4328.4    0.14       0
  4422.2    0.08       0  4537.7    0.14       0  4645.5    0.08       0
  4706.7    0.14       0  4774.4    0.08       0  4935.8    0.14       0
  4988.4    0.05       0  5011.6    0.14       0  5240.6    0.08       0
#XS Ineff=2,0
    0.00 4610.00  748.18               0
Permanent Ineff=
       F       F
Bank Sta=4988.4,5011.6
XS Rating Curve= 0
Exp/Cntr=0.3,0.1

Type RM Length L Ch R = 1,15453,1926,1926,1926
BEGIN DESCRIPTION:
Forbush Creek - 10.0
END DESCRIPTION:
XS GIS Cut Line= 3
      1548764.74       868960.50      1547837.90       867634.16
      1547656.77       867223.95
#Sta/Elev= 30
  3574.2  769.91  3733.4  755.29  3883.4  738.72  3950.6  734.80  4255.6  727.67
  4400.9  727.76  4426.3  726.57  4507.2  728.00  4526.9  725.53  4546.9  727.14
  4547.8  725.40  4547.9  723.60  4548.6  727.16  4562.0  727.79  4955.8  728.71
  4976.5  728.98  4985.5  723.18  4992.8  719.18  5013.9  719.18  5015.5  723.18
  5030.3  726.13  5055.5  739.40  5100.5  755.05  5128.6  761.88  5178.4  767.48
  5325.5  771.06  5426.0  777.13  5555.6  782.93  5613.5  783.39  5640.7  786.58
#Mann=7,-1,0
  3574.2    0.08       0  3950.6    0.14       0  4400.9    0.08       0
  4955.8    0.14       0  4985.5    0.05       0  5015.5    0.14       0
  5426.0    0.08       0
#XS Ineff=2,0
    0.00 4310.00  746.99               0
Permanent Ineff=
       F       F
Bank Sta=4985.5,5015.5
XS Rating Curve= 0
Exp/Cntr=0.3,0.1

Type RM Length L Ch R = 1,13527,862,862,862
BEGIN DESCRIPTION:
Forbush Creek - 9.0
END DESCRIPTION:
XS GIS Cut Line= 4
      1550187.50       868088.80      1549835.24       867628.71
      1549429.07       867096.74      1549324.83       866834.34
#Sta/Elev= 30
  4093.4  751.15  4352.1  743.20  4507.1  737.35  4586.1  732.61  4710.7  728.61
  4734.5  726.27  4746.6  727.40  4797.9  723.86  4812.5  724.50  4838.4  719.83
  4852.8  723.51  4962.2  724.46  4970.9  718.93  4982.2  714.93  5009.4  714.93
  5013.6  718.93  5015.6  725.44  5016.7  726.22  5046.4  724.47  5054.0  726.09
  5094.0  740.27  5107.7  742.86  5145.5  746.46  5211.2  747.85  5360.2  743.60
  5395.7  745.51  5418.0  744.46  5430.5  746.13  5501.6  747.69  5624.5  756.96
#Mann=4,-1,0
  4093.4    0.08       0  4710.7    0.14       0  4970.9    0.05       0
  5013.6    0.14       0
#XS Ineff=2,0
    0.00 4746.60  729.71               0
Permanent Ineff=
       F       F
Bank Sta=4970.9,5013.6
XS Rating Curve= 0
Exp/Cntr=0.3,0.1

Type RM Length L Ch R = 1,12665,1632,1632,1632
BEGIN DESCRIPTION:
Forbush Creek - 8.0
END DESCRIPTION:
XS GIS Cut Line= 3
      1550672.74       867973.78      1550697.90       867305.21
      1549612.35       866273.58
#Sta/Elev= 30
  3676.7  751.00  4062.1  735.28  4241.3  730.54  4294.4  729.92  4306.9  728.30
  4352.5  728.37  4496.2  721.21  4743.1  722.28  4798.5  720.93  4954.3  723.48
  4972.5  717.34  4982.2  713.34  5008.4  713.34  5013.6  717.34  5018.0  724.54
  5023.8  723.92  5039.9  722.80  5346.5  723.03  5402.4  720.92  5460.9  722.46
  5475.7  722.79  5495.9  725.26  5514.5  733.31  5525.7  739.57  5554.9  751.06
  5571.2  755.95  5601.3  762.79  5643.4  770.58  5668.2  772.46  5843.3  794.45
#Mann=6,-1,0
  3676.7    0.08       0  4241.3    0.14       0  4972.5    0.05       0
  5013.6    0.14       0  5023.8    0.08       0  5460.9    0.14       0
#XS Ineff=2,0
       0                 5370.00    0.00  751.24
Permanent Ineff=
       F       F
Bank Sta=4972.5,5013.6
XS Rating Curve= 0
Exp/Cntr=0.3,0.1

Type RM Length L Ch R = 1,11033,1640,1640,1640
BEGIN DESCRIPTION:
Forbush Creek - 7.0
END DESCRIPTION:
XS GIS Cut Line= 4
      1551014.21       867851.54      1551211.90       867276.46
      1551247.84       866137.03      1551431.16       865806.35
#Sta/Elev= 30
  3285.6  747.55  3360.4  746.01  3657.4  734.99  3998.0  720.62  4033.3  721.85
  4059.1  720.73  4063.5  719.30  4079.2  721.55  4093.8  719.69  4311.5  719.44
  4336.9  719.39  4361.5  721.63  4372.1  720.21  4428.7  719.05  4560.1  719.07
  4741.4  718.99  4780.6  718.47  4917.4  719.46  4948.3  719.29  4979.8  715.62
  4982.1  714.27  4986.5  710.27  5016.2  710.27  5019.8  714.27  5025.7  717.13
  5028.4  720.50  5038.2  722.43  5055.9  730.43  5075.8  734.35  5411.8  751.15
#Mann=11,-1,0
  3285.6    0.14       0  3657.4    0.08       0  3998.0    0.14       0
  4093.8    0.08       0  4311.5    0.14       0  4560.1    0.08       0
  4741.4    0.14       0  4780.6    0.08       0  4917.4    0.14       0
  4982.1    0.05       0  5019.8    0.14       0
#XS Ineff=2,0
    0.00 4200.00  730.41               0
Permanent Ineff=
       F       F
Bank Sta=4982.1,5019.8
XS Rating Curve= 0
Exp/Cntr=0.3,0.1

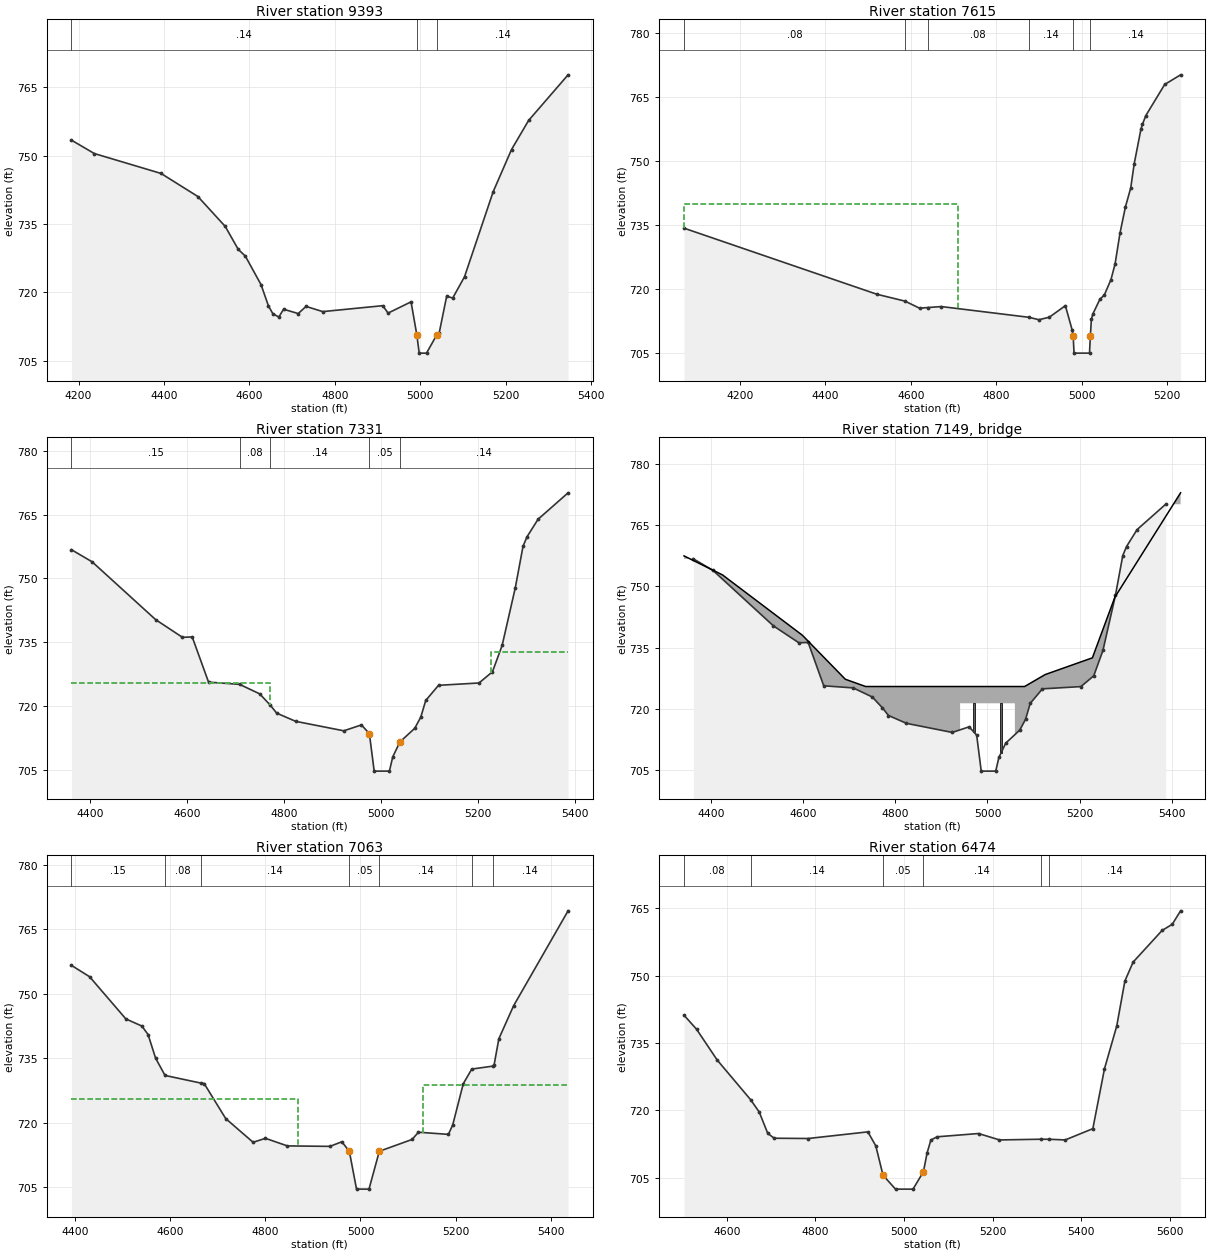
Type RM Length L Ch R = 1,9393,1778,1778,1778
BEGIN DESCRIPTION:
Forbush Creek - 6.0
END DESCRIPTION:
XS GIS Cut Line= 4
      1552660.46       867632.34      1552498.70       867222.54
      1552491.51       866744.48      1552527.46       866503.63
#Sta/Elev= 30
  4183.6  753.38  4237.0  750.45  4393.1  746.09  4479.4  741.03  4543.4  734.48
  4573.9  729.44  4590.4  727.98  4627.1  721.74  4644.5  717.07  4654.9  715.34
  4668.8  714.62  4680.0  716.33  4714.2  715.38  4732.5  716.95  4771.6  715.81
  4912.2  717.11  4924.5  715.48  4978.3  717.95  4991.8  710.71  4997.4  706.71
  5014.5  706.71  5038.5  710.71  5044.3  711.19  5061.7  719.20  5075.8  718.78
  5103.4  723.44  5170.6  742.11  5213.4  751.32  5253.4  757.70  5345.8  767.70
#Mann=3,-1,0
  4183.6    0.14       0  4991.8    0.05       0  5038.5    0.14       0
Bank Sta=4991.8,5038.5
XS Rating Curve= 0
Exp/Cntr=0.3,0.1

Type RM Length L Ch R = 1,7615,284,284,284
BEGIN DESCRIPTION:
Forbush Creek - 5.0
END DESCRIPTION:
XS GIS Cut Line= 4
      1553630.84       868087.33      1553893.19       867670.06
      1554058.10       867220.31      1554043.11       867030.42
#Sta/Elev= 30
  4068.9  734.17  4520.2  718.69  4586.3  717.07  4620.4  715.41  4639.2  715.57
  4671.2  715.80  4875.9  713.29  4899.7  712.72  4924.1  713.31  4961.6  716.01
  4977.2  710.42  4979.9  708.89  4981.9  704.89  5018.1  704.89  5020.1  708.89
  5022.5  712.82  5025.8  714.03  5042.3  717.49  5052.9  718.53  5068.4  722.14
  5078.0  725.81  5089.4  732.97  5102.3  739.20  5114.6  743.59  5122.7  749.25
  5138.7  757.47  5141.9  758.47  5149.9  760.55  5194.1  767.84  5231.3  770.10
#Mann=6,-1,0
  4068.9    0.08       0  4586.3    0.14       0  4639.2    0.08       0
  4875.9    0.14       0  4979.9    0.05       0  5020.1    0.14       0
#XS Ineff=2,0
    0.00 4710.00  739.87               0
Permanent Ineff=
       F       F
Bank Sta=4979.9,5020.1
XS Rating Curve= 0
Exp/Cntr=0.5,0.3

Type RM Length L Ch R = 1,7331,268,268,268
BEGIN DESCRIPTION:
Baltimore Road  FC - us
END DESCRIPTION:
XS GIS Cut Line= 5
      1554790.23       867630.10      1554377.93       867477.67
      1554350.44       867472.67      1554248.00       867405.21
      1554063.08       867012.88
#Sta/Elev= 30
  4362.4  756.74  4405.0  753.90  4536.0  740.33  4591.2  736.19  4611.3  736.28
  4645.0  725.68  4708.9  725.16  4750.4  722.93  4772.4  720.26  4785.4  718.41
  4824.4  716.49  4923.8  714.26  4960.2  715.64  4976.6  713.60  4986.5  704.80
  5017.9  704.80  5024.8  708.15  5039.6  711.65  5070.1  714.84  5082.6  717.48
  5092.8  721.38  5119.2  724.93  5202.7  725.48  5230.4  728.11  5250.4  734.32
  5277.5  747.83  5293.4  757.55  5301.5  759.75  5324.4  763.89  5386.3  770.09
#Mann=5,-1,0
  4362.4    0.15       0  4708.9    0.08       0  4772.4    0.14       0
  4976.6    0.05       0  5039.6    0.14       0
#XS Ineff=2,0
    0.00 4772.20  725.50 5227.90    0.00  732.73
Permanent Ineff=
       F       F
Bank Sta=4976.6,5039.6
XS Rating Curve= 0
Exp/Cntr=0.5,0.3

Type RM Length L Ch R =3,7149,,,
BEGIN DESCRIPTION:
Baltimore Road  FC - TOR
Structure ID: LDS_FC_02
Approximate Survey Structure
END DESCRIPTION:
Bridge Culvert--1,0,-1,-1,0
Deck Dist Width WeirC Skew NumUp NumDn MinLoCord MaxHiCord MaxSubmerge Is_Ogee
168.5,27,3,,14,14,,,0.95,0,1,1,,,
  4342.1  4425.7  4598.8  4691.8  4735.9  4940.7  4940.7  5059.4  5059.4  5080.5
  5125.2  5227.5  5276.2  5418.7
  757.46  752.80  738.04  727.28  725.50  725.50  725.50  725.50  725.50  725.50
  728.43  732.52  747.35  772.89
  684.80  684.80  684.80  684.80  684.80  684.80  721.40  721.40  684.80  684.80
  684.80  684.80  684.80  684.80
  4342.1  4425.7  4598.8  4691.8  4735.9  4940.7  4940.7  5059.4  5059.4  5080.5
  5125.2  5227.5  5276.2  5418.7
  757.46  752.80  738.04  727.28  725.50  725.50  725.50  725.50  725.50  725.50
  728.43  732.52  747.35  772.89
  684.80  684.80  684.80  684.80  684.80  684.80  721.40  721.40  684.80  684.80
  684.80  684.80  684.80  684.80
Pier Skew, UpSta & Num, DnSta & Num=,4970.3,2,4970.3,2,0,0,0,0,0
     3.5     3.5
  714.69  721.40
     3.5     3.5
  716.93  721.40
Pier Skew, UpSta & Num, DnSta & Num=,5029.7,2,5029.7,2,0,0,0,0,0
     3.5     3.5
  708.95  721.40
     3.5     3.5
  711.93  721.40
Abutment Skew #Up #Dn=,2,2
  4940.7  4958.6
  721.40  715.57
  4940.7  4958.6
  721.40  715.36
Abutment Skew #Up #Dn=,2,2
  5041.4  5059.4
  710.59  721.40
  5041.4  5059.4
  709.26  721.40
BR Coef=1,1,0,1.25,0,,,0.8,0,2,0,
WSPro=,,,, 1 ,,,, 0 ,,,, 0 ,,,,-1 ,-1 ,-1 , 0 , 0 , 0 , 0 , 0
BC Design=,,0,,0,,,,,,

Type RM Length L Ch R = 1,7063,589,589,589
BEGIN DESCRIPTION:
Baltimore Road  FC - ds
END DESCRIPTION:
XS GIS Cut Line= 4
      1554832.64       867567.60      1554505.36       867365.23
      1554327.95       867005.43      1554073.07       866972.94
#Sta/Elev= 30
  4393.1  756.56  4431.1  753.93  4507.3  744.12  4540.9  742.46  4553.9  740.49
  4569.7  735.01  4589.5  730.98  4664.1  729.22  4671.7  729.10  4717.0  720.95
  4774.5  715.44  4800.5  716.36  4846.4  714.60  4935.9  714.49  4960.8  715.56
  4976.6  713.35  4991.7  704.55  5017.9  704.55  5039.6  713.35  5108.4  716.10
  5121.7  717.78  5184.7  717.28  5193.8  719.50  5215.9  729.06  5233.7  732.46
  5277.6  733.14  5280.5  733.34  5290.6  739.51  5321.6  747.18  5436.0  769.25
#Mann=7,-1,0
  4393.1    0.15       0  4589.5    0.08       0  4664.1    0.14       0
  4976.6    0.05       0  5039.6    0.14       0  5233.7    0.08       0
  5277.6    0.14       0
#XS Ineff=2,0
    0.00 4868.20  725.50 5131.90    0.00  728.70
Permanent Ineff=
       F       F
Bank Sta=4976.6,5039.6
XS Rating Curve= 0
Exp/Cntr=0.5,0.3

Type RM Length L Ch R = 1,6474,891,891,891
BEGIN DESCRIPTION:
Forbush Creek - 4.0
END DESCRIPTION:
XS GIS Cut Line= 6
      1555080.06       866450.71      1554952.61       866590.66
      1554930.12       866620.64      1554260.49       866760.57
      1554085.59       866713.09      1554058.09       866705.59
#Sta/Elev= 30
  4503.5  741.19  4531.8  738.06  4578.5  731.18  4653.8  722.36  4673.3  719.60
  4692.5  714.85  4707.1  713.77  4783.7  713.71  4918.4  715.19  4936.3  712.07
  4952.6  705.53  4980.8  702.43  5020.3  702.43  5043.8  706.31  5052.1  710.50
  5060.6  713.37  5074.7  714.09  5168.2  714.82  5215.4  713.39  5308.9  713.55
  5327.3  713.54  5363.7  713.39  5426.1  715.90  5452.4  729.26  5480.0  738.76
  5498.4  748.80  5517.0  753.02  5582.4  760.07  5605.3  761.44  5624.1  764.44
#Mann=6,-1,0
  4503.5    0.08       0  4653.8    0.14       0  4952.6    0.05       0
  5043.8    0.14       0  5308.9    0.08       0  5327.3    0.14       0
Bank Sta=4952.6,5043.8
XS Rating Curve= 0
Exp/Cntr=0.3,0.1

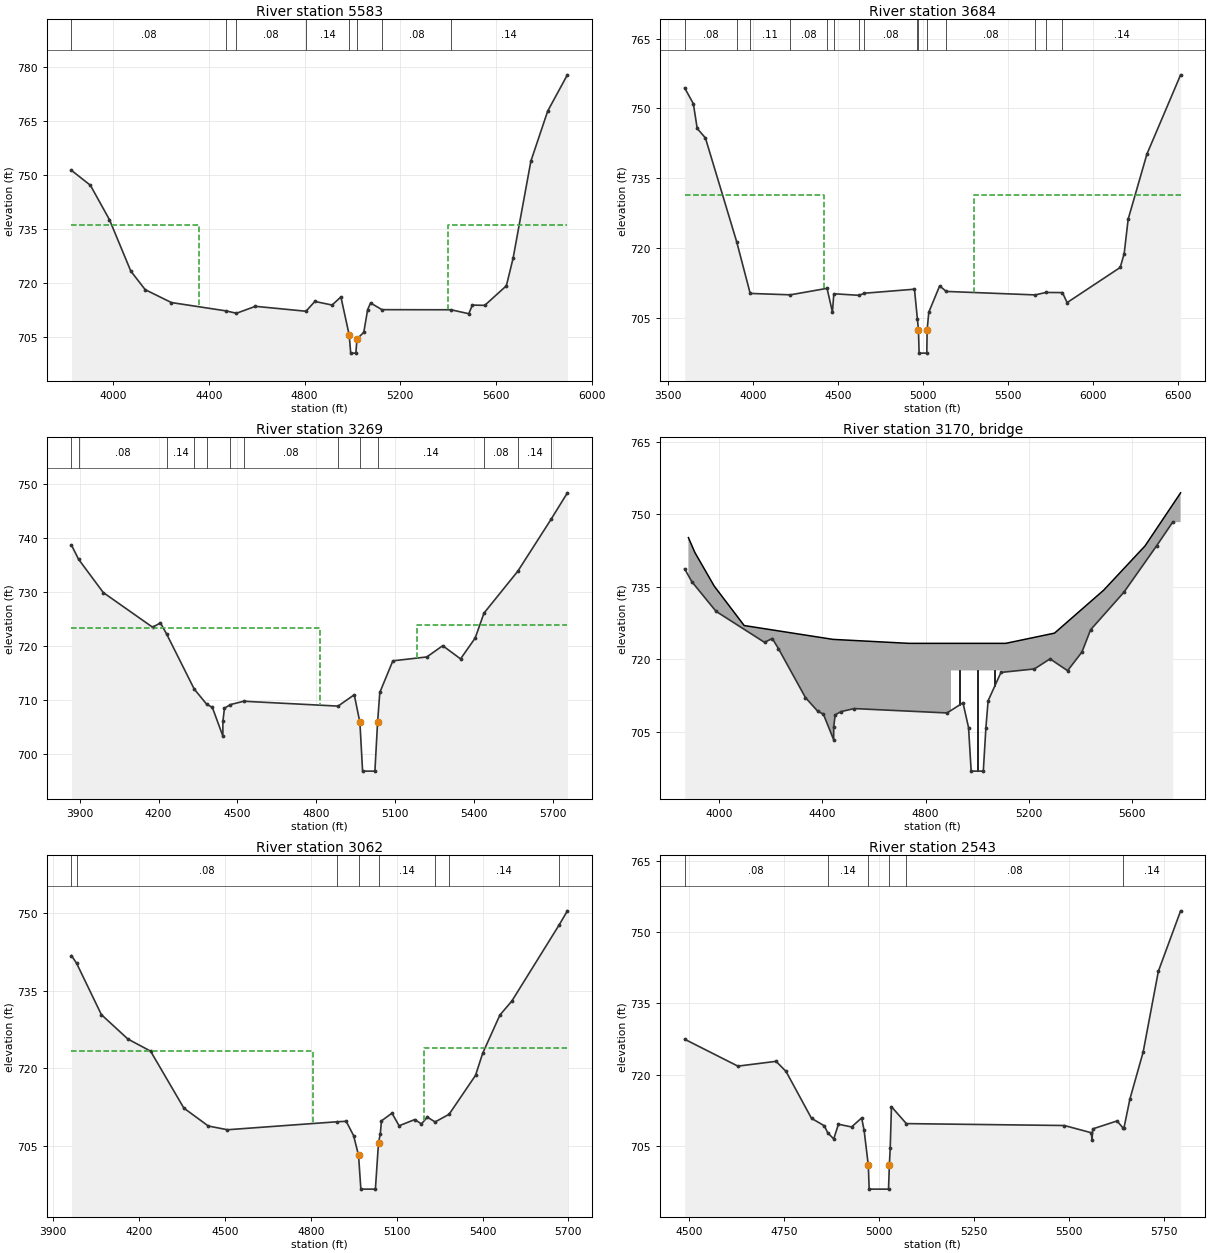
Type RM Length L Ch R = 1,5583,1899,1899,1899
BEGIN DESCRIPTION:
Forbush Creek - 3.0
END DESCRIPTION:
XS GIS Cut Line= 4
      1555441.47       866092.90      1555148.94       865938.03
      1553714.82       866047.03      1553485.37       866242.06
#Sta/Elev= 30
  3827.0  751.32  3905.9  747.18  3985.7  737.59  4074.8  723.27  4135.0  718.10
  4244.3  714.52  4472.3  712.20  4515.8  711.54  4595.1  713.47  4806.1  712.10
  4843.1  714.83  4915.0  713.83  4951.9  716.08  4986.6  705.44  4992.8  700.44
  5014.2  700.44  5019.1  704.39  5047.4  706.24  5063.5  712.55  5075.7  714.40
  5123.2  712.54  5411.8  712.51  5485.8  711.41  5500.7  713.82  5552.4  713.74
  5642.6  719.18  5670.6  726.82  5745.0  753.90  5815.4  767.86  5897.4  777.92
#Mann=8,-1,0
  3827.0    0.08       0  4472.3    0.14       0  4515.8    0.08       0
  4806.1    0.14       0  4986.6    0.05       0  5019.1    0.14       0
  5123.2    0.08       0  5411.8    0.14       0
#XS Ineff=2,0
    0.00 4360.00  736.08 5400.00    0.00  736.10
Permanent Ineff=
       F       F
Bank Sta=4986.6,5019.1
XS Rating Curve= 0
Exp/Cntr=0.3,0.1

Type RM Length L Ch R = 1,3684,415,415,415
BEGIN DESCRIPTION:
Forbush Creek - 2.0
END DESCRIPTION:
XS GIS Cut Line= 4
      1555970.33       864581.26      1555629.16       864394.03
      1553420.05       864369.07      1553116.38       864473.07
#Sta/Elev= 30
  3597.4  754.38  3648.4  750.99  3671.1  745.68  3719.3  743.65  3903.2  721.38
  3983.0  710.26  4219.8  709.96  4435.5  711.35  4467.1  706.25  4475.3  710.19
  4624.5  709.85  4654.6  710.30  4950.0  711.17  4967.2  704.78  4973.5  702.44
  4977.4  697.44  5022.6  697.44  5024.6  702.44  5034.3  706.22  5098.3  711.88
  5137.1  710.69  5661.2  709.94  5723.9  710.47  5821.1  710.44  5848.6  708.29
  6161.3  715.84  6184.6  718.83  6208.0  726.20  6318.6  740.20  6516.8  757.20
#Mann=15,-1,0
  3597.4    0.08       0  3903.2    0.14       0  3983.0    0.11       0
  4219.8    0.08       0  4435.5    0.14       0  4475.3    0.08       0
  4624.5    0.14       0  4654.6    0.08       0  4967.2    0.14       0
  4973.5    0.05       0  5024.6    0.14       0  5137.1    0.08       0
  5661.2    0.14       0  5723.9    0.08       0  5821.1    0.14       0
#XS Ineff=2,0
    0.00 4420.00  731.46 5300.00    0.00  731.46
Permanent Ineff=
       F       F
Bank Sta=4973.5,5024.6
XS Rating Curve= 0
Exp/Cntr=0.5,0.3

Type RM Length L Ch R = 1,3269,207,207,207
BEGIN DESCRIPTION:
SR 1605  FC - us
END DESCRIPTION:
XS GIS Cut Line= 4
      1555595.87       863520.37      1555200.65       863815.75
      1554293.71       864052.89      1553865.18       863894.79
#Sta/Elev= 30
  3868.5  738.69  3895.7  736.06  3989.7  729.91  4177.2  723.51  4207.3  724.30
  4230.9  722.23  4335.7  712.08  4383.6  709.24  4404.7  708.69  4444.8  703.37
  4444.9  706.09  4450.8  708.53  4473.3  709.20  4524.2  709.82  4883.2  708.92
  4944.9  711.02  4966.4  705.90  4976.6  696.90  5023.5  696.90  5033.6  705.90
  5042.1  711.44  5091.8  717.29  5221.2  718.01  5281.6  720.09  5349.5  717.65
  5405.2  721.51  5438.6  726.11  5567.5  733.87  5693.5  743.42  5756.1  748.35
#Mann=13,-1,0
  3868.5    0.14       0  3895.7    0.08       0  4230.9    0.14       0
  4335.7    0.08       0  4383.6    0.14       0  4473.3    0.08       0
  4524.2    0.08       0  4883.2    0.14       0  4966.4    0.05       0
  5033.6    0.14       0  5438.6    0.08       0  5567.5    0.14       0
  5693.5    0.08       0
#XS Ineff=2,0
    0.00 4815.00  723.30 5185.00    0.00  723.97
Permanent Ineff=
       F       F
Bank Sta=4966.4,5033.6
XS Rating Curve= 0
Exp/Cntr=0.5,0.3

Type RM Length L Ch R =3,3170,,,
BEGIN DESCRIPTION:
SR 1605  FC - TOR
Structure ID: LDS_FC_01
Approximate Survey Structure
END DESCRIPTION:
Bridge Culvert--1,0,-1,-1,0
Deck Dist Width WeirC Skew NumUp NumDn MinLoCord MaxHiCord MaxSubmerge Is_Ogee
83.5,31,3,,15,15,,,0.95,0,1,1,,,
  3882.9  3908.0  3982.6  4098.6  4442.2  4735.6  4898.5  4898.5  5101.5  5101.5
  5110.1  5298.9  5489.1  5649.0  5786.7
  745.14  742.06  735.14  726.98  724.12  723.30  723.30  723.30  723.30  723.30
  723.30  725.41  734.29  743.43  754.40
  676.90  676.90  676.90  676.90  676.90  676.90  676.90  717.70  717.70  676.90
  676.90  676.90  676.90  676.90  676.90
  3882.9  3908.0  3982.6  4098.6  4442.2  4735.6  4898.5  4898.5  5101.5  5101.5
  5110.1  5298.9  5489.1  5649.0  5786.7
  745.14  742.06  735.14  726.98  724.12  723.30  723.30  723.30  723.30  723.30
  723.30  725.41  734.29  743.43  754.40
  676.90  676.90  676.90  676.90  676.90  676.90  676.90  717.70  717.70  676.90
  676.90  676.90  676.90  676.90  676.90
Pier Skew, UpSta & Num, DnSta & Num=,4932.3,2,4932.3,2,0,0,0,0,0
       3       3
  710.33  717.70
       3       3
  708.82  717.70
Pier Skew, UpSta & Num, DnSta & Num=,5000,2,5000,2,0,0,0,0,0
       3       3
  696.90  717.70
       3       3
  696.65  717.70
Pier Skew, UpSta & Num, DnSta & Num=,5067.7,2,5067.7,2,0,0,0,0,0
       3       3
  714.37  717.70
       3       3
  710.57  717.70
Abutment Skew #Up #Dn=,2,2
  4898.5  4917.0
  717.70  710.16
  4898.5  4917.0
  717.70  709.63
Abutment Skew #Up #Dn=,2,2
  5083.0  5101.5
  715.71  717.70
  5083.0  5101.5
  711.33  717.70
BR Coef=1,1,0,1.25,0,,,0.8,0,2,0,
WSPro=,,,, 1 ,,,, 0 ,,,, 0 ,,,,-1 ,-1 ,-1 , 0 , 0 , 0 , 0 , 0
BC Design=,,0,,0,,,,,,

Type RM Length L Ch R = 1,3062,519,519,519
BEGIN DESCRIPTION:
SR 1605  FC - ds
END DESCRIPTION:
XS GIS Cut Line= 5
      1555537.61       863453.82      1555321.30       863578.62
      1554431.00       863803.27      1554302.03       863794.95
      1553869.37       863849.03
#Sta/Elev= 30
  3963.3  741.84  3981.1  740.37  4067.9  730.41  4160.6  725.69  4239.8  723.35
  4356.1  712.33  4441.7  708.86  4508.5  708.14  4890.7  709.68  4923.4  709.78
  4949.3  707.01  4966.7  703.17  4974.7  696.65  5025.5  696.65  5036.4  705.65
  5042.6  707.30  5046.7  709.86  5083.5  711.35  5108.3  708.91  5163.0  710.11
  5186.4  709.27  5207.1  710.58  5234.2  709.65  5283.2  711.14  5375.5  718.67
  5400.5  722.95  5460.6  730.33  5502.3  733.04  5668.0  747.80  5696.5  750.50
#Mann=8,-1,0
  3963.3    0.14       0  3981.1    0.08       0  4890.7    0.14       0
  4966.7    0.05       0  5036.4    0.14       0  5234.2    0.08       0
  5283.2    0.14       0  5668.0    0.08       0
#XS Ineff=2,0
    0.00 4806.00  723.30 5194.00    0.00  723.95
Permanent Ineff=
       F       F
Bank Sta=4966.7,5036.4
XS Rating Curve= 0
Exp/Cntr=0.5,0.3

Type RM Length L Ch R = 1,2543,0,0,0
BEGIN DESCRIPTION:
Forbush Creek - 1.0
END DESCRIPTION:
XS GIS Cut Line= 3
      1554838.70       863075.23      1554630.69       863212.51
      1553623.86       863532.87
#Sta/Elev= 30
  4488.8  727.44  4628.9  721.79  4729.4  722.80  4755.6  720.68  4822.7  710.82
  4856.5  709.25  4865.3  707.80  4881.2  706.48  4893.6  709.58  4928.2  709.01
  4954.7  710.90  4961.2  708.31  4972.3  700.94  4974.5  695.94  5025.5  695.94
  5027.7  700.94  5030.0  704.67  5033.2  713.27  5072.4  709.71  5488.4  709.31
  5559.5  707.79  5561.3  706.23  5563.2  708.60  5627.3  710.27  5642.6  708.82
  5645.2  708.72  5661.1  714.88  5695.9  724.73  5736.0  741.73  5794.6  754.43
#Mann=6,-1,0
  4488.8    0.08       0  4865.3    0.14       0  4972.3    0.05       0
  5027.7    0.14       0  5072.4    0.08       0  5642.6    0.14       0
Bank Sta=4972.3,5027.7
XS Rating Curve= 0
Exp/Cntr=0.3,0.1

Chan Stop Cuts=-1