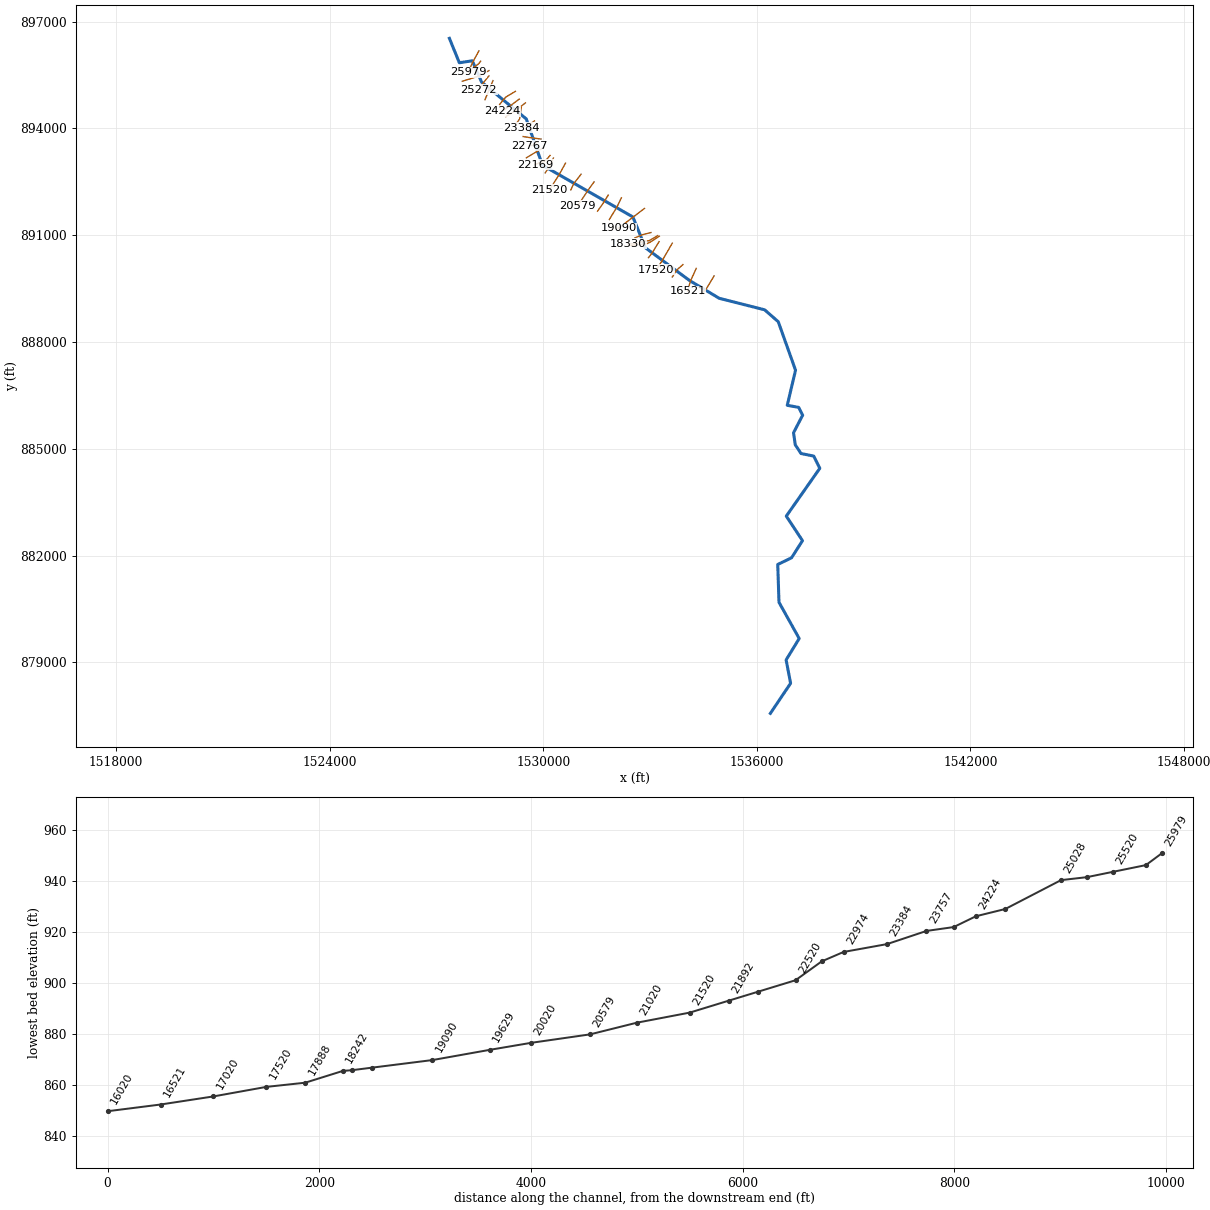
--- Little Forbush Creek.prj (project) ---

Proj Title=Little Forbush Creek Limited Detail Study
Current Plan=p01
Default Exp/Contr=0.3,0.1
English Units
Geom File=g01
Flow File=f01
Plan File=p01
Y Axis Title=Elevation
X Axis Title(PF)=Main Channel Distance
X Axis Title(XS)=Station
BEGIN DESCRIPTION:
Little Forbush Creek
END DESCRIPTION:
DSS Export Rating Curves= 0
DSS Export Rating Curve Sorted= 0
DSS Export Volume Flow Curves= 0
DXF OffsetX= 0
DXF OffsetY= 0
DXF ScaleX= 1
DXF ScaleY= 10

--- Little Forbush Creek.p01 (plan) ---

Plan Title=Floodway Run
Program Version=3.12
Short Identifier=Floodway
Geom File=g01
Flow File=f01
Subcritical Flow
K Sum by GR= 0
Std Step Tol= 0.01
Critical Tol= 0.01
Num of Std Step Trials= 20
Max Error Tol= 0.3
Flow Tol Ratio= 0.001
Split Flow NTrial= 30
Split Flow Tol= 0.02
Split Flow Ratio= 0.02
Log Output Level= 0
Friction Slope Method= 1
Unsteady Friction Slope Method= 2
Unsteady Bridges Friction Slope Method= 1
Parabolic Critical Depth
Global Vel Dist= 0 , 0 , 0
Global Log Level= 0
CheckData=True
Encroach Param=-1 ,0,0, 2
Encroach River=Little Forbush C
Encroach Reach=Reach-1
Encroach Node=25979
       1    4985  5007.8
Encroach Node=25830
       1    4980  5008.2
Encroach Node=25520
       1 4957.54 5011.36
Encroach Node=25272
       1 4987.25    5012
Encroach Node=25028
       1 4973.27  5007.1
Encroach Node=24502
       1    4988 5028.17
Encroach Node=24224
       1 4991.14  5044.5
Encroach Node=24014
       1 4979.88  5020.3
Encroach Node=23757
       1 4987.12 5003.88
Encroach Node=23384
       1    4988 5018.26
Encroach Node=22974
       1 4978.44    5017
Encroach Node=22767
       1  4976.5 5004.64
Encroach Node=22520
       1 4968.53    5015
Encroach Node=22169
       1  4970.4  5008.1
Encroach Node=21892
       1  4987.2  5012.8
Encroach Node=21520
       1 4984.63    5012
Encroach Node=21020
       1 4987.42 5022.63
Encroach Node=20579
       1 4986.86 5016.09
Encroach Node=20020
       1    4988 5023.07
Encroach Node=19629
       1 4940.18 5012.19
Encroach Node=19090
       1 4987.35 5069.25
Encroach Node=18520
       1 4952.94 5032.16
Encroach Node=18330
       1    4982    5018
Encroach Node=18242
       1  4977.5  5022.5
Encroach Node=17888
       1 4905.47  5013.2
Encroach Node=17520
       1 4878.91  5008.2
Encroach Node=17020
       1 4907.02  5013.2
Encroach Node=16521
       1 4889.03  5013.2
Encroach Node=16020
       1  4829.7 5012.12
Encroach Node=15520
       1  4912.8 5014.53
Encroach Node=15058
       1 4909.08 5013.53
Encroach Node=14520
       1 4902.56 5027.95
Encroach Node=14020
       1  4985.4 5116.46
Encroach Node=13461
       1 4854.41  5014.6
Encroach Node=13020
       1 4863.21  5014.6
Encroach Node=12615
       1 4866.97  5014.6
Encroach Node=12483
       1    4970    5030
Encroach Node=12443
       1    4970    5026
Encroach Node=11979
       1  4984.7  5015.3
Encroach Node=11520
       1 4978.98  5015.3
Encroach Node=11095
       1  4975.8 5016.71
Encroach Node=10537
       1 4974.94  5015.7
Encroach Node=10020
       1  4984.3  5015.7
Encroach Node=9520
       1 4974.27  5016.7
Encroach Node=9020
       1  4984.3  5016.7
Encroach Node=8656
       1 4970.79  5022.8
Encroach Node=8266
       1    4975  5016.3
Encroach Node=7760
       1 4978.61  5016.3
Encroach Node=7449
       1 4967.85 5017.51
Encroach Node=7415
       1    4967 5017.46
Encroach Node=7004
       1 4880.92 5020.65
Encroach Node=6422
       1 4871.34  5016.3
Encroach Node=6020
       1 4875.64  5016.3
Encroach Node=5520
       1    4976 5108.38
Encroach Node=5020
       1 4978.94 5076.37
Encroach Node=4531
       1 4921.25  5025.8
Encroach Node=4020
       1 4871.06 5028.13
Encroach Node=3520
       1 4914.53 5073.86
Encroach Node=3020
       1 4878.81 5038.24
Encroach Node=2520
       1  4982.7 5075.61
Encroach Node=2098
       1 4945.21 5040.84
Encroach Node=1761
       1 4851.16  5017.3
Encroach Node=1406
       1 4913.74  5017.3
Encroach Node=1103
       1 4894.58  5017.3
Encroach Node=553
       1 4903.71  5017.3
Encroach Node=154
       1 4969.66 5093.74
Encroach Node=108
       1 4969.66 5093.74
Encroach Node=98
       1 4974.49 5117.33
Encroach Node=87
       1 4939.09 5126.76
BEGIN DESCRIPTION:
Floodway Run
END DESCRIPTION:
Computation Interval=1HOUR
Output Interval=1HOUR
Run HTab= 0
Run UNet= 0
Run PostProcess= 0
UNET Theta= 1
UNET Theta Warmup= 1
UNET ZTol= 0.02
UNET ZSATol= 0.05
UNET MxIter= 20
UNET MaxInSteps= 0
UNET DtIC= 0
UNET DtMin= 0
UNET MaxCRTS= 20
UNET WFStab= 2
UNET SFStab= 1
UNET WFX= 1
UNET SFX= 1
UNET DSS MLevel= 4
UNET DZMax Abort= 100
UNET Convert EG Bridges=-1
UNET Use Existing IB Tables=-1
UNET Froude Reduction=False
UNET Froude Limit= 1
UNET Froude Power= 10
Instantaneous Interval=1HOUR
Write IC File= 0
Echo Input=False
Echo Output=False
Write Detailed= 0
Detailed Automatic Start=False, 10

--- Little Forbush Creek.f01 (steady flow) ---

Flow Title=Floodway
Number of Profiles=2
Profile Names=100-year,100-FW
River Rch & RM= Little Forbush C,Reach-1,25979
     359     359
River Rch & RM= Little Forbush C,Reach-1,25272
     483     483
River Rch & RM= Little Forbush C,Reach-1,24014
     550     550
River Rch & RM= Little Forbush C,Reach-1,22520
     728     728
River Rch & RM= Little Forbush C,Reach-1,21020
     840     840
River Rch & RM= Little Forbush C,Reach-1,19090
    1030    1030
River Rch & RM= Little Forbush C,Reach-1,17888
    1244    1244
River Rch & RM= Little Forbush C,Reach-1,14520
    1405    1405
River Rch & RM= Little Forbush C,Reach-1,14020
    1571    1571
River Rch & RM= Little Forbush C,Reach-1,11979
    1705    1705
River Rch & RM= Little Forbush C,Reach-1,11095
    1785    1785
River Rch & RM= Little Forbush C,Reach-1,8266
    1914    1914
River Rch & RM= Little Forbush C,Reach-1,5520
    2007    2007
River Rch & RM= Little Forbush C,Reach-1,2520
    2158    2158
Boundary for River Rch & Prof#=Little Forbush C,Reach-1,1
Up Type=0
Dn Type=3
Dn Slope=0.0027
Boundary for River Rch & Prof#=Little Forbush C,Reach-1,2
Up Type=0
Dn Type=3
Dn Slope=0.0027

--- Little Forbush Creek.g01 (geometry) ---

Geom Title=Existing Conditions

River Reach=Little Forbush C,Reach-1
Reach XY= 30
      1527363.10       896531.49      1527642.98       895845.27
      1528006.46       895900.49      1528269.28       895299.60
      1529522.30       894268.62      1529977.25       892966.63
      1532518.99       891512.60      1532871.45       890646.20
      1534115.15       889723.91      1534943.13       889228.13
      1536220.59       888904.09      1536602.55       888570.26
      1537088.54       887207.00      1536855.64       886221.05
      1537176.25       886162.56      1537288.63       885943.81
      1537031.88       885450.13      1537080.78       885112.43
      1537241.50       884866.81      1537600.00       884793.88
      1537770.25       884450.56      1536828.38       883107.69
      1537284.13       882418.00      1536975.19       881935.63
      1536588.38       881749.63      1536623.25       880687.75
      1537191.40       879668.45      1536823.75       879068.38
      1536949.88       878410.63      1536381.09       877565.70

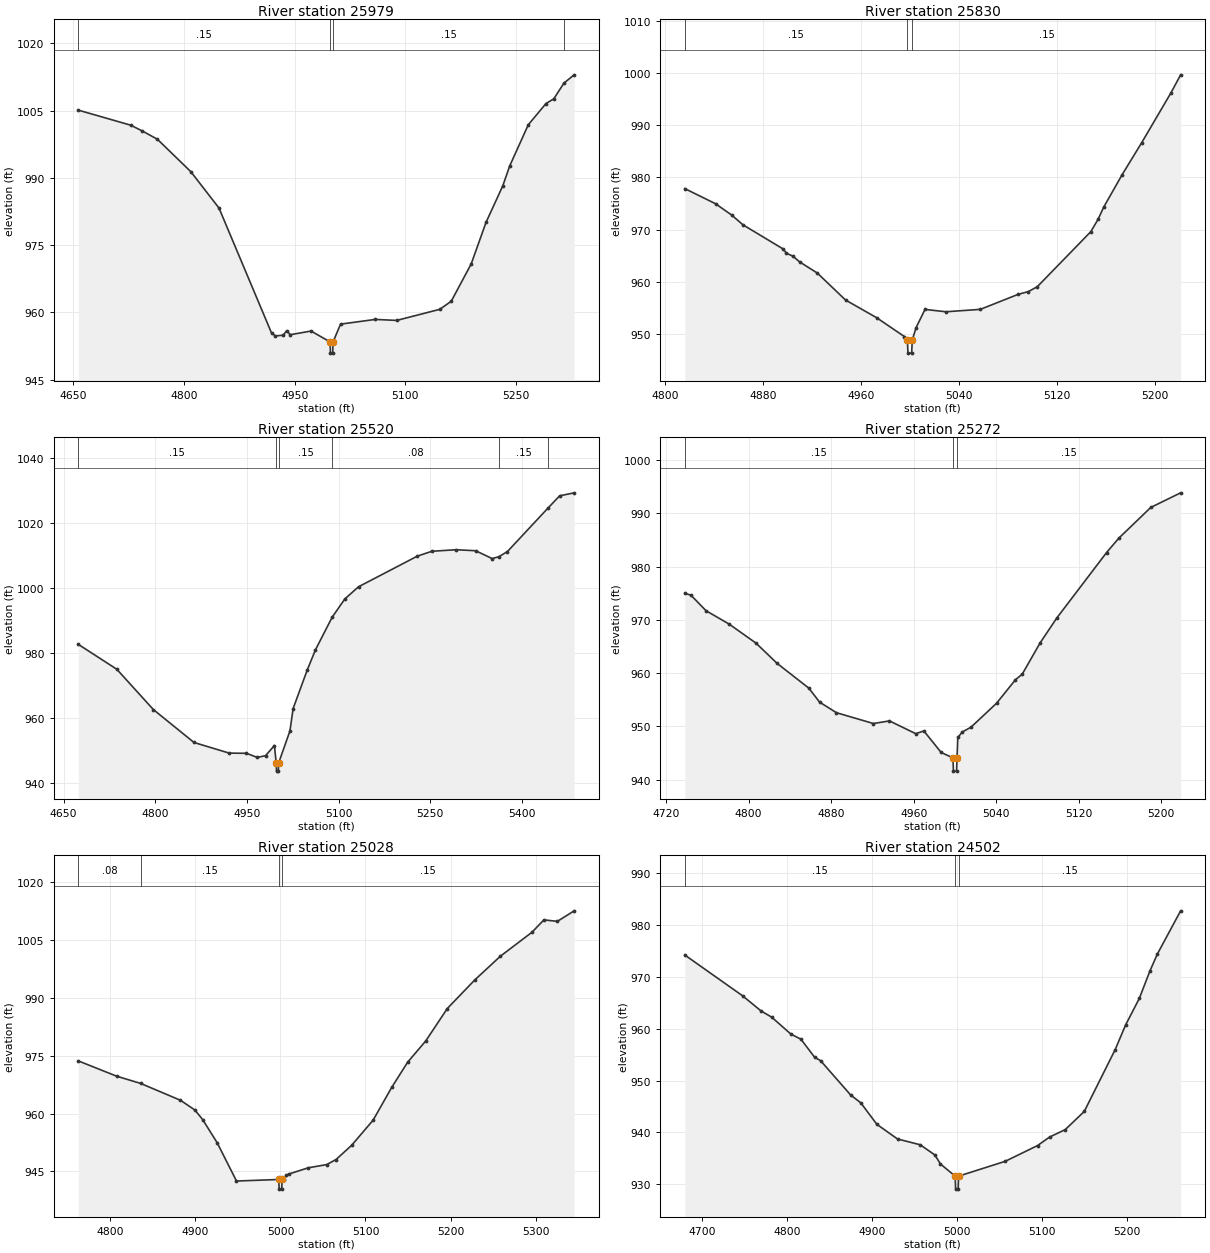
Type RM Length L Ch R = 1,25979,149,149,149
BEGIN DESCRIPTION:
Little Forbush Creek 52.0
END DESCRIPTION:
XS GIS Cut Line= 3
      1528193.68       896179.43      1528014.31       895854.88
      1527893.65       895579.36
#Sta/Elev= 30
  4657.0 1005.08  4727.9 1001.73  4743.4 1000.46  4764.1  998.59  4809.3  991.38
  4847.5  983.27  4918.7  955.41  4923.9  954.77  4934.4  954.92  4939.1  955.90
  4944.2  955.04  4972.2  955.85  4998.0  953.43  4998.5  950.93  5001.5  950.93
  5002.0  953.43  5012.2  957.39  5059.1  958.44  5088.2  958.22  5146.6  960.69
  5162.1  962.49  5189.1  970.79  5209.2  980.06  5232.0  988.24  5241.3  992.65
  5266.5 1001.83  5290.4 1006.55  5301.0 1007.60  5314.8 1011.11  5328.6 1012.95
#Mann=4,-1,0
  4657.0    0.15       0  4998.0   0.048       0  5002.0    0.15       0
  5314.8    0.08       0
Bank Sta=4998,5002
XS Rating Curve= 0
Exp/Cntr=0.3,0.1

Type RM Length L Ch R = 1,25830,310,310,310
BEGIN DESCRIPTION:
Little Forbush Creek 51.5
END DESCRIPTION:
XS GIS Cut Line= 3
      1528241.18       895888.60      1528186.01       895817.68
      1527933.89       895628.59
#Sta/Elev= 30
  4816.2  977.87  4841.3  974.97  4854.5  972.80  4863.7  970.93  4896.5  966.30
  4899.2  965.49  4904.6  964.90  4910.1  963.80  4924.4  961.69  4947.5  956.51
  4972.9  953.12  4995.6  949.50  4998.0  948.83  4998.5  946.33  5001.5  946.33
  5002.0  948.83  5005.1  951.21  5012.4  954.71  5029.5  954.26  5057.6  954.72
  5088.5  957.60  5096.9  958.13  5104.2  959.08  5147.9  969.63  5153.8  972.00
  5158.4  974.33  5173.5  980.57  5189.4  986.67  5213.4  996.27  5221.2  999.68
#Mann=3,-1,0
  4816.2    0.15       0  4998.0   0.048       0  5002.0    0.15       0
Bank Sta=4998,5002
XS Rating Curve= 0
Exp/Cntr=0.3,0.1

Type RM Length L Ch R = 1,25520,248,248,248
BEGIN DESCRIPTION:
Little Forbush Creek 51.0
END DESCRIPTION:
XS GIS Cut Line= 3
      1528474.97       895624.98      1528188.40       895469.98
      1527724.95       895324.99
#Sta/Elev= 30
  4674.2  982.74  4737.2  975.07  4797.0  962.66  4863.5  952.52  4921.1  949.25
  4949.3  949.19  4966.9  947.93  4980.5  948.45  4995.1  951.59  4998.0  946.20
  4998.5  943.70  5001.5  943.70  5002.0  946.20  5020.5  956.09  5025.7  962.97
  5048.6  974.75  5062.3  981.08  5089.6  991.12  5110.4  996.75  5132.7 1000.48
  5229.1 1009.93  5252.9 1011.42  5292.0 1011.89  5324.3 1011.59  5351.5 1009.16
  5362.6 1009.76  5376.4 1011.33  5443.6 1024.89  5461.9 1028.50  5485.6 1029.42
#Mann=6,-1,0
  4674.2    0.15       0  4998.0   0.048       0  5002.0    0.15       0
  5089.6    0.08       0  5362.6    0.15       0  5443.6    0.08       0
Bank Sta=4998,5002
XS Rating Curve= 0
Exp/Cntr=0.3,0.1

Type RM Length L Ch R = 1,25272,244,244,244
BEGIN DESCRIPTION:
Little Forbush Creek 50.5
END DESCRIPTION:
XS GIS Cut Line= 3
      1528474.80       895475.77      1528307.58       895270.72
      1528189.18       895090.05
#Sta/Elev= 30
  4738.1  974.97  4744.0  974.64  4758.7  971.71  4781.1  969.20  4807.1  965.63
  4827.6  961.82  4858.3  957.18  4868.8  954.54  4885.1  952.56  4920.9  950.53
  4936.5  951.02  4962.0  948.62  4969.8  949.14  4986.6  945.09  4998.0  944.09
  4998.5  941.59  5001.5  941.59  5002.0  944.09  5002.7  947.91  5007.2  948.96
  5015.4  949.82  5040.4  954.36  5058.5  958.73  5065.2  959.81  5082.6  965.70
  5098.8  970.38  5146.9  982.63  5158.8  985.34  5189.8  991.11  5218.7  993.85
#Mann=3,-1,0
  4738.1    0.15       0  4998.0   0.048       0  5002.0    0.15       0
Bank Sta=4998,5002
XS Rating Curve= 0
Exp/Cntr=0.3,0.1

Type RM Length L Ch R = 1,25028,526,526,526
BEGIN DESCRIPTION:
Little Forbush Creek 50.0
END DESCRIPTION:
XS GIS Cut Line= 3
      1528587.96       895343.76      1528495.52       895124.87
      1528362.03       894806.21
#Sta/Elev= 30
  4762.3  973.66  4807.5  969.69  4835.5  967.83  4882.4  963.46  4899.3  960.94
  4908.5  958.46  4925.6  952.44  4948.3  942.52  4998.0  942.92  4998.5  940.42
  5001.5  940.42  5002.0  942.92  5004.4  942.86  5007.1  944.01  5009.6  944.31
  5032.7  945.95  5054.4  946.78  5065.4  948.10  5083.8  951.80  5109.0  958.31
  5130.9  966.82  5149.6  973.33  5170.9  978.85  5196.2  987.24  5228.3  994.60
  5258.5 1000.78  5295.7 1007.00  5309.8 1010.22  5325.7 1009.84  5345.4 1012.57
#Mann=4,-1,0
  4762.3    0.08       0  4835.5    0.15       0  4998.0   0.048       0
  5002.0    0.15       0
Bank Sta=4998,5002
XS Rating Curve= 0
Exp/Cntr=0.3,0.1

Type RM Length L Ch R = 1,24502,278,278,278
BEGIN DESCRIPTION:
Little Forbush Creek 49.0
END DESCRIPTION:
XS GIS Cut Line= 3
      1529218.59       895042.93      1528947.02       894881.23
      1528775.02       894675.02
#Sta/Elev= 30
  4679.2  974.22  4747.3  966.36  4769.0  963.45  4781.7  962.23  4804.3  958.97
  4816.1  957.99  4832.3  954.50  4839.3  953.85  4874.7  947.24  4886.7  945.72
  4905.7  941.57  4930.0  938.75  4956.8  937.63  4974.1  935.66  4980.6  933.93
  4998.0  931.58  4998.5  929.08  5001.5  929.08  5002.0  931.58  5057.1  934.45
  5095.2  937.49  5109.2  939.11  5127.7  940.55  5150.2  944.06  5186.7  956.00
  5199.0  960.76  5215.1  965.85  5227.6  971.14  5236.3  974.39  5263.8  982.74
#Mann=3,-1,0
  4679.2    0.15       0  4998.0   0.048       0  5002.0    0.15       0
Bank Sta=4998,5002
XS Rating Curve= 0
Exp/Cntr=0.3,0.1

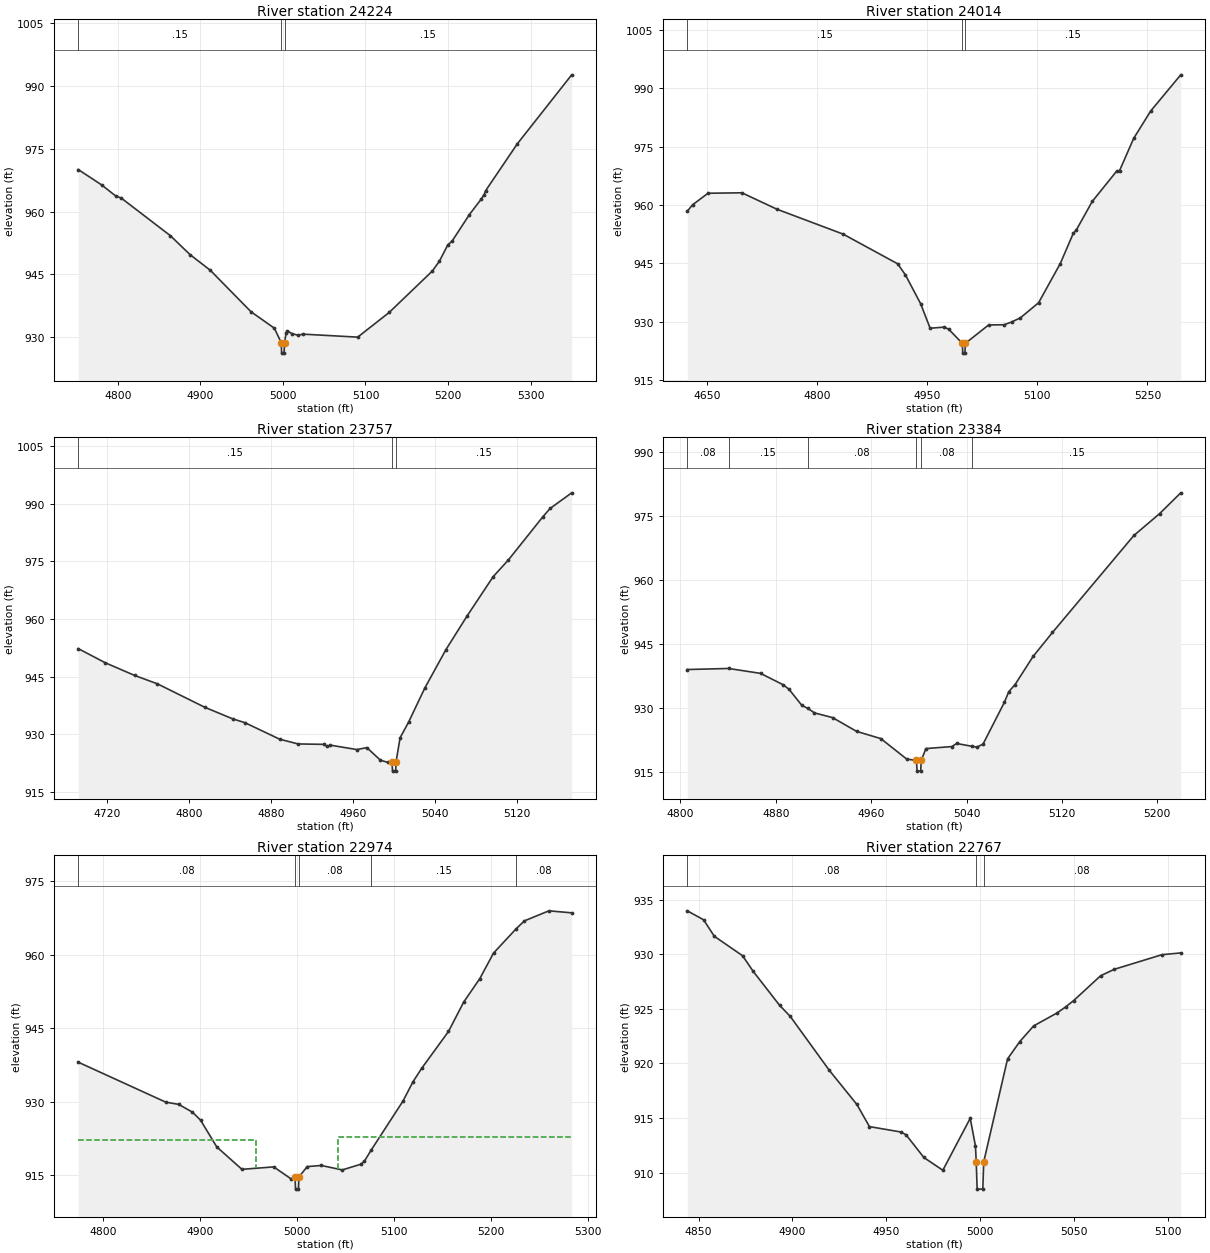
Type RM Length L Ch R = 1,24224,210,210,210
BEGIN DESCRIPTION:
Little Forbush Creek 48.5
END DESCRIPTION:
XS GIS Cut Line= 3
      1529326.44       894825.24      1529048.31       894616.65
      1528837.16       894482.74
#Sta/Elev= 30
  4752.1  970.07  4780.4  966.41  4797.6  963.74  4804.2  963.26  4863.6  954.29
  4887.7  949.72  4912.1  946.01  4961.3  936.12  4989.7  932.17  4998.0  928.72
  4998.5  926.22  5001.5  926.22  5002.0  928.72  5004.0  931.06  5005.5  931.53
  5010.8  930.89  5018.8  930.48  5023.9  930.76  5090.6  930.04  5128.7  935.93
  5181.0  945.82  5189.6  948.19  5199.8  952.09  5204.9  952.96  5225.9  959.31
  5240.1  962.98  5243.8  964.10  5245.5  965.00  5283.9  976.20  5349.8  992.69
#Mann=3,-1,0
  4752.1    0.15       0  4998.0   0.048       0  5002.0    0.15       0
Bank Sta=4998,5002
XS Rating Curve= 0
Exp/Cntr=0.3,0.1

Type RM Length L Ch R = 1,24014,257,257,257
BEGIN DESCRIPTION:
Little Forbush Creek 48.0
END DESCRIPTION:
XS GIS Cut Line= 3
      1529499.37       894717.88      1529206.02       894488.86
      1528950.64       894332.13
#Sta/Elev= 30
  4623.5  958.40  4630.8  960.06  4651.7  963.01  4697.8  963.13  4745.6  958.91
  4835.7  952.52  4909.9  944.90  4920.4  942.08  4941.3  934.62  4954.1  928.36
  4973.6  928.65  4979.6  928.07  4998.0  924.47  4998.5  921.97  5001.5  921.97
  5002.0  924.47  5033.8  929.21  5054.9  929.25  5065.1  929.97  5077.0  931.03
  5101.8  934.91  5131.3  944.96  5149.1  952.76  5152.8  953.47  5174.9  960.93
  5208.4  968.76  5212.0  968.81  5231.2  977.09  5254.5  984.15  5295.3  993.41
#Mann=3,-1,0
  4623.5    0.15       0  4998.0   0.048       0  5002.0    0.15       0
Bank Sta=4998,5002
XS Rating Curve= 0
Exp/Cntr=0.3,0.1

Type RM Length L Ch R = 1,23757,373,373,373
BEGIN DESCRIPTION:
Little Forbush Creek 47.5
END DESCRIPTION:
XS GIS Cut Line= 3
      1529383.10       894588.33      1529336.74       894268.99
      1529246.60       894137.64
#Sta/Elev= 30
  4691.5  952.30  4718.1  948.60  4746.5  945.34  4768.8  943.15  4815.3  937.03
  4842.4  934.04  4854.3  933.05  4888.2  928.76  4906.2  927.52  4931.2  927.41
  4934.6  926.87  4937.8  927.20  4963.8  926.05  4973.4  926.56  4986.7  923.29
  4993.6  922.75  4998.0  922.95  4998.5  920.45  5001.5  920.45  5002.0  922.95
  5005.9  929.12  5014.2  933.19  5030.1  942.08  5050.7  952.05  5071.1  960.69
  5096.7  970.97  5111.7  975.36  5145.5  986.63  5152.4  988.73  5173.5  992.80
#Mann=3,-1,0
  4691.5    0.15       0  4998.0   0.048       0  5002.0    0.15       0
Bank Sta=4998,5002
XS Rating Curve= 0
Exp/Cntr=0.3,0.1

Type RM Length L Ch R = 1,23384,410,410,410
BEGIN DESCRIPTION:
Little Forbush Creek 47.0
END DESCRIPTION:
XS GIS Cut Line= 4
      1529753.50       894211.60      1529649.83       894141.11
      1529554.46       894095.50      1529386.55       894022.94
#Sta/Elev= 30
  4805.7  939.05  4840.3  939.30  4867.2  938.15  4886.4  935.45  4891.2  934.39
  4901.8  930.66  4907.0  929.94  4912.4  928.90  4927.6  927.80  4947.7  924.58
  4968.1  922.88  4989.8  918.09  4998.0  917.77  4998.5  915.27  5001.5  915.27
  5002.0  917.77  5005.9  920.55  5027.7  921.02  5031.7  921.74  5044.9  921.06
  5048.6  920.89  5053.8  921.58  5071.7  931.35  5075.4  933.85  5080.7  935.53
  5095.8  942.11  5112.1  947.73  5180.4  970.43  5201.9  975.52  5219.7  980.41
#Mann=6,-1,0
  4805.7    0.08       0  4840.3    0.15       0  4907.0    0.08       0
  4998.0   0.048       0  5002.0    0.08       0  5044.9    0.15       0
Bank Sta=4998,5002
XS Rating Curve= 0
Exp/Cntr=0.3,0.1

Type RM Length L Ch R = 1,22974,207,207,207
BEGIN DESCRIPTION:
Little Forbush Creek 46.0
END DESCRIPTION:
XS GIS Cut Line= 3
      1529938.65       893701.49      1529624.15       893742.35
      1529434.50       893772.01
#Sta/Elev= 30
  4774.3  938.11  4864.6  929.95  4878.0  929.49  4892.2  927.90  4900.6  926.25
  4917.2  920.82  4943.2  916.23  4976.0  916.73  4994.3  914.23  4998.0  914.69
  4998.5  912.19  5001.5  912.19  5002.0  914.69  5010.6  916.79  5025.1  917.02
  5046.7  916.11  5065.6  917.26  5069.4  917.85  5076.5  920.15  5109.3  930.15
  5119.7  934.12  5128.6  936.84  5156.3  944.38  5172.0  950.38  5188.6  955.17
  5202.8  960.39  5225.6  965.24  5234.5  966.95  5259.9  969.01  5283.4  968.60
#Mann=5,-1,0
  4774.3    0.08       0  4998.0   0.048       0  5002.0    0.08       0
  5076.5    0.15       0  5225.6    0.08       0
#XS Ineff=2,0
    0.00 4958.20  922.21 5041.80    0.00  922.84
Permanent Ineff=
       F       F
Bank Sta=4998,5002
XS Rating Curve= 0
Exp/Cntr=0.3,0.1

Type RM Length L Ch R = 1,22767,247,247,247
BEGIN DESCRIPTION:
Little Forbush Creek 45.5
END DESCRIPTION:
XS GIS Cut Line= 4
      1529839.40       893615.98      1529709.10       893531.07
      1529688.92       893521.82      1529603.98       893514.25
#Sta/Elev= 30
  4844.0  933.99  4852.7  933.17  4858.4  931.66  4873.5  929.87  4879.1  928.45
  4893.2  925.33  4898.9  924.31  4919.7  919.37  4934.4  916.24  4941.1  914.21
  4958.1  913.71  4960.7  913.44  4970.1  911.38  4980.2  910.21  4994.8  914.97
  4997.6  912.43  4998.0  910.98  4998.5  908.48  5001.5  908.48  5002.0  910.98
  5014.7  920.42  5021.2  922.00  5028.6  923.44  5041.1  924.63  5045.7  925.19
  5049.9  925.76  5064.3  928.04  5071.6  928.63  5097.0  929.97  5107.0  930.13
#Mann=3,-1,0
  4844.0    0.08       0  4998.0   0.048       0  5002.0    0.08       0
Bank Sta=4998,5002
XS Rating Curve= 0
Exp/Cntr=0.3,0.1

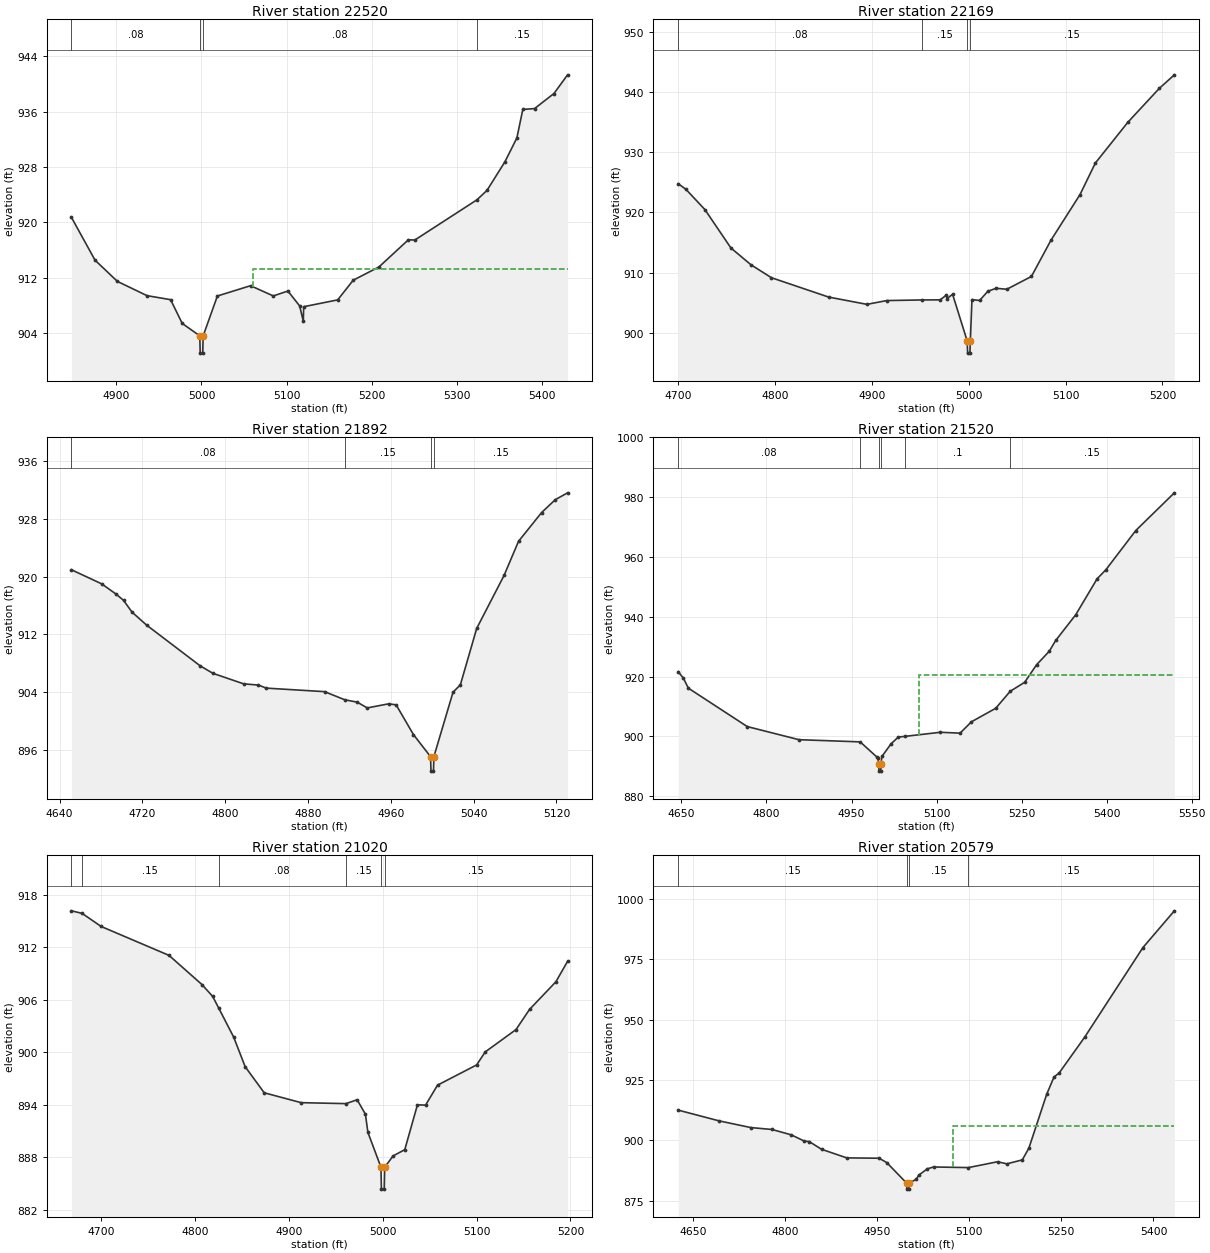
Type RM Length L Ch R = 1,22520,351,351,351
BEGIN DESCRIPTION:
Little Forbush Creek 45.0
END DESCRIPTION:
XS GIS Cut Line= 3
      1530024.97       893474.98      1529894.18       893395.98
      1529524.97       893174.98
#Sta/Elev= 30
  4847.2  920.69  4874.9  914.51  4901.2  911.44  4936.0  909.38  4963.7  908.80
  4977.4  905.36  4998.0  903.57  4998.5  901.07  5001.5  901.07  5002.0  903.57
  5018.7  909.33  5057.7  910.82  5084.4  909.34  5101.6  910.05  5115.4  907.89
  5119.7  905.68  5120.1  907.78  5160.1  908.77  5178.3  911.61  5208.6  913.53
  5243.2  917.46  5250.7  917.42  5323.8  923.24  5335.5  924.59  5356.5  928.70
  5370.7  932.18  5377.7  936.31  5391.5  936.43  5414.3  938.61  5430.3  941.31
#Mann=4,-1,0
  4847.2    0.08       0  4998.0   0.048       0  5002.0    0.08       0
  5323.8    0.15       0
#XS Ineff=2,0
       0                 5061.00    0.00  913.20
Permanent Ineff=
       F       F
Bank Sta=4998,5002
XS Rating Curve= 0
Exp/Cntr=0.3,0.1

Type RM Length L Ch R = 1,22169,277,277,277
BEGIN DESCRIPTION:
Little Forbush Creek 44.5
END DESCRIPTION:
XS GIS Cut Line= 5
      1530191.37       893241.35      1530090.66       893121.75
      1529987.97       893058.91      1529919.49       893041.80
      1529764.46       892985.42
#Sta/Elev= 30
  4700.0  924.76  4707.9  923.84  4727.5  920.47  4754.4  914.08  4775.1  911.29
  4796.2  909.14  4855.3  905.92  4894.8  904.71  4915.4  905.34  4951.5  905.44
  4970.5  905.46  4976.7  906.23  4977.6  905.68  4983.3  906.38  4998.4  898.60
  4998.8  896.60  5001.2  896.60  5001.6  898.60  5003.3  905.50  5011.2  905.35
  5019.7  906.89  5028.3  907.38  5039.3  907.22  5064.7  909.35  5084.9  915.38
  5114.8  922.94  5130.7  928.20  5164.2  934.97  5196.7  940.61  5212.3  942.87
#Mann=4,-1,0
  4700.0    0.08       0  4951.5    0.15       0  4998.4   0.048       0
  5001.6    0.15       0
Bank Sta=4998.4,5001.6
XS Rating Curve= 0
Exp/Cntr=0.3,0.1

Type RM Length L Ch R = 1,21892,372,372,372
BEGIN DESCRIPTION:
Little Forbush Creek 43.5
END DESCRIPTION:
XS GIS Cut Line= 3
      1530285.57       893169.27      1530187.87       892949.90
      1530055.15       892750.83
#Sta/Elev= 30
  4651.4  920.95  4680.6  919.00  4694.6  917.57  4701.7  916.72  4709.9  915.09
  4724.0  913.29  4775.9  907.64  4788.2  906.61  4817.8  905.16  4832.1  904.99
  4839.6  904.57  4896.0  904.08  4915.6  902.95  4927.5  902.63  4937.2  901.83
  4957.8  902.39  4965.1  902.26  4981.9  898.13  4998.4  895.08  4998.8  893.08
  5001.2  893.08  5001.6  895.08  5020.1  904.00  5027.2  905.03  5043.0  912.84
  5069.4  920.16  5083.4  924.89  5105.7  928.87  5118.9  930.65  5130.8  931.60
#Mann=4,-1,0
  4651.4    0.08       0  4915.6    0.15       0  4998.4   0.048       0
  5001.6    0.15       0
Bank Sta=4998.4,5001.6
XS Rating Curve= 0
Exp/Cntr=0.3,0.1

Type RM Length L Ch R = 1,21520,500,500,500
BEGIN DESCRIPTION:
Little Forbush Creek 43.0
END DESCRIPTION:
XS GIS Cut Line= 3
      1530625.00       893024.99      1530454.33       892713.03
      1530175.01       892275.01
#Sta/Elev= 30
  4644.4  921.60  4653.5  919.45  4662.2  916.11  4766.1  903.25  4857.4  898.86
  4965.3  898.13  4995.6  892.92  4996.7  892.57  4998.0  890.84  4998.5  888.34
  5001.5  888.34  5002.0  890.84  5003.6  893.24  5019.9  897.51  5032.6  899.75
  5044.2  899.97  5106.8  901.34  5141.5  901.05  5161.6  904.85  5204.3  909.36
  5230.0  915.07  5255.4  918.06  5276.4  923.93  5298.7  928.42  5310.4  932.12
  5345.5  940.67  5383.4  952.75  5398.4  955.65  5451.4  968.85  5519.5  981.47
#Mann=6,-1,0
  4644.4    0.08       0  4965.3    0.15       0  4998.0   0.048       0
  5002.0    0.15       0  5044.2     0.1       0  5230.0    0.15       0
#XS Ineff=2,0
       0                 5068.70    0.00  920.43
Permanent Ineff=
       F       F
Bank Sta=4998,5002
XS Rating Curve= 0
Exp/Cntr=0.3,0.1

Type RM Length L Ch R = 1,21020,441,441,441
BEGIN DESCRIPTION:
Little Forbush Creek 42.0
END DESCRIPTION:
XS GIS Cut Line= 3
      1531063.72       892714.73      1530859.57       892452.92
      1530775.00       892275.00
#Sta/Elev= 30
  4668.0  916.17  4679.3  915.88  4699.7  914.38  4772.0  911.08  4807.1  907.75
  4818.5  906.40  4824.8  905.10  4841.0  901.73  4853.2  898.36  4873.5  895.38
  4912.9  894.25  4960.6  894.14  4972.6  894.58  4981.4  892.94  4984.1  890.85
  4998.0  886.87  4998.5  884.37  5001.5  884.37  5002.0  886.87  5010.9  888.16
  5023.4  888.88  5036.9  894.00  5045.6  893.97  5058.3  896.25  5100.0  898.56
  5109.2  900.05  5142.0  902.60  5156.4  904.90  5184.5  908.06  5197.0  910.40
#Mann=6,-1,0
  4668.0    0.08       0  4679.3    0.15       0  4824.8    0.08       0
  4960.6    0.15       0  4998.0   0.048       0  5002.0    0.15       0
Bank Sta=4998,5002
XS Rating Curve= 0
Exp/Cntr=0.3,0.1

Type RM Length L Ch R = 1,20579,559,559,559
BEGIN DESCRIPTION:
Little Forbush Creek 41.0
END DESCRIPTION:
XS GIS Cut Line= 3
      1531428.63       892499.14      1531265.57       892274.13
      1530971.64       891833.09
#Sta/Elev= 30
  4626.1  912.53  4692.3  908.10  4744.4  905.30  4778.9  904.51  4810.3  902.27
  4831.6  899.67  4839.3  899.51  4859.4  896.31  4900.5  892.74  4953.2  892.60
  4965.7  890.78  4998.0  882.29  4998.5  879.79  5001.5  879.79  5002.0  882.29
  5013.6  883.84  5017.9  885.62  5031.8  888.22  5042.0  888.97  5098.6  888.72
  5146.1  891.14  5161.1  890.27  5186.4  891.91  5197.1  896.79  5226.1  919.11
  5238.0  926.26  5246.3  927.90  5288.0  942.79  5382.8  979.91  5434.0  995.14
#Mann=4,-1,0
  4626.1    0.15       0  4998.0   0.048       0  5002.0    0.15       0
  5098.6    0.15       0
#XS Ineff=2,0
       0                 5074.10    0.00  905.85
Permanent Ineff=
       F       F
Bank Sta=4998,5002
XS Rating Curve= 0
Exp/Cntr=0.3,0.1

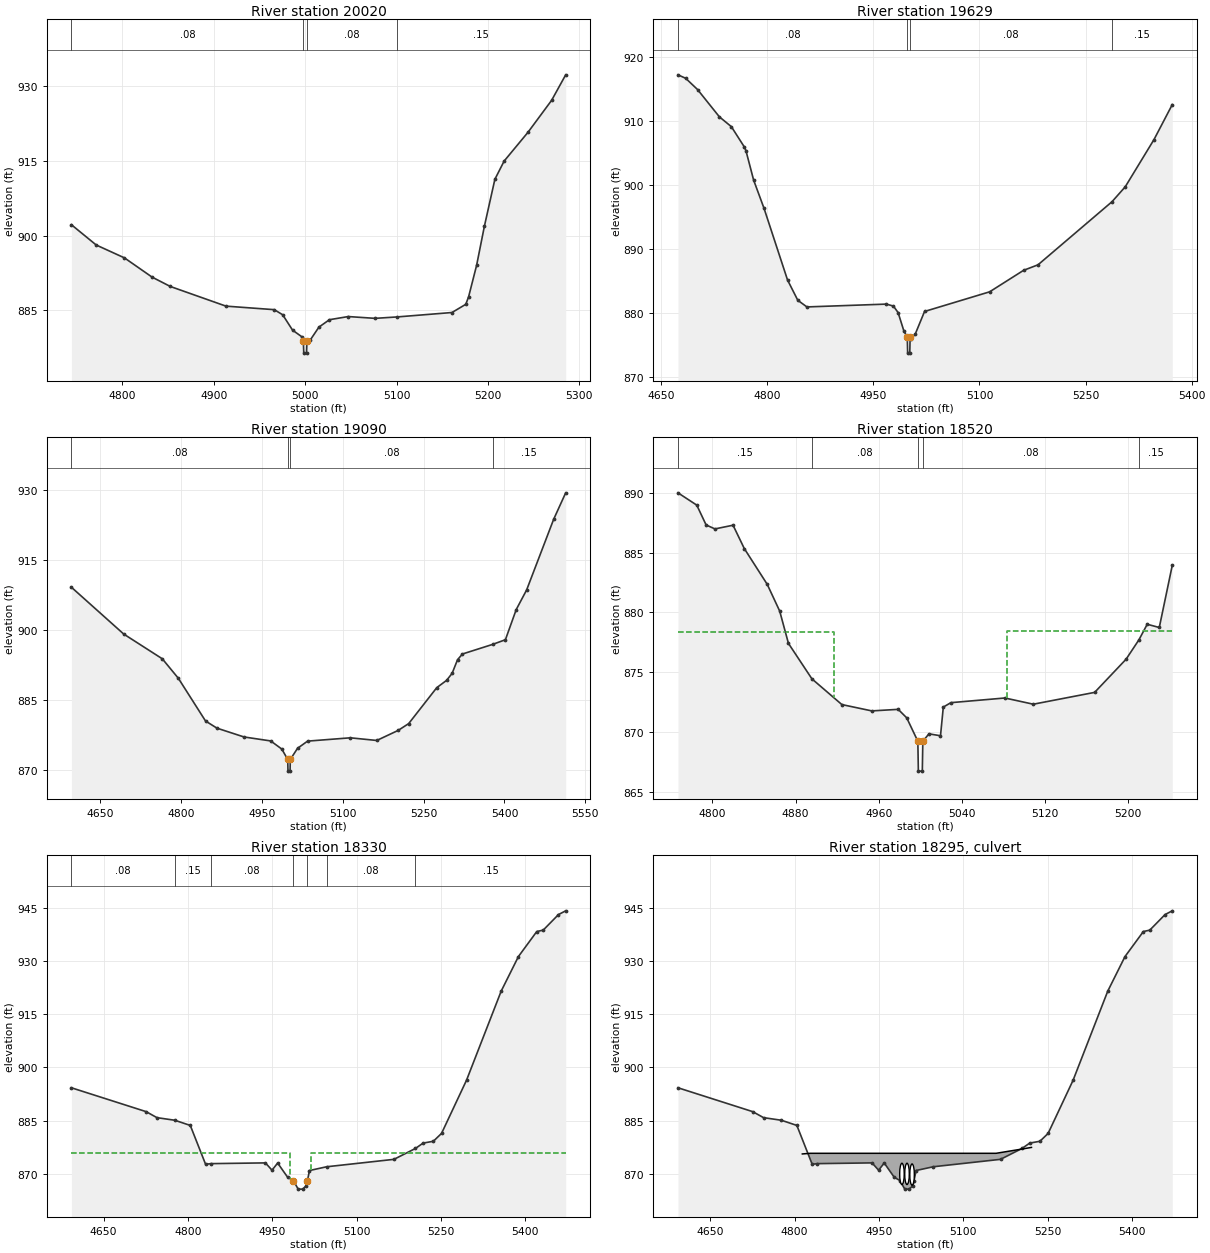
Type RM Length L Ch R = 1,20020,391,391,391
BEGIN DESCRIPTION:
Little Forbush Creek 40.0
END DESCRIPTION:
XS GIS Cut Line= 3
      1531825.03       892125.04      1531689.83       891907.77
      1531525.01       891675.02
#Sta/Elev= 30
  4744.1  902.19  4771.3  898.12  4802.2  895.54  4832.4  891.69  4852.4  889.81
  4913.3  885.87  4966.2  885.16  4975.4  884.14  4986.2  881.06  4996.2  879.75
  4998.0  878.95  4998.5  876.45  5001.5  876.45  5002.0  878.95  5005.8  879.14
  5015.1  881.67  5026.6  883.15  5047.2  883.78  5076.5  883.42  5100.4  883.70
  5160.7  884.59  5175.8  886.23  5178.9  887.72  5187.7  894.06  5196.2  901.88
  5207.7  911.30  5217.8  914.94  5244.0  920.73  5269.8  927.12  5285.2  932.23
#Mann=4,-1,0
  4744.1    0.08       0  4998.0   0.048       0  5002.0    0.08       0
  5100.4    0.15       0
Bank Sta=4998,5002
XS Rating Curve= 0
Exp/Cntr=0.3,0.1

Type RM Length L Ch R = 1,19629,539,539,539
BEGIN DESCRIPTION:
Little Forbush Creek 39.0
END DESCRIPTION:
XS GIS Cut Line= 3
      1532195.41       892051.33      1532071.48       891794.30
      1531856.73       891440.98
#Sta/Elev= 30
  4673.8  917.18  4684.7  916.64  4701.5  914.88  4732.4  910.61  4749.3  909.08
  4767.6  905.91  4769.9  905.33  4780.8  900.72  4795.5  896.31  4828.7  885.12
  4843.2  881.95  4856.1  880.91  4968.5  881.35  4978.4  881.04  4985.0  880.03
  4993.3  877.11  4998.0  876.19  4998.5  873.69  5001.5  873.69  5002.0  876.19
  5003.5  875.95  5009.4  876.71  5022.4  880.20  5114.4  883.27  5162.4  886.63
  5182.8  887.49  5287.4  897.35  5306.1  899.68  5346.8  907.07  5372.6  912.53
#Mann=4,-1,0
  4673.8    0.08       0  4998.0   0.048       0  5002.0    0.08       0
  5287.4    0.15       0
Bank Sta=4998,5002
XS Rating Curve= 0
Exp/Cntr=0.3,0.1

Type RM Length L Ch R = 1,19090,570,570,570
BEGIN DESCRIPTION:
Little Forbush Creek 38.0
END DESCRIPTION:
XS GIS Cut Line= 3
      1532844.50       891753.22      1532555.98       891532.19
      1532113.68       891198.36
#Sta/Elev= 30
  4596.0  909.10  4693.1  899.07  4764.8  893.76  4794.6  889.58  4845.0  880.44
  4866.2  878.90  4916.5  877.01  4966.0  876.16  4986.6  874.42  4997.6  872.19
  4998.1  869.69  5001.9  869.69  5002.4  872.19  5015.8  874.58  5034.5  876.12
  5113.8  876.83  5162.9  876.26  5202.5  878.41  5222.1  879.87  5274.3  887.58
  5292.5  889.14  5302.8  890.65  5312.8  893.56  5321.9  894.79  5378.0  896.85
  5401.7  897.85  5421.8  904.32  5441.1  908.52  5491.3  923.67  5513.6  929.33
#Mann=4,-1,0
  4596.0    0.08       0  4997.6   0.048       0  5002.4    0.08       0
  5378.0    0.15       0
Bank Sta=4997.6,5002.4
XS Rating Curve= 0
Exp/Cntr=0.3,0.1

Type RM Length L Ch R = 1,18520,190,190,190
BEGIN DESCRIPTION:
Little Forbush Creek 37.0
END DESCRIPTION:
XS GIS Cut Line= 3
      1533024.97       891074.99      1532798.84       891018.02
      1532575.00       890925.00
#Sta/Elev= 30
  4766.8  890.00  4784.9  888.97  4793.9  887.31  4802.4  886.98  4819.8  887.29
  4830.6  885.34  4852.7  882.34  4864.7  880.10  4873.1  877.40  4895.7  874.43
  4924.5  872.28  4953.3  871.75  4978.7  871.88  4986.9  871.17  4997.6  869.21
  4998.1  866.71  5001.9  866.71  5002.4  869.21  5008.3  869.83  5019.4  869.67
  5022.1  872.07  5029.4  872.44  5081.4  872.83  5108.7  872.31  5167.7  873.30
  5198.0  876.08  5210.4  877.71  5218.3  879.00  5229.9  878.73  5242.4  883.93
#Mann=5,-1,0
  4766.8    0.15       0  4895.7    0.08       0  4997.6   0.048       0
  5002.4    0.08       0  5210.4    0.15       0
#XS Ineff=2,0
    0.00 4916.80  878.35 5083.20    0.00  878.44
Permanent Ineff=
       F       F
Bank Sta=4997.6,5002.4
XS Rating Curve= 0
Exp/Cntr=0.5,0.3

Type RM Length L Ch R = 1,18330,88,88,88
BEGIN DESCRIPTION:
Moccasin Gap Rd (LFC) US
END DESCRIPTION:
XS GIS Cut Line= 5
      1533216.73       890989.85      1532973.71       890845.95
      1532849.02       890836.60      1532608.06       890767.62
      1532387.43       890762.64
#Sta/Elev= 30
  4592.8  894.26  4725.6  887.54  4745.0  885.84  4776.7  885.11  4804.2  883.65
  4831.4  872.71  4840.8  872.89  4937.8  873.10  4949.5  871.04  4959.5  873.06
  4977.2  869.07  4987.5  868.11  4996.0  865.71  5004.0  865.71  5010.3  866.66
  5012.5  868.11  5016.1  870.95  5046.7  872.01  5166.3  874.10  5204.4  877.16
  5218.2  878.68  5236.3  879.19  5250.9  881.41  5295.3  896.39  5356.9  921.48
  5387.6  931.23  5420.2  938.27  5431.6  938.66  5458.8  943.05  5471.6  944.10
#Mann=7,-1,0
  4592.8    0.08       0  4776.7    0.15       0  4840.8    0.08       0
  4987.5   0.048       0  5012.5    0.08       0  5046.7    0.08       0
  5204.4    0.15       0
#XS Ineff=2,0
    0.00 4982.00  875.80 5018.00    0.00  875.80
Permanent Ineff=
       F       F
Bank Sta=4987.5,5012.5
XS Rating Curve= 0
Exp/Cntr=0.5,0.3

Type RM Length L Ch R =2,18295,,,
BEGIN DESCRIPTION:
Moccasin Gap Rd (LFC) TOR
Structure ID: LDS_LFC_06
Approximate Survey Structure
END DESCRIPTION:
Bridge Culvert--1,0,-1,-1,0
Deck Dist Width WeirC Skew NumUp NumDn MinLoCord MaxHiCord MaxSubmerge Is_Ogee
5,60,3,,5,5,,,0.95,0,1,1,,,
  4813.9  4827.9  5158.3  5202.9  5221.3
  875.62  875.80  875.80  876.96  877.46
  845.71  845.71  845.71  845.71  845.71
  4813.9  4827.9  5158.3  5202.9  5221.3
  875.62  875.80  875.80  876.96  877.46
  845.41  845.41  845.41  845.41  845.41
Culvert=4,6,8,60,0.012,0.5,1,29,1,867,4991,866.5,4991,Culvert #1,0,5
Culvert Bottom n=0.012
Culvert Bottom Depth=0
Culvert Depth Blocked=0
Culvert=4,6,8,60,0.012,0.5,1,29,1,867,5000,866.5,5000,Culvert #2,0,5
Culvert Bottom n=0.012
Culvert Bottom Depth=0
Culvert Depth Blocked=0
Culvert=4,6,8,60,0.012,0.5,1,29,1,866.8,5009,866.5,5009,Culvert #3,0,5
Culvert Bottom n=0.012
Culvert Bottom Depth=0
Culvert Depth Blocked=0
BC Design=,,0,,0,,,,,,

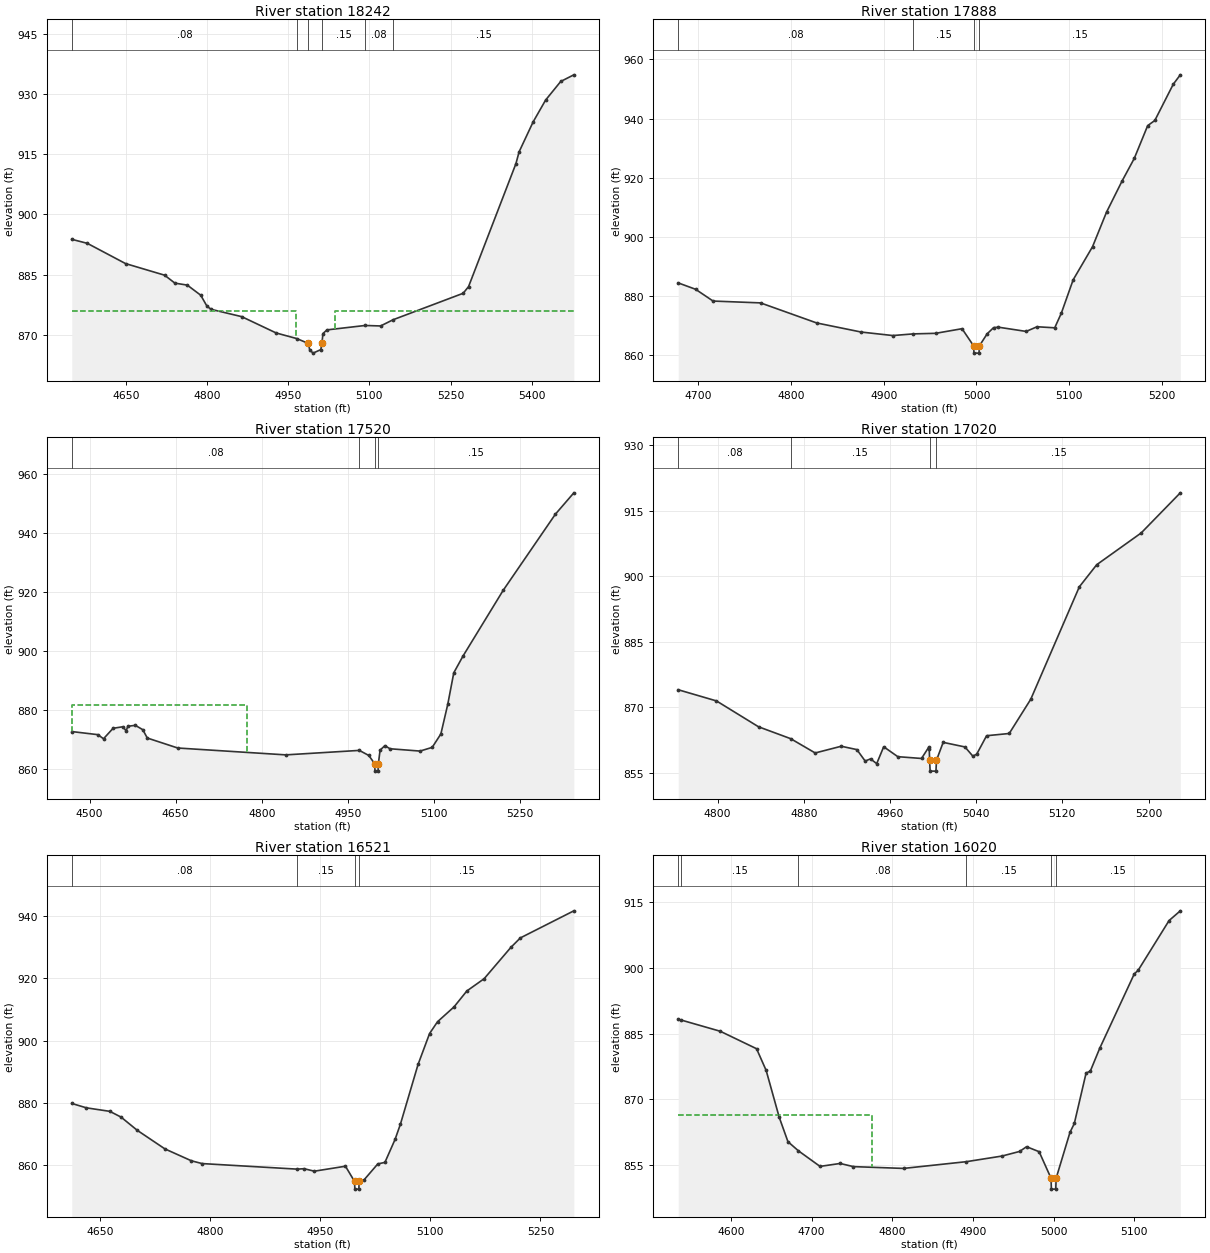
Type RM Length L Ch R = 1,18242,354,354,354
BEGIN DESCRIPTION:
Moccasin Gap Rd (LFC) DS
END DESCRIPTION:
XS GIS Cut Line= 5
      1533261.50       890971.60      1532992.84       890797.47
      1532888.35       890754.35      1532792.16       890742.74
      1532395.73       890716.20
#Sta/Elev= 30
  4550.4  893.77  4579.1  892.77  4649.8  887.72  4721.9  884.83  4740.9  882.85
  4763.8  882.36  4788.6  879.84  4800.4  877.04  4808.4  876.30  4864.3  874.50
  4928.0  870.43  4966.2  869.03  4987.5  867.81  4989.8  866.26  4996.0  865.41
  5010.4  866.28  5012.5  867.81  5014.3  870.28  5021.8  871.20  5092.2  872.30
  5120.8  872.18  5144.3  873.75  5273.3  880.32  5283.3  881.98  5370.8  912.62
  5376.7  915.58  5402.6  923.03  5425.7  928.48  5453.6  933.11  5477.8  934.76
#Mann=6,-1,0
  4550.4    0.08       0  4966.2    0.15       0  4987.5   0.048       0
  5012.5    0.15       0  5092.2    0.08       0  5144.3    0.15       0
#XS Ineff=2,0
    0.00 4964.00  875.80 5036.00    0.00  875.80
Permanent Ineff=
       F       F
Bank Sta=4987.5,5012.5
XS Rating Curve= 0
Exp/Cntr=0.5,0.3

Type RM Length L Ch R = 1,17888,368,368,368
BEGIN DESCRIPTION:
Little Forbush Creek 36.0
END DESCRIPTION:
XS GIS Cut Line= 3
      1533254.59       890818.82      1533038.83       890470.35
      1532954.64       890368.89
#Sta/Elev= 30
  4678.2  884.51  4696.9  882.36  4715.8  878.38  4767.0  877.76  4827.6  870.98
  4875.6  867.91  4909.7  866.73  4931.9  867.29  4955.9  867.48  4984.4  869.04
  4996.8  863.29  4997.3  860.79  5002.7  860.79  5003.2  863.29  5011.5  867.31
  5018.4  869.39  5023.7  869.55  5053.6  868.12  5065.3  869.70  5084.4  869.34
  5091.6  874.34  5104.3  885.56  5125.2  896.74  5140.3  908.42  5156.9  918.83
  5170.2  926.55  5184.7  937.64  5192.4  939.38  5212.3  951.63  5219.9  954.80
#Mann=4,-1,0
  4678.2    0.08       0  4931.9    0.15       0  4996.8   0.048       0
  5003.2    0.15       0
Bank Sta=4996.8,5003.2
XS Rating Curve= 0
Exp/Cntr=0.3,0.1

Type RM Length L Ch R = 1,17520,500,500,500
BEGIN DESCRIPTION:
Little Forbush Creek 35.0
END DESCRIPTION:
XS GIS Cut Line= 3
      1533625.00       890775.00      1533358.21       890315.89
      1533174.99       890024.98
#Sta/Elev= 30
  4469.0  872.58  4514.6  871.52  4524.3  870.13  4541.0  873.69  4558.1  874.21
  4563.8  872.80  4566.6  874.37  4579.7  874.69  4592.7  873.22  4600.6  870.38
  4653.7  866.99  4841.9  864.66  4970.1  866.18  4986.6  864.45  4996.8  861.64
  4997.3  859.14  5002.7  859.14  5003.2  861.64  5006.2  866.27  5014.6  867.79
  5023.4  866.74  5075.8  865.95  5097.0  867.21  5112.1  871.76  5124.1  881.81
  5134.6  892.54  5150.6  898.20  5220.5  920.49  5311.7  946.42  5343.8  953.66
#Mann=4,-1,0
  4469.0    0.08       0  4970.1    0.15       0  4996.8   0.048       0
  5003.2    0.15       0
#XS Ineff=2,0
    0.00 4773.60  881.57               0
Permanent Ineff=
       F       F
Bank Sta=4996.8,5003.2
XS Rating Curve= 0
Exp/Cntr=0.3,0.1

Type RM Length L Ch R = 1,17020,499,499,499
BEGIN DESCRIPTION:
Little Forbush Creek 34.0
END DESCRIPTION:
XS GIS Cut Line= 3
      1533924.99       890174.99      1533746.83       890019.46
      1533624.99       889824.98
#Sta/Elev= 30
  4763.5  874.03  4799.0  871.47  4838.0  865.55  4867.9  862.82  4890.6  859.55
  4914.8  861.09  4929.3  860.32  4937.0  857.70  4942.0  858.20  4947.7  857.10
  4954.2  860.97  4967.3  858.70  4989.3  858.29  4995.9  860.83  4996.5  860.37
  4996.8  857.89  4997.3  855.39  5002.7  855.39  5003.2  857.89  5009.4  861.98
  5029.6  860.93  5036.9  858.84  5040.5  859.26  5049.7  863.50  5070.7  864.01
  5090.7  871.86  5135.8  897.62  5151.9  902.67  5193.2  909.95  5229.5  919.14
#Mann=4,-1,0
  4763.5    0.08       0  4867.9    0.15       0  4996.8   0.048       0
  5003.2    0.15       0
Bank Sta=4996.8,5003.2
XS Rating Curve= 0
Exp/Cntr=0.3,0.1

Type RM Length L Ch R = 1,16521,501,501,501
BEGIN DESCRIPTION:
Little Forbush Creek 33.0
END DESCRIPTION:
XS GIS Cut Line= 3
      1534297.88       890066.62      1534134.30       889710.24
      1534057.62       889429.14
#Sta/Elev= 30
  4611.9  879.77  4631.8  878.36  4663.7  877.23  4679.0  875.38  4701.1  871.12
  4738.7  865.15  4774.8  861.32  4789.3  860.43  4918.8  858.64  4928.1  858.78
  4942.1  857.98  4984.5  859.58  4996.8  854.71  4997.3  852.21  5002.7  852.21
  5003.2  854.71  5009.7  855.16  5028.5  860.32  5038.2  860.81  5052.0  868.19
  5059.3  873.10  5083.3  892.30  5099.0  902.26  5109.8  906.05  5132.3  910.83
  5149.7  915.94  5173.3  919.90  5209.6  929.95  5222.6  933.02  5295.4  941.73
#Mann=4,-1,0
  4611.9    0.08       0  4918.8    0.15       0  4996.8   0.048       0
  5003.2    0.15       0
Bank Sta=4996.8,5003.2
XS Rating Curve= 0
Exp/Cntr=0.3,0.1

Type RM Length L Ch R = 1,16020,500,500,500
BEGIN DESCRIPTION:
Little Forbush Creek 32.0
END DESCRIPTION:
XS GIS Cut Line= 3
      1534800.68       889855.45      1534559.71       889457.41
      1534442.42       889352.88
#Sta/Elev= 30
  4534.7  888.27  4537.9  888.13  4586.8  885.55  4631.8  881.57  4643.7  876.62
  4659.9  865.94  4670.7  860.38  4683.7  858.30  4710.5  854.75  4735.4  855.42
  4751.8  854.70  4814.0  854.29  4892.0  855.83  4936.1  857.11  4957.9  858.16
  4966.5  859.24  4982.1  858.10  4996.8  852.07  4997.3  849.57  5002.7  849.57
  5003.2  852.07  5020.3  862.49  5025.7  864.53  5040.3  876.03  5045.5  876.45
  5057.1  881.63  5100.0  898.61  5104.9  899.46  5143.2  910.79  5157.1  913.00
#Mann=6,-1,0
  4534.7    0.08       0  4537.9    0.15       0  4683.7    0.08       0
  4892.0    0.15       0  4996.8   0.048       0  5003.2    0.15       0
#XS Ineff=2,0
    0.00 4774.50  866.54               0
Permanent Ineff=
       F       F
Bank Sta=4996.8,5003.2
XS Rating Curve= 0
Exp/Cntr=0.3,0.1