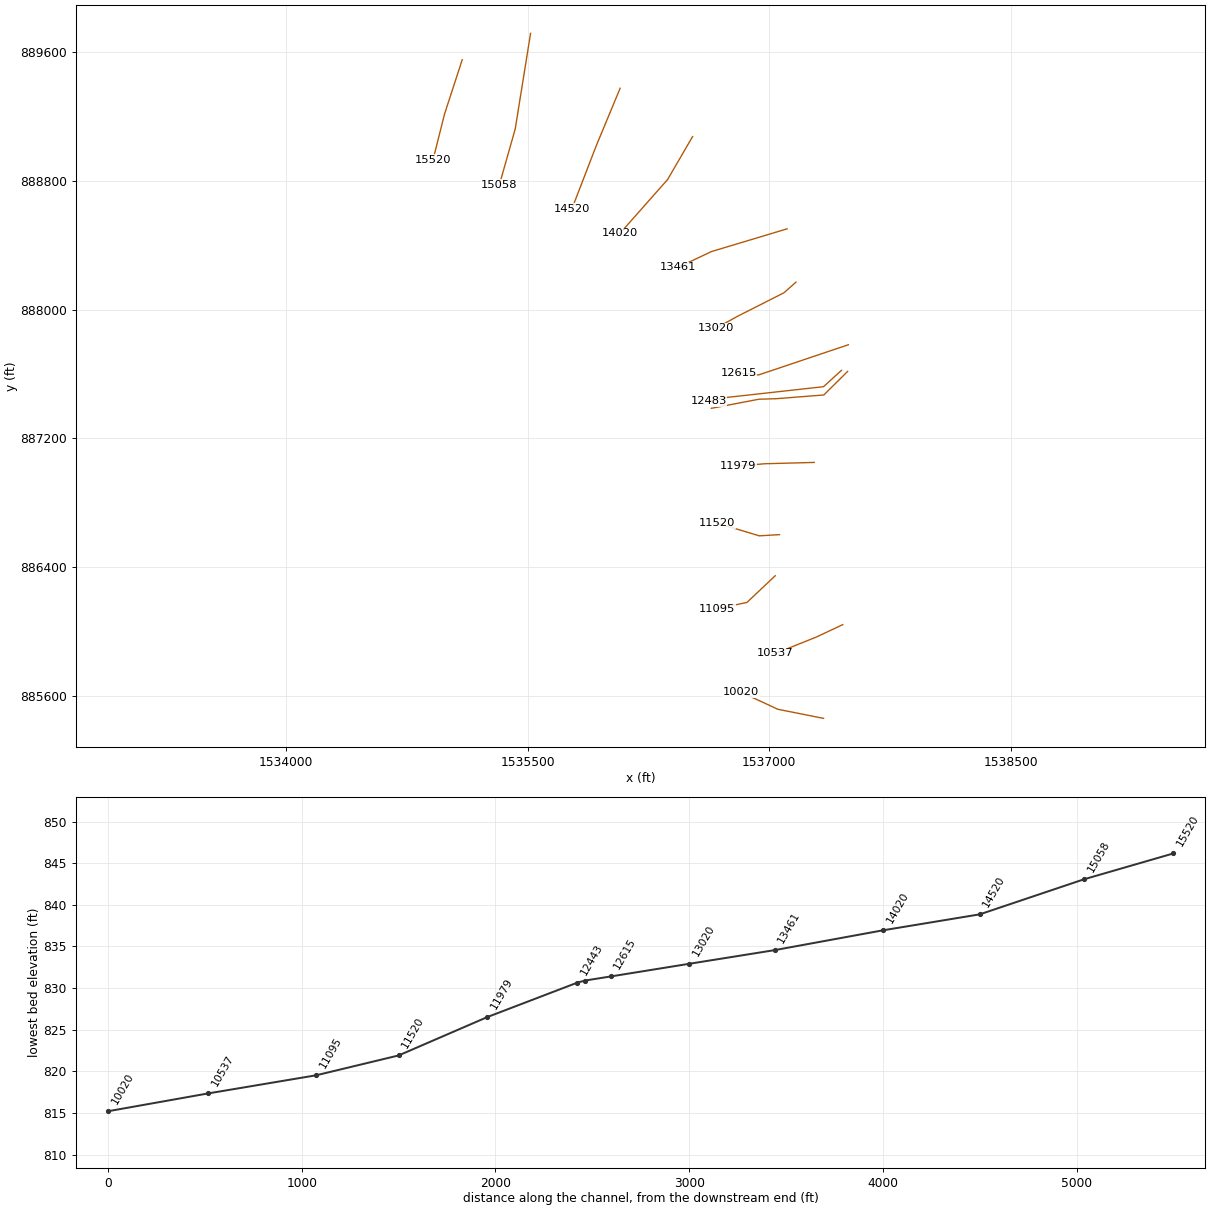
HEC-RAS study Little Forbush Creek.prj: Little Forbush Creek Limited Detail Study

--- Little Forbush Creek.g01 (geometry) --- (continued)

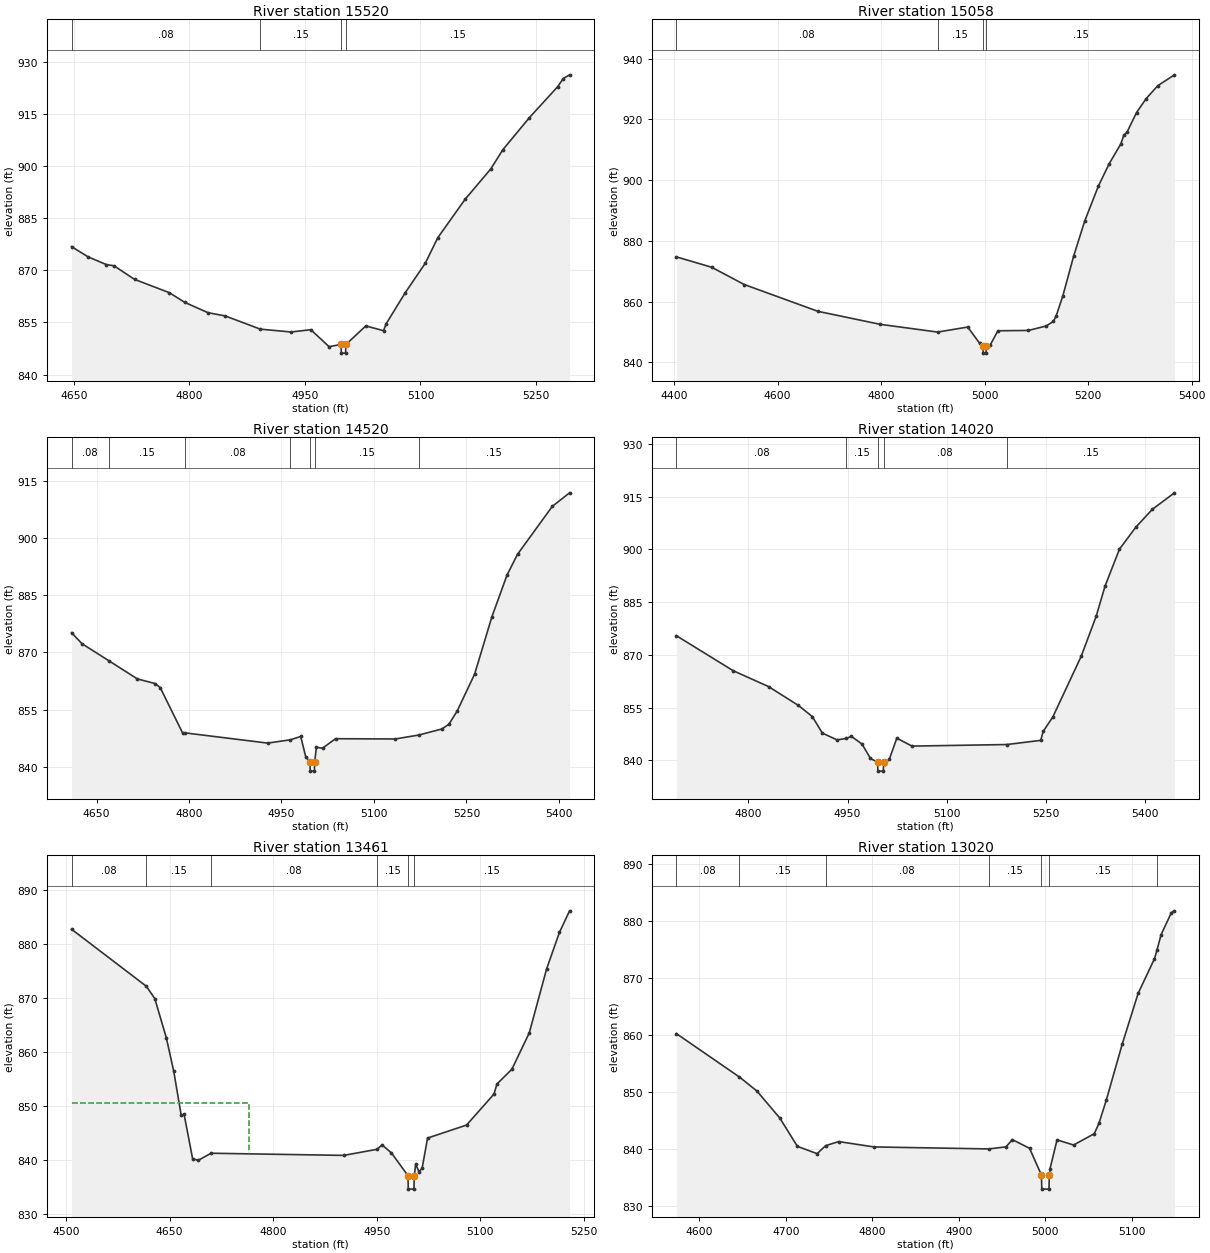
Type RM Length L Ch R = 1,15520,462,462,462
BEGIN DESCRIPTION:
Little Forbush Creek 31.0
END DESCRIPTION:
XS GIS Cut Line= 3
      1535094.23       889551.93      1534984.88       889216.19
      1534913.25       888931.46
#Sta/Elev= 30
  4646.9  876.85  4668.6  873.88  4692.1  871.68  4702.0  871.33  4728.8  867.41
  4773.8  863.59  4794.1  860.77  4824.1  857.82  4846.4  856.89  4892.0  853.08
  4931.9  852.26  4957.6  852.92  4981.3  848.03  4996.8  848.67  4997.3  846.17
  5002.7  846.17  5003.2  848.67  5029.0  854.01  5052.0  852.64  5055.5  854.65
  5080.2  863.57  5106.3  872.10  5122.4  879.40  5157.8  890.45  5191.2  899.22
  5207.1  904.82  5241.5  914.03  5278.0  922.90  5285.5  925.29  5293.6  926.35
#Mann=4,-1,0
  4646.9    0.08       0  4892.0    0.15       0  4996.8   0.048       0
  5003.2    0.15       0
Bank Sta=4996.8,5003.2
XS Rating Curve= 0
Exp/Cntr=0.3,0.1

Type RM Length L Ch R = 1,15058,538,538,538
BEGIN DESCRIPTION:
Little Forbush Creek 30.0
END DESCRIPTION:
XS GIS Cut Line= 3
      1535518.82       889716.14      1535423.69       889123.25
      1535325.01       888775.03
#Sta/Elev= 30
  4404.4  874.75  4472.4  871.34  4535.4  865.65  4677.9  856.82  4798.0  852.55
  4909.1  849.99  4967.3  851.65  4990.4  846.28  4996.8  845.56  4997.3  843.06
  5002.7  843.06  5003.2  845.56  5010.5  845.66  5025.6  850.42  5084.6  850.53
  5118.8  851.99  5132.7  853.48  5138.1  855.24  5151.1  861.92  5172.1  875.08
  5193.4  886.56  5219.6  897.99  5240.6  905.43  5263.1  911.92  5268.8  914.73
  5275.2  915.84  5293.5  922.27  5312.2  926.88  5334.6  931.13  5366.8  934.70
#Mann=4,-1,0
  4404.4    0.08       0  4909.1    0.15       0  4996.8   0.048       0
  5003.2    0.15       0
Bank Sta=4996.8,5003.2
XS Rating Curve= 0
Exp/Cntr=0.3,0.1

Type RM Length L Ch R = 1,14520,500,500,500
BEGIN DESCRIPTION:
Little Forbush Creek 29.0
END DESCRIPTION:
XS GIS Cut Line= 3
      1536074.99       889374.97      1535925.22       889014.34
      1535775.00       888625.01
#Sta/Elev= 30
  4609.5  875.18  4626.4  872.30  4670.0  867.82  4716.3  863.05  4745.0  861.84
  4753.3  860.78  4789.5  848.91  4793.0  848.90  4927.5  846.21  4964.1  847.06
  4981.2  847.94  4989.4  842.58  4996.1  841.35  4996.6  838.85  5003.4  838.85
  5003.9  841.35  5006.6  845.10  5016.6  844.88  5037.7  847.36  5134.4  847.29
  5172.5  848.32  5209.9  849.90  5221.5  851.14  5235.0  854.63  5263.3  864.32
  5291.3  879.35  5315.8  890.29  5332.9  895.77  5389.3  908.35  5417.3  911.90
#Mann=7,-1,0
  4609.5    0.08       0  4670.0    0.15       0  4793.0    0.08       0
  4964.1    0.15       0  4996.1   0.048       0  5003.9    0.15       0
  5172.5    0.15       0
Bank Sta=4996.1,5003.9
XS Rating Curve= 0
Exp/Cntr=0.3,0.1

Type RM Length L Ch R = 1,14020,559,559,559
BEGIN DESCRIPTION:
Little Forbush Creek 28.0
END DESCRIPTION:
XS GIS Cut Line= 3
      1536524.99       889074.98      1536369.52       888808.06
      1536075.00       888475.00
#Sta/Elev= 30
  4691.1  875.43  4777.1  865.47  4830.5  860.97  4875.3  855.65  4896.6  852.46
  4911.8  847.76  4934.0  845.82  4948.2  846.23  4955.7  846.82  4971.8  844.64
  4984.6  840.57  4995.4  839.43  4995.9  836.93  5004.1  836.93  5004.6  839.43
  5006.4  839.09  5013.1  840.26  5024.5  846.30  5047.4  844.05  5190.8  844.49
  5242.2  845.68  5246.1  848.27  5260.7  852.38  5303.6  869.63  5326.1  880.95
  5339.7  889.61  5361.4  900.06  5386.2  906.31  5411.3  911.41  5444.6  916.07
#Mann=5,-1,0
  4691.1    0.08       0  4948.2    0.15       0  4995.4   0.048       0
  5004.6    0.08       0  5190.8    0.15       0
Bank Sta=4995.4,5004.6
XS Rating Curve= 0
Exp/Cntr=0.3,0.1

Type RM Length L Ch R = 1,13461,441,441,441
BEGIN DESCRIPTION:
Little Forbush Creek 27.0
END DESCRIPTION:
XS GIS Cut Line= 3
      1537111.62       888501.96      1536642.02       888360.82
      1536432.84       888262.01
#Sta/Elev= 30
  4507.9  882.70  4616.3  872.13  4628.5  869.85  4645.2  862.60  4656.0  856.37
  4666.8  848.22  4671.0  848.40  4683.3  840.20  4691.4  839.88  4710.0  841.20
  4902.3  840.80  4951.0  841.94  4957.7  842.76  4971.5  841.26  4995.4  837.05
  4995.9  834.55  5004.1  834.55  5004.6  837.05  5006.6  839.20  5011.3  837.79
  5015.9  838.39  5023.8  844.01  5080.3  846.42  5120.0  852.15  5124.4  854.03
  5146.0  856.76  5171.3  863.53  5196.4  875.38  5215.0  882.14  5229.6  886.11
#Mann=6,-1,0
  4507.9    0.08       0  4616.3    0.15       0  4710.0    0.08       0
  4951.0    0.15       0  4995.4   0.048       0  5004.6    0.15       0
#XS Ineff=2,0
    0.00 4765.30  850.51               0
Permanent Ineff=
       F       F
Bank Sta=4995.4,5004.6
XS Rating Curve= 0
Exp/Cntr=0.3,0.1

Type RM Length L Ch R = 1,13020,405,405,405
BEGIN DESCRIPTION:
Little Forbush Creek 26.0
END DESCRIPTION:
XS GIS Cut Line= 4
      1537166.79       888170.89      1537092.59       888105.12
      1536800.69       887957.19      1536670.24       887884.77
#Sta/Elev= 30
  4573.6  860.18  4646.3  852.58  4666.5  850.13  4693.0  845.39  4713.4  840.41
  4736.2  839.13  4746.0  840.53  4761.1  841.25  4801.9  840.31  4934.7  839.96
  4954.5  840.33  4961.9  841.59  4981.7  840.07  4995.4  835.41  4995.9  832.91
  5004.1  832.91  5004.6  835.41  5005.4  836.51  5013.5  841.55  5032.6  840.65
  5056.5  842.63  5061.9  844.44  5070.3  848.46  5088.9  858.38  5107.2  867.24
  5126.1  873.31  5129.0  874.84  5133.8  877.56  5145.7  881.42  5149.2  881.72
#Mann=7,-1,0
  4573.6    0.08       0  4646.3    0.15       0  4746.0    0.08       0
  4934.7    0.15       0  4995.4   0.048       0  5004.6    0.15       0
  5129.0    0.08       0
Bank Sta=4995.4,5004.6
XS Rating Curve= 0
Exp/Cntr=0.3,0.1

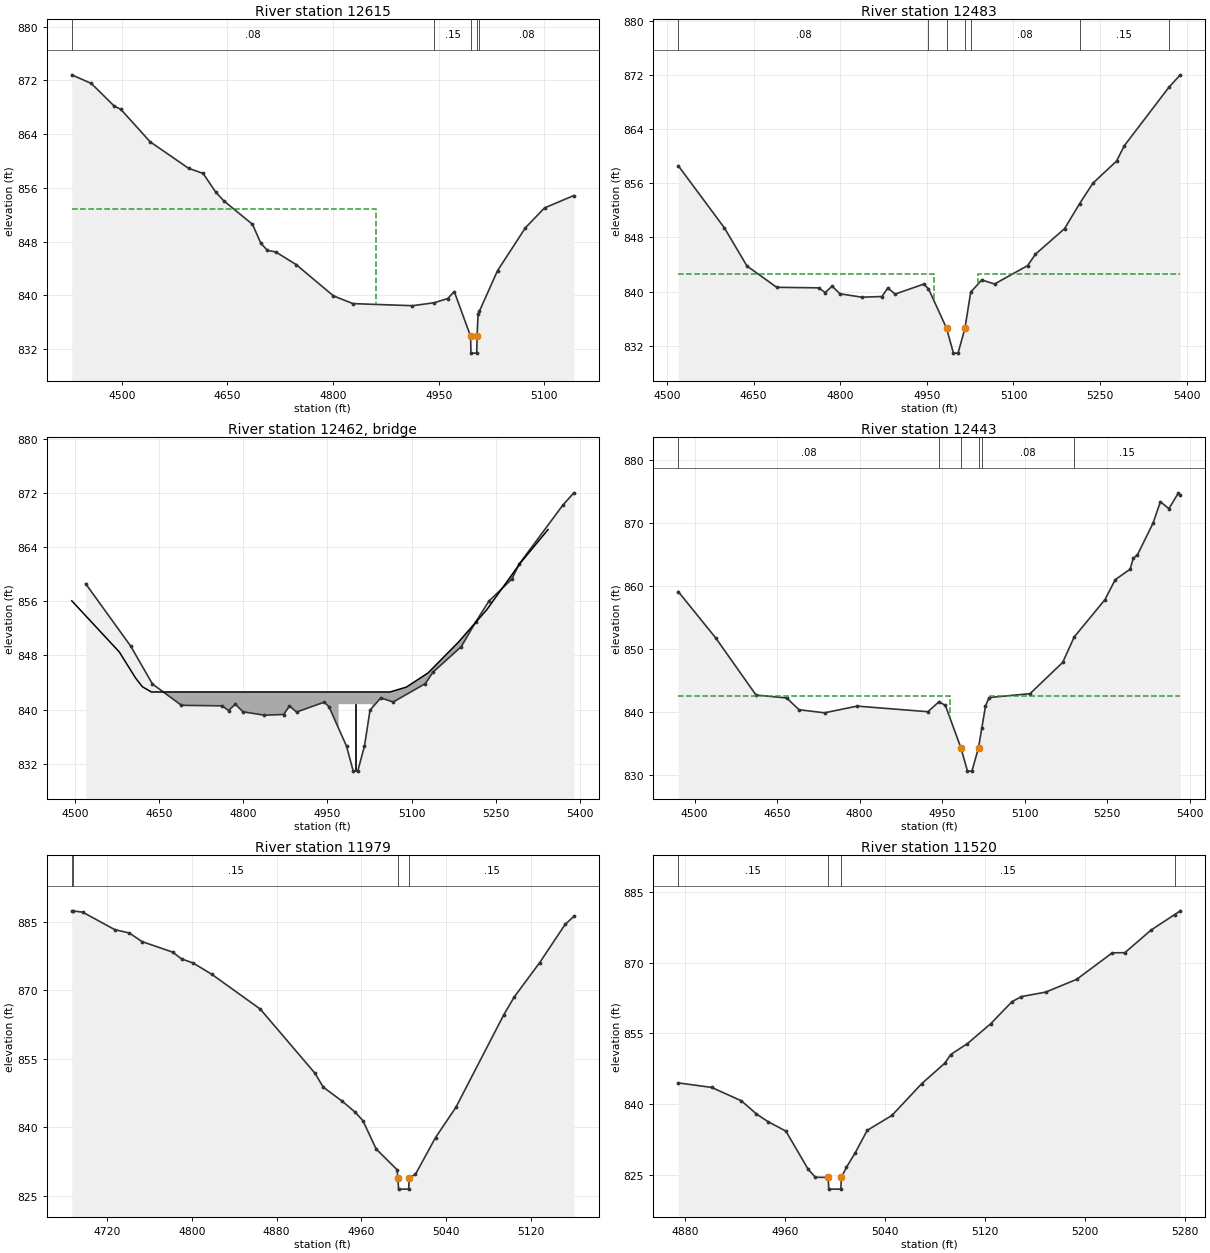
Type RM Length L Ch R = 1,12615,132,132,132
BEGIN DESCRIPTION:
Little Forbush Creek 25.0
END DESCRIPTION:
XS GIS Cut Line= 3
      1537492.52       887782.24      1536935.21       887594.81
      1536810.83       887606.42
#Sta/Elev= 30
  4429.1  872.82  4456.8  871.54  4489.4  868.17  4498.8  867.68  4540.4  862.85
  4594.9  858.91  4615.6  858.14  4633.5  855.36  4645.2  854.04  4685.7  850.57
  4697.7  847.72  4707.0  846.68  4718.6  846.46  4747.6  844.58  4800.7  839.91
  4828.5  838.76  4912.9  838.45  4943.7  838.89  4963.0  839.52  4972.2  840.56
  4995.4  833.89  4995.9  831.39  5004.1  831.39  5004.6  833.89  5006.0  837.24
  5007.9  837.63  5033.6  843.66  5073.3  850.06  5100.4  853.01  5142.0  854.85
#Mann=5,-1,0
  4429.1    0.08       0  4943.7    0.15       0  4995.4   0.048       0
  5004.6    0.15       0  5007.9    0.08       0
#XS Ineff=2,0
    0.00 4861.30  852.90               0
Permanent Ineff=
       F       F
Bank Sta=4995.4,5004.6
XS Rating Curve= 0
Exp/Cntr=0.5,0.3

Type RM Length L Ch R = 1,12483,40,40,40
BEGIN DESCRIPTION:
Rockett Rd (LFC) US
END DESCRIPTION:
XS GIS Cut Line= 5
      1537449.39       887623.03      1537338.24       887521.83
      1536980.00       887482.03      1536741.16       887455.49
      1536625.03       887432.26
#Sta/Elev= 30
  4519.4  858.61  4599.4  849.41  4638.4  843.78  4690.0  840.63  4762.6  840.55
  4773.9  839.85  4786.0  840.80  4799.5  839.67  4837.4  839.17  4872.2  839.27
  4882.4  840.53  4895.0  839.63  4944.5  841.10  4952.8  840.41  4984.0  834.60
  4996.0  830.90  5004.0  830.90  5016.0  834.60  5025.9  839.92  5045.1  841.72
  5067.2  841.12  5124.5  843.84  5138.1  845.53  5188.5  849.31  5214.5  853.00
  5237.6  856.03  5278.4  859.28  5292.0  861.57  5369.4  870.23  5388.9  872.04
#Mann=7,-1,0
  4519.4    0.08       0  4952.8    0.15       0  4984.0   0.048       0
  5016.0    0.15       0  5025.9    0.08       0  5214.5    0.15       0
  5369.4    0.08       0
#XS Ineff=2,0
    0.00 4961.50  842.60 5038.50    0.00  842.60
Permanent Ineff=
       F       F
Bank Sta=4984,5016
XS Rating Curve= 0
Exp/Cntr=0.5,0.3

Type RM Length L Ch R =3,12462,,,
BEGIN DESCRIPTION:
Rockett Rd (LFC) TOR
Structure ID: LDS_LFC_03
Approximate Survey Structure
END DESCRIPTION:
Bridge Culvert--1,0,-1,-1,0
Deck Dist Width WeirC Skew NumUp NumDn MinLoCord MaxHiCord MaxSubmerge Is_Ogee
8.5,25,3,,16,16,,,0.95,0,1,1,,,
  4494.7  4579.4  4608.3  4620.4  4636.4  4970.0  4970.0  5030.0  5030.0  5061.6
  5090.6  5129.3  5182.6  5233.8  5293.0  5342.9
  856.08  848.51  844.67  843.38  842.60  842.60  842.60  842.60  842.60  842.60
  843.32  845.42  849.90  854.76  861.60  866.61
  810.90  810.90  810.90  810.90  810.90  810.90  840.80  840.80  810.90  810.90
  810.90  810.90  810.90  810.90  810.90  810.90
  4494.7  4579.4  4608.3  4620.4  4636.4  4970.0  4970.0  5030.0  5030.0  5061.6
  5090.6  5129.3  5182.6  5233.8  5293.0  5342.9
  856.08  848.51  844.67  843.38  842.60  842.60  842.60  842.60  842.60  842.60
  843.32  845.42  849.90  854.76  861.60  866.61
  810.90  810.90  810.90  810.90  810.90  810.90  840.80  840.80  810.90  810.90
  810.90  810.90  810.90  810.90  810.90  810.90
Pier Skew, UpSta & Num, DnSta & Num=,5000,2,5000,2,0,0,0,0,0
     2.2     2.2
  830.90  840.80
     2.2     2.2
  830.65  840.80
BR Coef=1,1,0,1.25,0,,,0.8,0,2,0,
WSPro=,,,, 1 ,,,, 0 ,,,, 0 ,,,,-1 ,-1 ,-1 , 0 , 0 , 0 , 0 , 0
BC Design=,,0,,0,,,,,,

Type RM Length L Ch R = 1,12443,464,464,464
BEGIN DESCRIPTION:
Rocket Rd (LFC) DS
END DESCRIPTION:
XS GIS Cut Line= 5
      1537487.55       887616.41      1537340.05       887470.32
      1537044.68       887447.20      1536936.87       887443.88
      1536641.64       887387.49
#Sta/Elev= 30
  4470.4  859.12  4538.6  851.76  4611.8  842.71  4667.4  842.25  4690.0  840.38
  4736.2  839.90  4795.5  840.96  4924.0  840.07  4944.2  841.65  4955.8  841.07
  4984.0  834.35  4996.0  830.65  5004.0  830.65  5016.0  834.35  5021.9  837.42
  5028.7  840.95  5035.1  842.32  5109.6  842.93  5168.9  847.88  5189.9  851.92
  5245.9  857.86  5264.4  861.00  5291.6  862.68  5297.2  864.41  5304.8  864.94
  5333.1  869.97  5346.5  873.37  5362.0  872.27  5379.3  874.78  5382.7  874.42
#Mann=6,-1,0
  4470.4    0.08       0  4944.2    0.15       0  4984.0   0.048       0
  5016.0    0.15       0  5021.9    0.08       0  5189.9    0.15       0
#XS Ineff=2,0
    0.00 4963.50  842.60 5036.50    0.00  842.60
Permanent Ineff=
       F       F
Bank Sta=4984,5016
XS Rating Curve= 0
Exp/Cntr=0.5,0.3

Type RM Length L Ch R = 1,11979,459,459,459
BEGIN DESCRIPTION:
Little Forbush Creek 24.0
END DESCRIPTION:
XS GIS Cut Line= 3
      1537280.25       887051.43      1536973.08       887043.19
      1536806.49       887028.67
#Sta/Elev= 30
  4686.4  887.39  4687.6  887.36  4696.7  887.10  4727.0  883.28  4740.8  882.54
  4752.7  880.67  4781.6  878.37  4790.2  876.87  4801.0  875.99  4818.6  873.53
  4864.5  865.91  4916.2  851.88  4924.1  848.81  4942.0  845.75  4954.4  843.32
  4961.6  841.48  4974.1  835.29  4993.7  830.79  4994.7  829.02  4995.2  826.52
  5004.8  826.52  5005.3  829.02  5011.1  829.72  5030.2  837.81  5049.4  844.40
  5094.6  864.62  5104.5  868.53  5128.6  876.06  5152.7  884.43  5160.9  886.18
#Mann=4,-1,0
  4686.4    0.08       0  4687.6    0.15       0  4994.7   0.048       0
  5005.3    0.15       0
Bank Sta=4994.7,5005.3
XS Rating Curve= 0
Exp/Cntr=0.3,0.1

Type RM Length L Ch R = 1,11520,425,425,425
BEGIN DESCRIPTION:
Little Forbush Creek 23.0
END DESCRIPTION:
XS GIS Cut Line= 3
      1537064.60       886603.00      1536939.62       886595.48
      1536675.01       886675.00
#Sta/Elev= 30
  4874.8  844.46  4901.5  843.50  4925.3  840.65  4937.3  837.88  4946.4  836.26
  4960.9  834.22  4978.8  826.07  4984.5  824.41  4994.7  824.40  4995.2  821.90
  5004.8  821.90  5005.3  824.40  5009.2  826.50  5016.3  829.60  5025.9  834.38
  5045.7  837.56  5069.6  844.32  5088.1  848.67  5092.6  850.47  5106.0  852.79
  5124.6  857.00  5141.7  861.71  5149.3  862.79  5168.7  863.74  5193.4  866.45
  5221.9  872.08  5232.0  872.12  5252.9  876.91  5271.8  880.21  5276.3  881.00
#Mann=4,-1,0
  4874.8    0.15       0  4994.7   0.048       0  5005.3    0.15       0
  5271.8    0.08       0
Bank Sta=4994.7,5005.3
XS Rating Curve= 0
Exp/Cntr=0.3,0.1

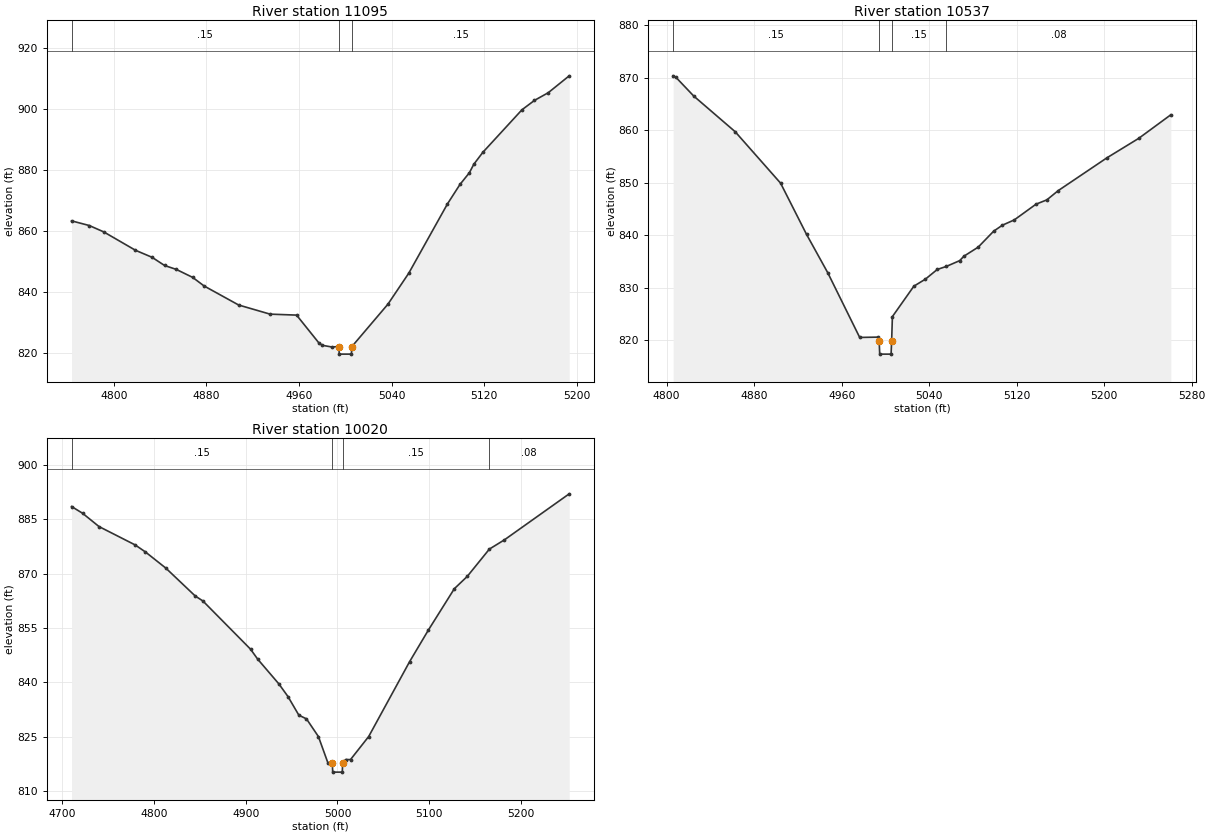
Type RM Length L Ch R = 1,11095,558,558,558
BEGIN DESCRIPTION:
Little Forbush Creek 22.0
END DESCRIPTION:
XS GIS Cut Line= 3
      1537038.01       886347.55      1536862.24       886181.73
      1536678.10       886143.57
#Sta/Elev= 30
  4763.6  863.24  4778.9  861.71  4791.4  859.62  4818.8  853.59  4833.1  851.29
  4843.9  848.60  4854.0  847.32  4868.2  844.69  4878.0  841.89  4907.9  835.63
  4935.0  832.64  4957.9  832.32  4977.1  823.22  4980.2  822.41  4988.5  821.85
  4994.3  822.02  4994.8  819.52  5005.2  819.52  5005.7  822.02  5036.8  835.92
  5054.8  846.09  5088.2  868.82  5099.0  875.20  5107.1  879.02  5110.9  881.80
  5118.7  885.71  5152.5  899.68  5163.3  902.76  5175.2  905.28  5193.3  910.82
#Mann=3,-1,0
  4763.6    0.15       0  4994.3   0.048       0  5005.7    0.15       0
Bank Sta=4994.3,5005.7
XS Rating Curve= 0
Exp/Cntr=0.3,0.1

Type RM Length L Ch R = 1,10537,517,517,517
BEGIN DESCRIPTION:
Little Forbush Creek 21.0
END DESCRIPTION:
XS GIS Cut Line= 3
      1537457.69       886044.08      1537295.12       885967.77
      1537039.73       885864.95
#Sta/Elev= 30
  4806.0  870.36  4808.5  870.08  4824.8  866.51  4862.7  859.71  4904.2  849.91
  4927.9  840.16  4947.3  832.85  4976.5  820.52  4993.2  820.58  4994.3  819.84
  4994.8  817.34  5005.2  817.34  5005.7  819.84  5006.4  824.49  5026.0  830.28
  5036.6  831.63  5047.4  833.47  5055.6  834.04  5067.9  835.15  5071.8  836.00
  5084.8  837.72  5099.0  840.77  5107.0  841.91  5117.8  842.91  5137.7  845.91
  5147.6  846.73  5157.9  848.48  5202.5  854.74  5231.5  858.44  5260.9  862.94
#Mann=4,-1,0
  4806.0    0.15       0  4994.3   0.048       0  5005.7    0.15       0
  5055.6    0.08       0
Bank Sta=4994.3,5005.7
XS Rating Curve= 0
Exp/Cntr=0.3,0.1

Type RM Length L Ch R = 1,10020,500,500,500
BEGIN DESCRIPTION:
Little Forbush Creek 20.0
END DESCRIPTION:
XS GIS Cut Line= 3
      1537338.21       885461.92      1537053.99       885518.54
      1536825.03       885624.99
#Sta/Elev= 30
  4710.2  888.50  4722.2  886.64  4740.1  882.97  4779.5  877.90  4790.7  875.96
  4812.9  871.51  4845.0  863.80  4853.3  862.44  4905.2  849.14  4913.1  846.36
  4936.1  839.55  4946.0  836.07  4957.9  830.91  4966.2  829.90  4979.2  825.02
  4989.6  817.72  4994.3  817.70  4994.8  815.20  5005.2  815.20  5005.7  817.70
  5008.8  818.66  5014.2  818.67  5034.0  825.03  5078.5  845.65  5099.0  854.39
  5127.3  865.81  5141.4  869.21  5165.5  876.75  5181.9  879.30  5252.5  892.00
#Mann=4,-1,0
  4710.2    0.15       0  4994.3   0.048       0  5005.7    0.15       0
  5165.5    0.08       0
Bank Sta=4994.3,5005.7
XS Rating Curve= 0
Exp/Cntr=0.3,0.1