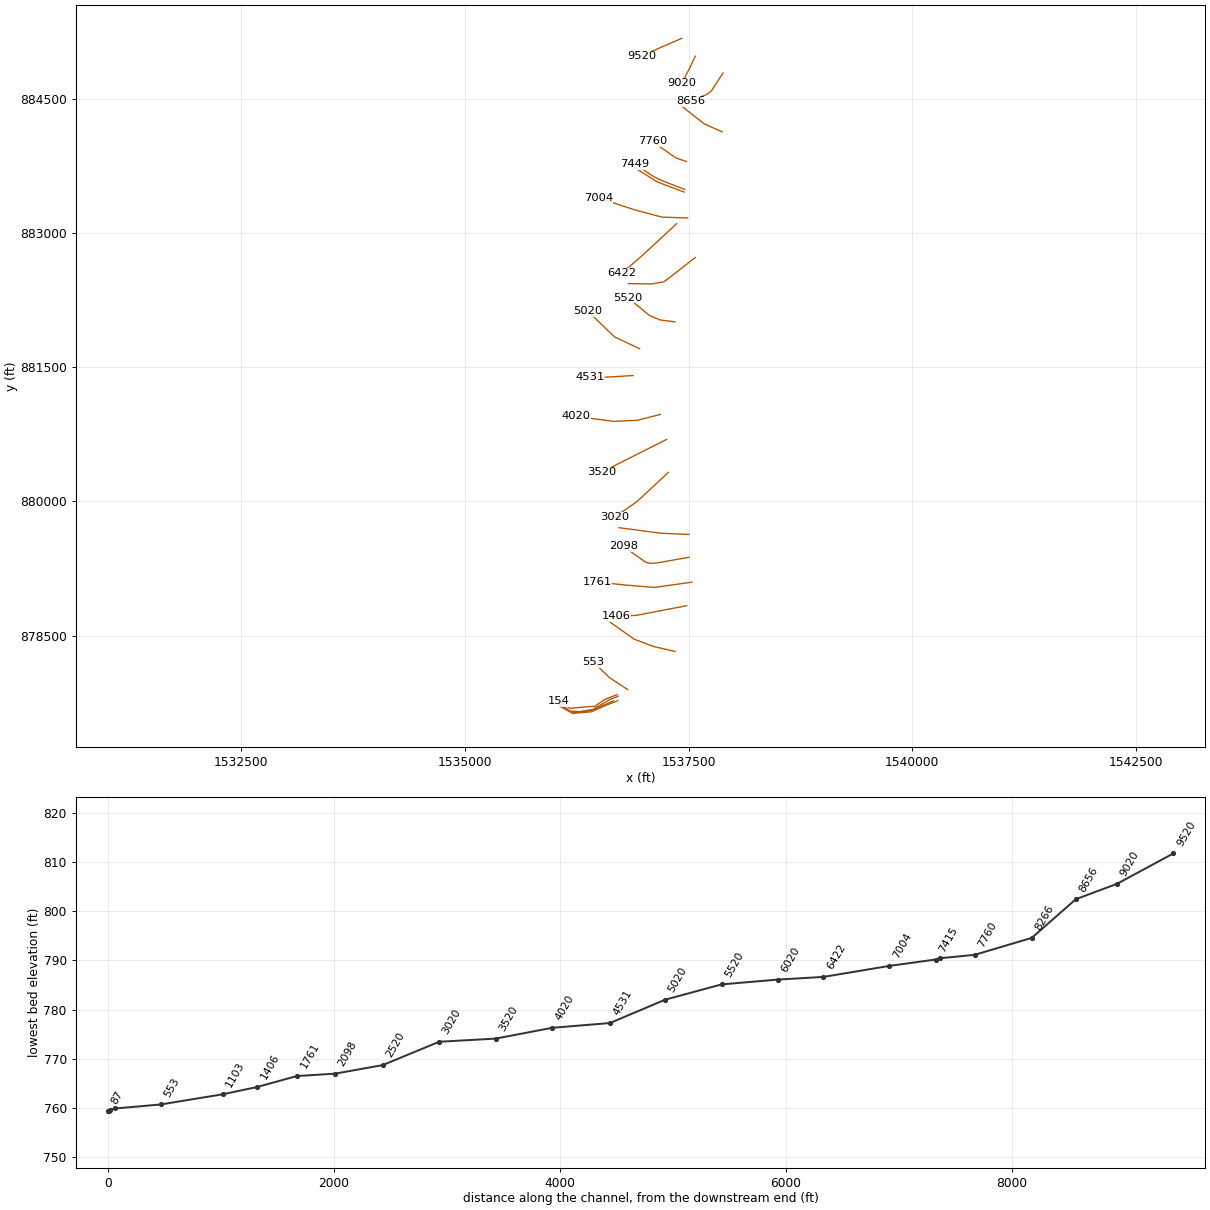
HEC-RAS study Little Forbush Creek.prj: Little Forbush Creek Limited Detail Study

--- Little Forbush Creek.g01 (geometry) --- (continued)

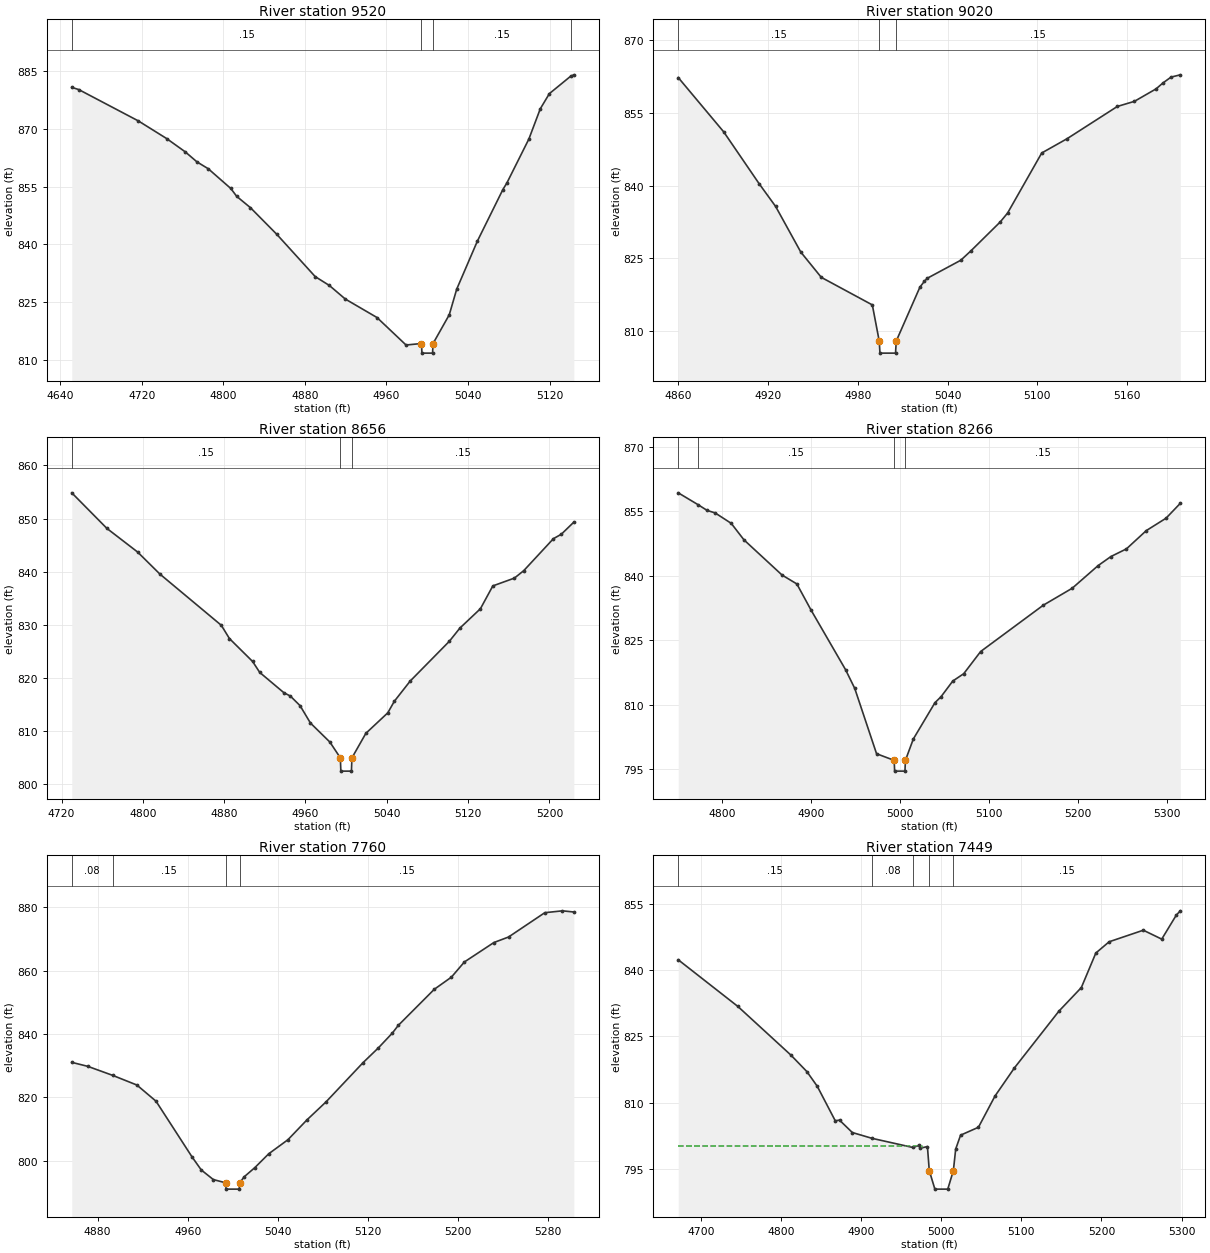
Type RM Length L Ch R = 1,9520,500,500,500
BEGIN DESCRIPTION:
Little Forbush Creek 19.0
END DESCRIPTION:
XS GIS Cut Line= 3
      1537424.99       885175.00      1537105.10       885036.22
      1536974.98       884974.99
#Sta/Elev= 30
  4651.3  880.82  4658.2  880.24  4716.5  872.11  4744.4  867.50  4762.6  864.05
  4774.1  861.44  4785.2  859.65  4807.3  854.52  4813.1  852.47  4826.6  849.52
  4852.3  842.63  4890.1  831.60  4904.0  829.29  4919.6  825.77  4950.7  820.96
  4979.2  813.81  4994.3  814.20  4994.8  811.70  5005.2  811.70  5005.7  814.20
  5021.6  821.68  5028.9  828.34  5049.2  840.85  5074.2  854.25  5078.1  855.95
  5099.7  867.39  5110.9  875.26  5119.8  879.19  5140.6  883.70  5143.8  884.08
#Mann=4,-1,0
  4651.3    0.15       0  4994.3   0.048       0  5005.7    0.15       0
  5140.6    0.08       0
Bank Sta=4994.3,5005.7
XS Rating Curve= 0
Exp/Cntr=0.3,0.1

Type RM Length L Ch R = 1,9020,364,364,364
BEGIN DESCRIPTION:
Little Forbush Creek 18.0
END DESCRIPTION:
XS GIS Cut Line= 3
      1537574.99       884974.98      1537516.31       884847.87
      1537425.00       884675.01
#Sta/Elev= 26
  4860.0  862.22  4890.4  851.04  4914.1  840.36  4925.1  835.69  4941.9  826.31
  4955.6  821.11  4989.7  815.44  4994.3  808.02  4994.8  805.52  5005.2  805.52
  5005.7  808.02  5021.5  819.10  5024.4  820.26  5026.4  820.92  5048.8  824.63
  5055.6  826.57  5075.2  832.52  5080.1  834.35  5102.9  846.70  5119.8  849.63
  5153.4  856.27  5164.8  857.32  5179.3  859.89  5183.9  861.11  5189.3  862.31
  5195.5  862.78
#Mann=3,-1,0
  4860.0    0.15       0  4994.3   0.048       0  5005.7    0.15       0
Bank Sta=4994.3,5005.7
XS Rating Curve= 0
Exp/Cntr=0.3,0.1

Type RM Length L Ch R = 1,8656,390,390,390
BEGIN DESCRIPTION:
Little Forbush Creek 17.0
END DESCRIPTION:
XS GIS Cut Line= 4
      1537885.54       884786.85      1537752.88       884584.54
      1537713.07       884553.03      1537529.01       884471.77
#Sta/Elev= 30
  4730.1  854.84  4764.7  848.13  4794.9  843.68  4816.8  839.53  4877.2  829.88
  4885.2  827.38  4908.0  823.06  4915.0  821.00  4938.8  817.17  4945.1  816.55
  4954.7  814.73  4964.9  811.46  4984.0  807.88  4994.3  804.90  4994.8  802.40
  5005.2  802.40  5005.7  804.90  5019.4  809.52  5041.0  813.39  5047.4  815.56
  5063.0  819.37  5101.5  826.86  5111.9  829.35  5132.1  833.00  5144.3  837.30
  5165.5  838.77  5174.7  840.17  5203.9  846.20  5211.7  847.04  5224.0  849.32
#Mann=3,-1,0
  4730.1    0.15       0  4994.3   0.048       0  5005.7    0.15       0
Bank Sta=4994.3,5005.7
XS Rating Curve= 0
Exp/Cntr=0.3,0.1

Type RM Length L Ch R = 1,8266,506,506,506
BEGIN DESCRIPTION:
Little Forbush Creek 16.0
END DESCRIPTION:
XS GIS Cut Line= 3
      1537875.57       884130.12      1537674.93       884219.66
      1537404.40       884432.29
#Sta/Elev= 30
  4751.2  859.30  4773.3  856.56  4783.7  855.20  4792.6  854.63  4810.7  852.20
  4825.0  848.36  4867.8  840.17  4884.4  838.10  4900.4  832.00  4939.1  818.15
  4949.4  813.80  4973.9  798.60  4993.7  797.05  4994.2  794.55  5005.8  794.55
  5006.3  797.05  5015.2  802.03  5039.5  810.48  5046.3  811.86  5059.5  815.51
  5071.8  817.22  5090.8  822.38  5161.1  833.15  5193.6  837.10  5222.7  842.37
  5237.1  844.48  5254.5  846.26  5276.8  850.51  5299.0  853.40  5315.0  856.86
#Mann=4,-1,0
  4751.2    0.08       0  4773.3    0.15       0  4993.7   0.048       0
  5006.3    0.15       0
Bank Sta=4993.7,5006.3
XS Rating Curve= 0
Exp/Cntr=0.3,0.1

Type RM Length L Ch R = 1,7760,311,311,311
BEGIN DESCRIPTION:
Little Forbush Creek 15.0
END DESCRIPTION:
XS GIS Cut Line= 3
      1537477.57       883798.39      1537358.65       883839.10
      1537096.13       884022.27
#Sta/Elev= 30
  4857.1  831.08  4871.3  829.82  4893.3  826.99  4914.9  823.93  4931.9  818.83
  4963.9  801.25  4972.1  797.14  4982.8  794.11  4993.7  793.10  4994.2  791.10
  5005.8  791.10  5006.3  793.10  5010.1  794.96  5019.7  797.90  5032.0  802.25
  5049.0  806.67  5066.0  812.96  5082.8  818.59  5115.8  831.01  5129.4  835.66
  5141.8  840.33  5147.0  842.73  5179.0  854.12  5194.2  857.95  5205.7  862.73
  5231.9  868.86  5244.9  870.60  5277.1  878.27  5292.8  878.86  5302.9  878.49
#Mann=4,-1,0
  4857.1    0.08       0  4893.3    0.15       0  4993.7   0.048       0
  5006.3    0.15       0
Bank Sta=4993.7,5006.3
XS Rating Curve= 0
Exp/Cntr=0.5,0.3

Type RM Length L Ch R = 1,7449,34,34,34
BEGIN DESCRIPTION:
Addison Rd (LFC) US
END DESCRIPTION:
XS GIS Cut Line= 4
      1537458.94       883485.28      1537192.30       883590.15
      1537112.32       883629.26      1536902.55       883767.92
#Sta/Elev= 30
  4671.5  842.34  4746.0  831.77  4812.3  820.74  4832.1  817.03  4845.1  813.70
  4867.6  805.88  4872.9  806.03  4888.9  803.22  4913.4  801.91  4964.6  799.83
  4971.7  800.30  4973.7  799.67  4982.7  800.04  4985.0  794.60  4992.0  790.40
  5008.1  790.40  5015.1  794.60  5018.0  799.48  5024.1  802.62  5046.4  804.41
  5067.1  811.49  5091.4  817.87  5146.9  830.71  5174.9  836.05  5193.0  843.87
  5209.6  846.42  5252.3  849.04  5275.3  847.02  5293.5  852.46  5298.5  853.43
#Mann=5,-1,0
  4671.5    0.15       0  4913.4    0.08       0  4964.6    0.15       0
  4985.0   0.048       0  5015.1    0.15       0
#XS Ineff=2,0
    0.00 4976.00  800.24 5024.00    0.00  800.24
Permanent Ineff=
       F       F
Bank Sta=4985,5015.1
XS Rating Curve= 0
Exp/Cntr=0.5,0.3

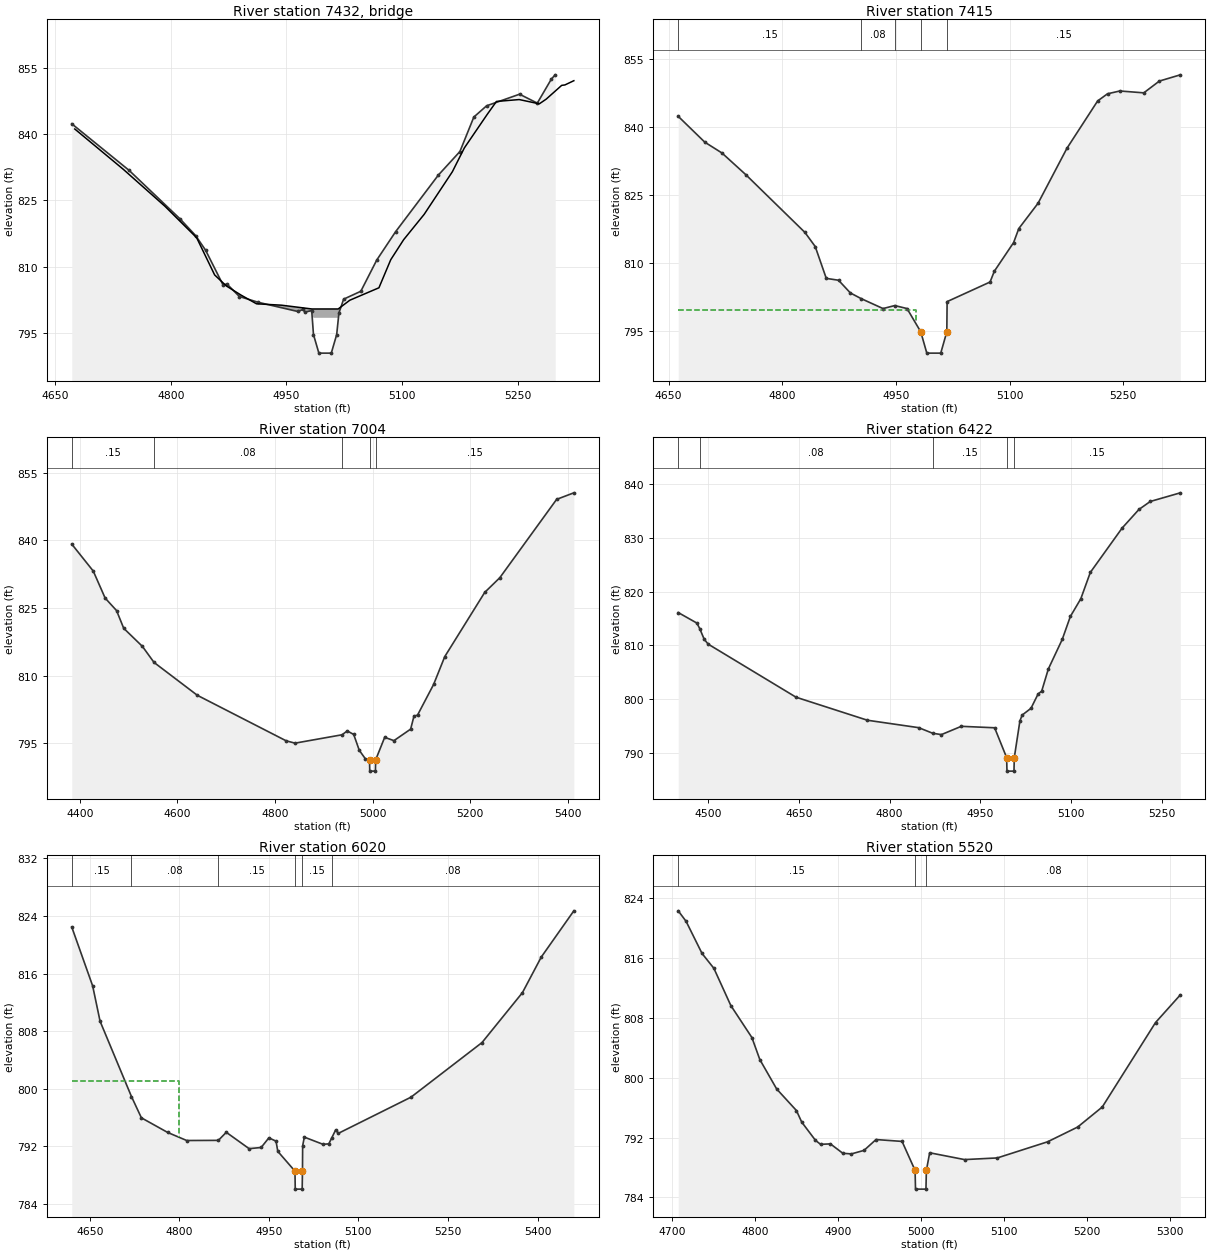
Type RM Length L Ch R =3,7432,,,
BEGIN DESCRIPTION:
Addison Rd (LFC) TOR
Structure ID: LDS_LFC_02
Approximate Survey Structure
END DESCRIPTION:
Bridge Culvert--1,0,-1,-1,0
Deck Dist Width WeirC Skew NumUp NumDn MinLoCord MaxHiCord MaxSubmerge Is_Ogee
7,20,3,,29,29,,,0.95,0,1,1,,,
  4675.4  4703.8  4738.4  4792.3  4833.5  4856.8  4872.1  4890.9  4911.1  4943.5
  4983.0  4983.0  5017.0  5017.0  5032.1  5069.9  5085.2  5101.9  5128.6  5165.1
  5180.7  5210.1  5222.3  5251.8  5277.9  5286.8  5306.9  5311.1  5322.7
  841.16  837.04  832.02  823.67  816.53  808.11  805.60  803.56  801.57  801.26
  800.40  800.40  800.40  800.40  802.38  805.20  811.55  816.08  821.84  831.47
  836.88  844.41  847.40  847.83  846.86  847.92  851.04  851.14  852.10
  770.40  770.40  770.40  770.40  770.40  770.40  770.40  770.40  770.40  770.40
  770.40  798.40  798.40  770.40  770.40  770.40  770.40  770.40  770.40  770.40
  770.40  770.40  770.40  770.40  770.40  770.40  770.40  770.40  770.40
  4675.4  4703.8  4738.4  4792.3  4833.5  4856.8  4872.1  4890.9  4911.1  4943.5
  4983.0  4983.0  5017.0  5017.0  5032.1  5069.9  5085.2  5101.9  5128.6  5165.1
  5180.7  5210.1  5222.3  5251.8  5277.9  5286.8  5306.9  5311.1  5322.7
  841.16  837.04  832.02  823.67  816.53  808.11  805.60  803.56  801.57  801.26
  800.40  800.40  800.40  800.40  802.38  805.20  811.55  816.08  821.84  831.47
  836.88  844.41  847.40  847.83  846.86  847.92  851.04  851.14  852.10
  770.40  770.40  770.40  770.40  770.40  770.40  770.40  770.40  770.40  770.40
  770.40  798.40  798.40  770.40  770.40  770.40  770.40  770.40  770.40  770.40
  770.40  770.40  770.40  770.40  770.40  770.40  770.40  770.40  770.40
BR Coef=1,1,0,1.25,0,,,0.8,0,2,0,
WSPro=,,,, 1 ,,,, 0 ,,,, 0 ,,,,-1 ,-1 ,-1 , 0 , 0 , 0 , 0 , 0
BC Design=,,0,,0,,,,,,

Type RM Length L Ch R = 1,7415,411,411,411
BEGIN DESCRIPTION:
Addison Rd (LFC) DS
END DESCRIPTION:
XS GIS Cut Line= 4
      1537450.36       883457.25      1537228.91       883540.23
      1537145.89       883574.31      1536860.59       883752.68
#Sta/Elev= 30
  4662.7  842.32  4697.7  836.64  4720.4  834.25  4751.7  829.50  4829.9  816.75
  4843.5  813.64  4858.1  806.62  4874.3  806.21  4889.9  803.41  4903.9  802.18
  4933.0  799.97  4948.5  800.63  4964.7  799.97  4982.8  794.85  4990.8  790.15
  5009.2  790.15  5017.2  794.85  5017.6  801.50  5074.3  805.82  5079.9  808.19
  5105.4  814.52  5112.2  817.59  5137.7  823.19  5175.7  835.27  5216.3  845.72
  5229.3  847.29  5245.6  847.91  5277.2  847.50  5297.7  850.09  5325.4  851.47
#Mann=5,-1,0
  4662.7    0.15       0  4903.9    0.08       0  4948.5    0.15       0
  4982.8   0.048       0  5017.2    0.15       0
#XS Ineff=2,0
    0.00 4976.00  799.70 5024.00    0.00  801.33
Permanent Ineff=
       F       F
Bank Sta=4982.8,5017.2
XS Rating Curve= 0
Exp/Cntr=0.5,0.3

Type RM Length L Ch R = 1,7004,582,582,582
BEGIN DESCRIPTION:
Little Forbush Creek 14.0
END DESCRIPTION:
XS GIS Cut Line= 4
      1537489.46       883167.21      1537200.94       883177.52
      1536888.15       883261.73      1536492.25       883391.62
#Sta/Elev= 30
  4383.3  839.17  4427.4  833.19  4451.7  827.21  4475.1  824.44  4489.8  820.51
  4528.2  816.49  4551.9  812.95  4640.7  805.66  4822.8  795.57  4841.0  795.05
  4937.5  796.91  4948.0  797.76  4961.3  796.98  4972.7  793.47  4984.9  791.63
  4993.7  791.35  4994.2  788.85  5005.8  788.85  5006.3  791.35  5024.8  796.34
  5043.8  795.61  5078.0  798.16  5084.8  801.02  5092.2  801.28  5125.1  808.06
  5148.0  814.24  5229.9  828.47  5260.8  831.72  5377.3  849.09  5412.6  850.54
#Mann=5,-1,0
  4383.3    0.15       0  4551.9    0.08       0  4937.5    0.15       0
  4993.7   0.048       0  5006.3    0.15       0
Bank Sta=4993.7,5006.3
XS Rating Curve= 0
Exp/Cntr=0.3,0.1

Type RM Length L Ch R = 1,6422,402,402,402
BEGIN DESCRIPTION:
Little Forbush Creek 13.0
END DESCRIPTION:
XS GIS Cut Line= 3
      1537367.07       883103.16      1536986.39       882750.59
      1536750.16       882547.95
#Sta/Elev= 30
  4450.7  816.10  4481.6  814.14  4486.3  813.10  4493.6  811.14  4500.2  810.23
  4645.5  800.36  4763.5  796.08  4848.3  794.70  4871.4  793.66  4885.8  793.41
  4918.7  794.95  4973.8  794.68  4993.7  789.12  4994.2  786.62  5005.8  786.62
  5006.3  789.12  5015.6  795.95  5019.3  797.04  5033.9  798.30  5045.7  800.97
  5051.6  801.49  5062.6  805.61  5085.6  811.11  5099.0  815.37  5116.3  818.67
  5132.0  823.56  5184.6  831.81  5212.4  835.27  5231.1  836.75  5280.8  838.36
#Mann=5,-1,0
  4450.7    0.15       0  4486.3    0.08       0  4871.4    0.15       0
  4993.7   0.048       0  5006.3    0.15       0
Bank Sta=4993.7,5006.3
XS Rating Curve= 0
Exp/Cntr=0.3,0.1

Type RM Length L Ch R = 1,6020,500,500,500
BEGIN DESCRIPTION:
Little Forbush Creek 12.0
END DESCRIPTION:
XS GIS Cut Line= 5
      1537575.03       882725.02      1537275.30       882491.27
      1537223.30       882453.87      1537089.32       882430.33
      1536828.63       882433.95
#Sta/Elev= 30
  4619.9  822.47  4654.9  814.29  4667.3  809.39  4719.9  798.93  4736.5  795.98
  4780.5  793.95  4812.4  792.83  4865.4  792.85  4878.7  793.97  4916.9  791.70
  4937.1  791.86  4950.0  793.20  4962.0  792.74  4965.0  791.32  4993.7  788.58
  4994.2  786.08  5005.8  786.08  5006.3  788.58  5006.6  792.10  5009.4  793.30
  5040.8  792.30  5050.4  792.37  5055.0  793.14  5061.8  794.29  5066.5  793.83
  5188.1  798.85  5307.0  806.43  5374.7  813.36  5406.3  818.31  5460.8  824.72
#Mann=6,-1,0
  4619.9    0.15       0  4719.9    0.08       0  4865.4    0.15       0
  4993.7   0.048       0  5006.3    0.15       0  5055.0    0.08       0
#XS Ineff=2,0
    0.00 4799.70  801.09               0
Permanent Ineff=
       F       F
Bank Sta=4993.7,5006.3
XS Rating Curve= 0
Exp/Cntr=0.3,0.1

Type RM Length L Ch R = 1,5520,500,500,500
BEGIN DESCRIPTION:
Little Forbush Creek 11.0
END DESCRIPTION:
XS GIS Cut Line= 4
      1537348.21       882006.68      1537181.66       882028.40
      1537066.74       882076.12      1536825.03       882274.98
#Sta/Elev= 30
  4707.6  822.31  4717.1  820.90  4736.3  816.61  4750.6  814.62  4771.0  809.65
  4796.4  805.37  4806.0  802.42  4826.3  798.49  4850.1  795.61  4856.5  794.06
  4873.1  791.62  4879.2  791.09  4891.1  791.15  4906.1  789.89  4916.4  789.81
  4931.6  790.28  4946.1  791.73  4977.5  791.48  4993.2  787.60  4993.7  785.10
  5006.3  785.10  5006.8  787.60  5010.8  789.96  5052.8  789.05  5092.3  789.27
  5153.0  791.43  5189.2  793.40  5218.9  796.08  5283.1  807.37  5313.0  811.07
#Mann=3,-1,0
  4707.6    0.15       0  4993.2   0.048       0  5006.8    0.08       0
Bank Sta=4993.2,5006.8
XS Rating Curve= 0
Exp/Cntr=0.3,0.1

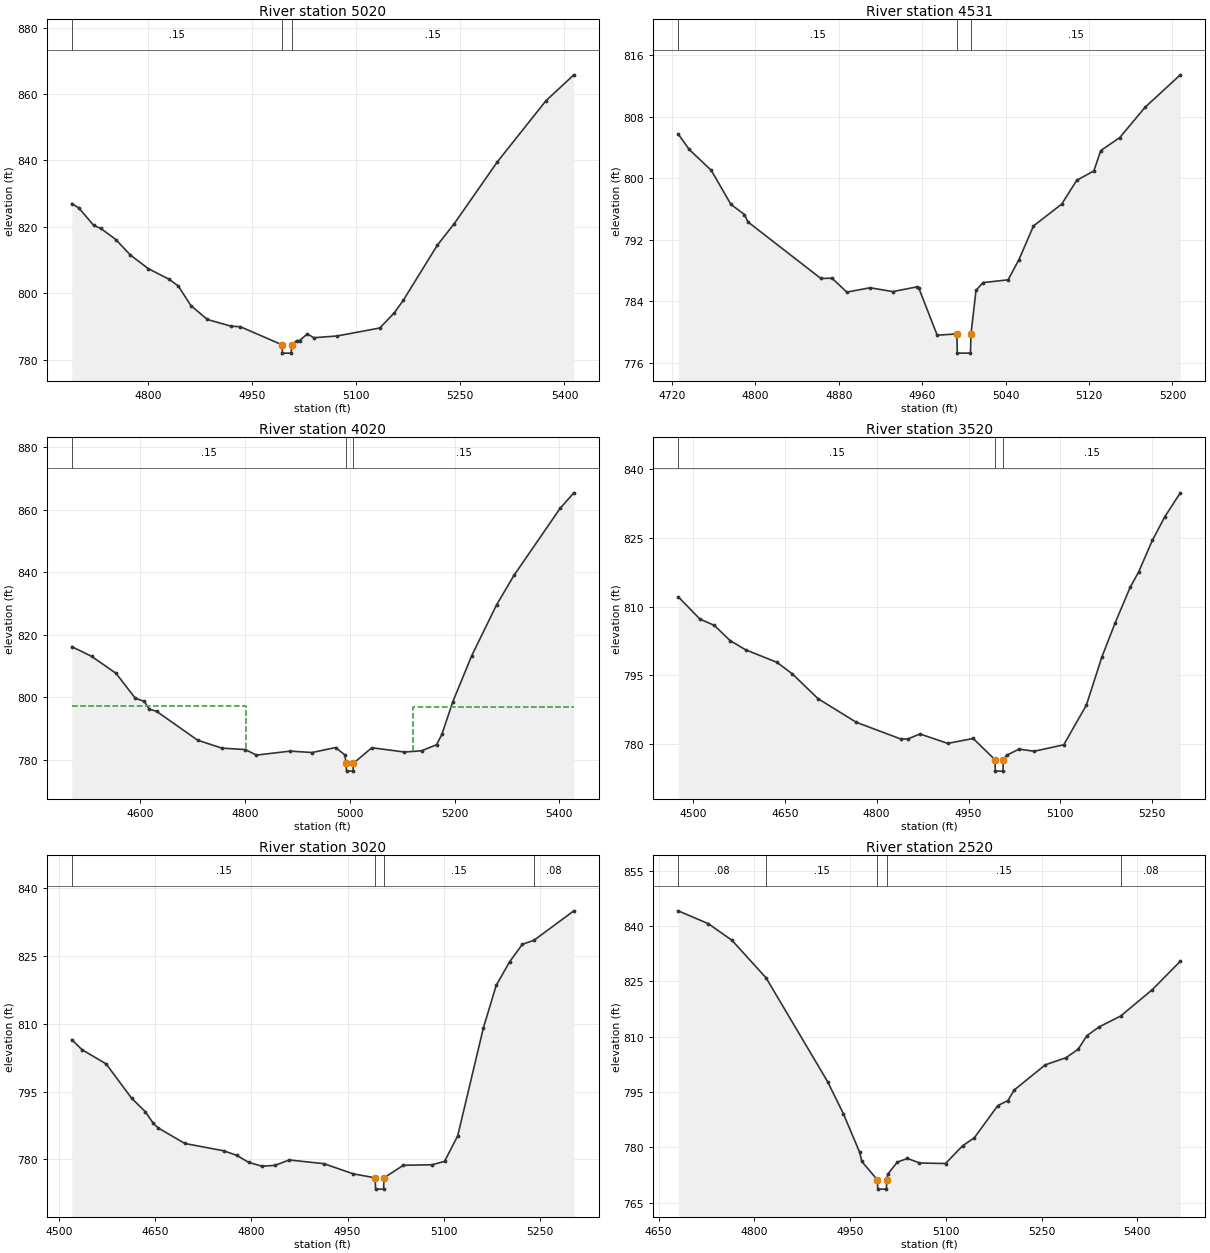
Type RM Length L Ch R = 1,5020,489,489,489
BEGIN DESCRIPTION:
Little Forbush Creek 10.0
END DESCRIPTION:
XS GIS Cut Line= 3
      1536953.56       881706.12      1536673.56       881838.94
      1536374.99       882125.01
#Sta/Elev= 30
  4690.1  827.01  4700.4  825.67  4721.7  820.44  4732.0  819.51  4753.5  816.19
  4774.7  811.50  4800.4  807.42  4830.4  804.22  4843.5  802.21  4861.7  796.32
  4885.4  792.12  4919.6  790.10  4933.1  789.93  4993.2  784.49  4993.7  781.99
  5006.3  781.99  5006.8  784.49  5014.1  785.73  5018.4  785.77  5029.5  787.79
  5038.7  786.63  5072.4  787.15  5134.0  789.56  5154.9  794.15  5167.7  797.87
  5216.8  814.48  5241.3  821.00  5303.3  839.57  5373.3  857.96  5413.5  865.76
#Mann=3,-1,0
  4690.1    0.15       0  4993.2   0.048       0  5006.8    0.15       0
Bank Sta=4993.2,5006.8
XS Rating Curve= 0
Exp/Cntr=0.3,0.1

Type RM Length L Ch R = 1,4531,511,511,511
BEGIN DESCRIPTION:
Little Forbush Creek 9.0
END DESCRIPTION:
XS GIS Cut Line= 3
      1536879.33       881407.04      1536630.63       881391.20
      1536398.49       881385.86
#Sta/Elev= 30
  4726.1  805.73  4736.6  803.73  4757.8  801.01  4776.6  796.59  4789.6  795.27
  4792.9  794.31  4862.8  786.96  4873.6  786.99  4887.7  785.18  4910.1  785.75
  4931.8  785.25  4955.2  785.87  4956.8  785.69  4974.4  779.58  4993.2  779.75
  4993.7  777.25  5006.3  777.25  5006.8  779.75  5011.6  785.41  5018.3  786.42
  5042.4  786.78  5052.8  789.41  5066.7  793.78  5093.8  796.63  5108.2  799.72
  5124.6  800.94  5131.2  803.58  5149.5  805.28  5173.7  809.21  5207.5  813.43
#Mann=3,-1,0
  4726.1    0.15       0  4993.2   0.048       0  5006.8    0.15       0
Bank Sta=4993.2,5006.8
XS Rating Curve= 0
Exp/Cntr=0.3,0.1

Type RM Length L Ch R = 1,4020,500,500,500
BEGIN DESCRIPTION:
Little Forbush Creek 8.0
END DESCRIPTION:
XS GIS Cut Line= 4
      1537187.10       880972.52      1536930.91       880907.31
      1536664.59       880894.29      1536240.45       880950.94
#Sta/Elev= 30
  4469.0  816.13  4506.8  813.04  4553.6  807.59  4590.3  799.62  4607.8  798.60
  4616.7  796.15  4630.9  795.44  4709.4  786.19  4755.7  783.64  4800.2  783.19
  4821.8  781.41  4886.2  782.69  4928.0  782.24  4972.7  783.83  4990.3  781.52
  4993.2  778.78  4993.7  776.28  5006.3  776.28  5006.8  778.78  5042.1  783.77
  5104.3  782.40  5137.0  782.79  5165.7  784.73  5175.9  788.08  5196.7  798.49
  5232.8  813.22  5280.4  829.55  5313.5  838.94  5401.6  860.41  5427.9  865.39
#Mann=3,-1,0
  4469.0    0.15       0  4993.2   0.048       0  5006.8    0.15       0
#XS Ineff=2,0
    0.00 4801.20  797.14 5121.60    0.00  796.82
Permanent Ineff=
       F       F
Bank Sta=4993.2,5006.8
XS Rating Curve= 0
Exp/Cntr=0.3,0.1

Type RM Length L Ch R = 1,3520,500,500,500
BEGIN DESCRIPTION:
Little Forbush Creek 7.0
END DESCRIPTION:
XS GIS Cut Line= 3
      1537256.90       880693.61      1536788.94       880458.29
      1536524.99       880324.99
#Sta/Elev= 30
  4476.2  812.12  4511.7  807.25  4535.1  805.89  4560.9  802.56  4586.1  800.56
  4637.1  797.84  4662.3  795.32  4704.3  789.91  4766.6  784.76  4839.2  781.11
  4851.1  781.11  4870.7  782.20  4916.1  780.14  4957.6  781.21  4993.2  776.59
  4993.7  774.09  5006.3  774.09  5006.8  776.59  5012.3  777.55  5032.4  778.89
  5057.2  778.43  5105.4  779.83  5142.3  788.47  5167.5  798.93  5189.3  806.42
  5213.9  814.21  5227.7  817.54  5250.0  824.41  5270.4  829.59  5295.7  834.80
#Mann=3,-1,0
  4476.2    0.15       0  4993.2   0.048       0  5006.8    0.15       0
Bank Sta=4993.2,5006.8
XS Rating Curve= 0
Exp/Cntr=0.3,0.1

Type RM Length L Ch R = 1,3020,500,500,500
BEGIN DESCRIPTION:
Little Forbush Creek 6.0
END DESCRIPTION:
XS GIS Cut Line= 3
      1537275.01       880325.01      1536923.73       879997.90
      1536675.02       879825.01
#Sta/Elev= 30
  4520.0  806.46  4536.1  804.22  4573.5  801.12  4613.2  793.55  4634.5  790.57
  4647.2  787.98  4654.4  786.99  4696.3  783.53  4756.7  781.92  4777.1  780.92
  4795.9  779.35  4816.1  778.53  4836.6  778.68  4859.1  779.89  4913.1  779.07
  4959.3  776.81  4993.2  775.95  4993.7  773.45  5006.3  773.45  5006.8  775.95
  5037.1  778.72  5081.7  778.83  5101.3  779.58  5121.8  785.22  5161.9  809.09
  5181.8  818.42  5202.7  823.64  5222.6  827.51  5240.9  828.41  5302.9  834.90
#Mann=4,-1,0
  4520.0    0.15       0  4993.2   0.048       0  5006.8    0.15       0
  5240.9    0.08       0
Bank Sta=4993.2,5006.8
XS Rating Curve= 0
Exp/Cntr=0.3,0.1

Type RM Length L Ch R = 1,2520,422,422,422
BEGIN DESCRIPTION:
Little Forbush Creek 5.0
END DESCRIPTION:
XS GIS Cut Line= 3
      1537505.71       879630.94      1537186.72       879645.02
      1536723.64       879706.97
#Sta/Elev= 30
  4680.7  844.16  4727.9  840.67  4765.0  836.15  4818.4  825.97  4914.7  797.85
  4939.5  789.11  4965.0  778.65  4968.3  776.21  4992.7  771.21  4993.2  768.71
  5006.8  768.71  5007.3  771.21  5008.7  772.73  5024.0  776.05  5039.8  777.03
  5058.6  775.80  5099.4  775.65  5126.1  780.46  5144.6  782.64  5181.4  791.38
  5197.1  792.71  5206.9  795.57  5255.8  802.42  5288.0  804.33  5307.2  806.64
  5320.8  810.30  5340.1  812.70  5373.6  815.62  5423.4  822.80  5467.2  830.50
#Mann=5,-1,0
  4680.7    0.08       0  4818.4    0.15       0  4992.7   0.048       0
  5007.3    0.15       0  5373.6    0.08       0
Bank Sta=4992.7,5007.3
XS Rating Curve= 0
Exp/Cntr=0.3,0.1

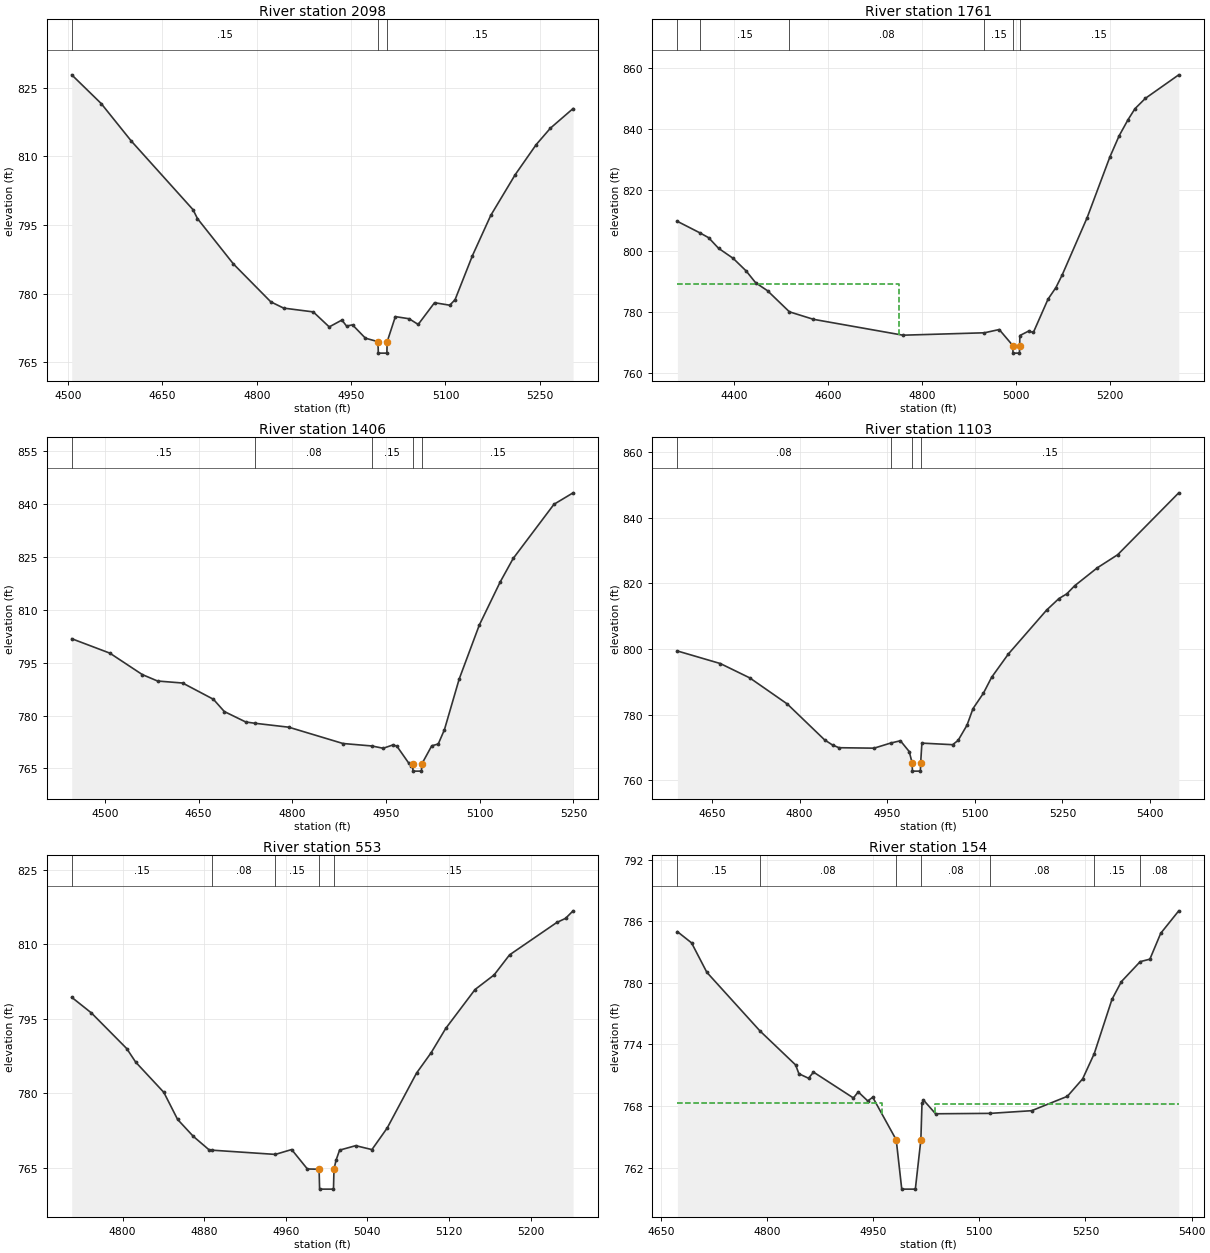
Type RM Length L Ch R = 1,2098,337,337,337
BEGIN DESCRIPTION:
Little Forbush Creek 4.0
END DESCRIPTION:
XS GIS Cut Line= 5
      1537506.28       879375.99      1537142.30       879311.95
      1537063.11       879308.58      1537017.61       879323.75
      1536772.52       879496.93
#Sta/Elev= 30
  4505.9  827.79  4552.7  821.52  4600.7  813.30  4698.7  798.32  4705.8  796.36
  4763.0  786.44  4822.3  778.18  4842.7  776.81  4889.8  775.98  4915.2  772.70
  4935.3  774.20  4942.7  772.89  4952.2  773.14  4972.7  770.24  4992.7  769.47
  4993.2  766.97  5006.8  766.97  5007.3  769.47  5020.3  774.95  5042.2  774.48
  5056.6  773.24  5082.6  777.99  5106.8  777.44  5115.2  778.65  5142.9  788.30
  5171.9  797.06  5210.8  805.97  5244.1  812.53  5266.8  816.14  5302.8  820.42
#Mann=3,-1,0
  4505.9    0.15       0  4992.7   0.048       0  5007.3    0.15       0
Bank Sta=4992.7,5007.3
XS Rating Curve= 0
Exp/Cntr=0.3,0.1

Type RM Length L Ch R = 1,1761,355,355,355
BEGIN DESCRIPTION:
Little Forbush Creek 3.5
END DESCRIPTION:
XS GIS Cut Line= 4
      1537538.96       879098.14      1537119.18       879038.90
      1536810.15       879064.66      1536480.49       879098.14
#Sta/Elev= 30
  4280.0  809.77  4327.1  806.05  4346.4  804.40  4367.5  800.92  4398.5  797.62
  4426.0  793.50  4446.3  789.60  4471.5  786.99  4518.0  780.06  4569.2  777.59
  4759.3  772.38  4932.4  773.17  4963.9  774.24  4992.7  768.99  4993.2  766.49
  5006.8  766.49  5007.3  768.99  5007.7  772.26  5026.6  773.75  5036.4  773.27
  5067.7  784.25  5084.3  788.01  5097.8  792.21  5150.8  811.02  5198.8  830.83
  5218.8  837.91  5237.8  843.22  5252.4  846.78  5274.5  850.18  5345.4  857.90
#Mann=6,-1,0
  4280.0    0.08       0  4327.1    0.15       0  4518.0    0.08       0
  4932.4    0.15       0  4992.7   0.048       0  5007.3    0.15       0
#XS Ineff=2,0
    0.00 4751.60  789.22               0
Permanent Ineff=
       F       F
Bank Sta=4992.7,5007.3
XS Rating Curve= 0
Exp/Cntr=0.3,0.1

Type RM Length L Ch R = 1,1406,303,303,303
BEGIN DESCRIPTION:
Little Forbush Creek 3.0
END DESCRIPTION:
XS GIS Cut Line= 3
      1537480.94       878835.11      1536916.52       878727.28
      1536689.05       878715.48
#Sta/Elev= 30
  4447.1  801.78  4508.1  797.69  4560.1  791.61  4584.5  789.79  4624.6  789.22
  4673.9  784.61  4691.3  781.14  4725.6  778.18  4740.6  777.81  4794.5  776.70
  4881.2  772.08  4927.5  771.38  4945.6  770.73  4961.4  771.69  4967.5  771.32
  4986.3  766.57  4990.2  765.82  4992.7  766.25  4993.2  764.25  5006.8  764.25
  5007.3  766.25  5023.3  771.43  5033.7  771.94  5043.6  776.00  5067.2  790.35
  5099.4  805.65  5132.7  817.82  5153.6  824.52  5218.9  839.88  5249.5  843.13
#Mann=5,-1,0
  4447.1    0.15       0  4740.6    0.08       0  4927.5    0.15       0
  4992.7   0.048       0  5007.3    0.15       0
Bank Sta=4992.7,5007.3
XS Rating Curve= 0
Exp/Cntr=0.3,0.1

Type RM Length L Ch R = 1,1103,550,550,550
BEGIN DESCRIPTION:
Little Forbush Creek 2.0
END DESCRIPTION:
XS GIS Cut Line= 4
      1537350.05       878323.75      1537106.20       878380.02
      1536891.98       878461.36      1536582.95       878681.11
#Sta/Elev= 30
  4590.7  799.41  4664.2  795.58  4714.6  791.21  4778.9  783.25  4842.8  772.31
  4856.4  770.74  4867.4  769.92  4927.5  769.78  4955.8  771.33  4972.6  772.04
  4987.7  768.75  4992.7  765.28  4993.2  762.78  5006.8  762.78  5007.3  765.28
  5009.4  771.32  5062.0  770.84  5071.4  772.14  5086.7  776.80  5096.9  781.83
  5114.7  786.52  5128.9  791.41  5157.4  798.47  5223.0  811.88  5244.1  815.40
  5257.5  816.82  5270.8  819.26  5309.6  824.74  5344.7  828.76  5449.3  847.63
#Mann=4,-1,0
  4590.7    0.08       0  4955.8    0.15       0  4992.7   0.048       0
  5007.3    0.15       0
Bank Sta=4992.7,5007.3
XS Rating Curve= 0
Exp/Cntr=0.3,0.1

Type RM Length L Ch R = 1,553,399,399,399
BEGIN DESCRIPTION:
Little Forbush Creek 1.0
END DESCRIPTION:
XS GIS Cut Line= 3
      1536819.52       877898.32      1536618.58       878030.26
      1536437.53       878204.27
#Sta/Elev= 30
  4750.2  799.33  4769.5  796.18  4804.1  789.01  4812.9  786.28  4840.5  780.19
  4854.0  774.74  4869.4  771.33  4884.8  768.63  4887.3  768.56  4949.8  767.70
  4965.8  768.68  4981.2  764.77  4992.7  764.71  4993.2  760.71  5006.8  760.71
  5007.3  764.71  5009.3  766.52  5012.8  768.56  5028.6  769.46  5044.5  768.67
  5059.5  773.03  5088.2  784.06  5102.6  788.19  5116.8  793.05  5145.6  800.90
  5164.3  803.84  5179.4  807.87  5225.7  814.39  5234.3  815.22  5241.7  816.74
#Mann=5,-1,0
  4750.2    0.15       0  4887.3    0.08       0  4949.8    0.15       0
  4992.7   0.048       0  5007.3    0.15       0
Bank Sta=4992.7,5007.3
XS Rating Curve= 0
Exp/Cntr=0.5,0.3

Type RM Length L Ch R = 1,154,46,46,46
BEGIN DESCRIPTION:
Mount Carmel Church Rd (LFC) US
END DESCRIPTION:
XS GIS Cut Line= 6
      1536700.64       877841.06      1536566.71       877788.70
      1536451.51       877710.27      1536397.58       877707.82
      1536177.41       877688.68      1536050.73       877769.46
#Sta/Elev= 30
  4673.4  784.98  4693.4  783.89  4715.0  781.02  4790.2  775.30  4840.4  772.00
  4845.1  771.14  4858.7  770.70  4865.7  771.30  4922.1  768.78  4928.9  769.37
  4942.4  768.49  4949.4  768.85  4982.6  764.70  4990.4  759.90  5009.6  759.90
  5017.4  764.70  5019.0  768.25  5021.1  768.58  5038.2  767.24  5115.5  767.28
  5173.9  767.54  5224.4  768.94  5246.0  770.64  5262.4  773.10  5287.4  778.38
  5300.8  780.12  5327.3  782.06  5341.0  782.30  5356.3  784.82  5381.8  787.01
#Mann=7,-1,0
  4673.4    0.15       0  4790.2    0.08       0  4982.6   0.048       0
  5017.4    0.08       0  5115.5    0.08       0  5262.4    0.15       0
  5327.3    0.08       0
#XS Ineff=2,0
    0.00 4963.00  768.26 5037.00    0.00  768.20
Permanent Ineff=
       F       F
Bank Sta=4982.6,5017.4
XS Rating Curve= 0
Exp/Cntr=0.5,0.3

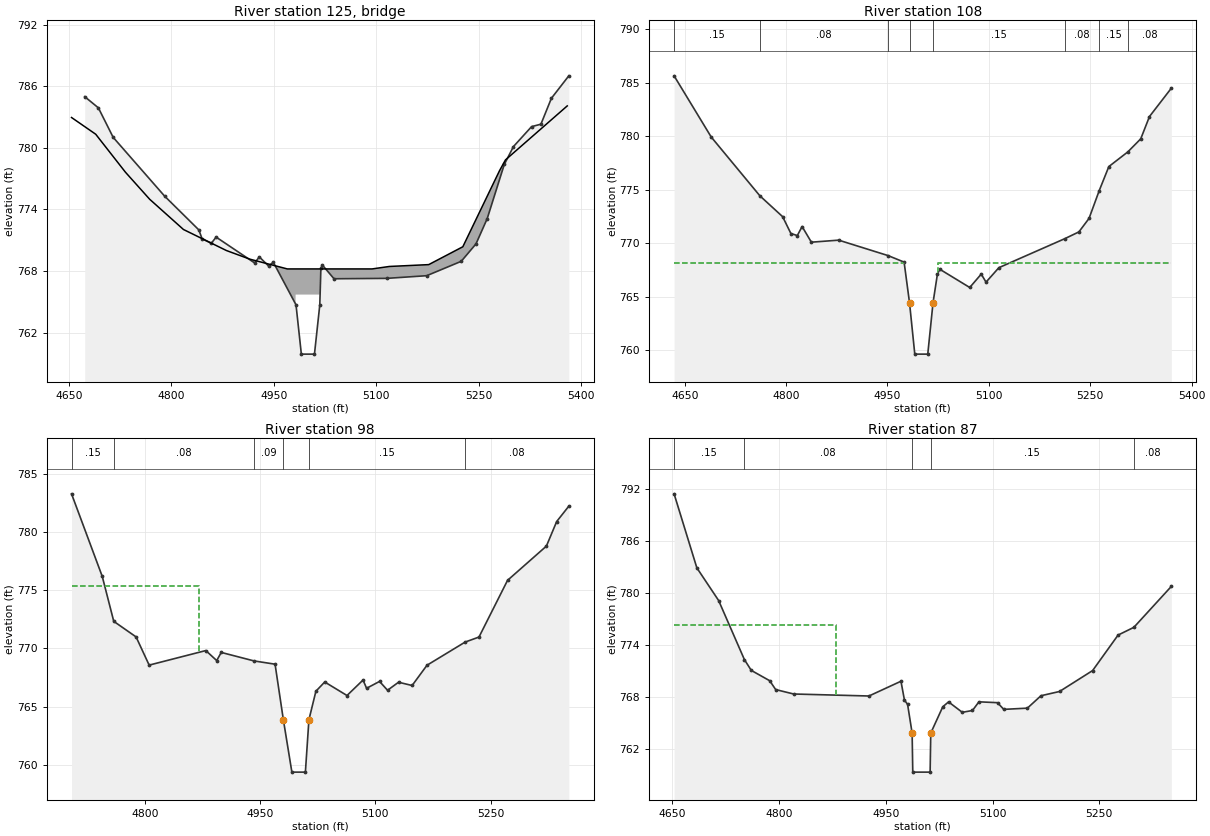
Type RM Length L Ch R =3,125,,,
BEGIN DESCRIPTION:
Mount Carmel Church Rd (LFC) TOR
Structure ID: LDS_LFC_01
Approximate Survey Structure
END DESCRIPTION:
Bridge Culvert--1,0,-1,-1,0
Deck Dist Width WeirC Skew NumUp NumDn MinLoCord MaxHiCord MaxSubmerge Is_Ogee
19,20,3,,19,19,,,0.95,0,1,1,,,
  4654.1  4689.5  4733.0  4768.4  4817.9  4880.8  4915.1  4969.9  4982.0  4982.0
  5018.0  5018.0  5093.9  5119.2  5176.8  5226.7  5280.4  5289.1  5379.5
  782.95  781.32  777.62  774.99  772.04  769.99  769.15  768.20  768.20  768.20
  768.20  768.20  768.20  768.44  768.62  770.36  777.77  778.82  784.08
  739.90  739.90  739.90  739.90  739.90  739.90  739.90  739.90  739.90  765.70
  765.70  739.90  739.90  739.90  739.90  739.90  739.90  739.90  739.90
  4654.1  4689.5  4733.0  4768.4  4817.9  4880.8  4915.1  4969.9  4982.0  4982.0
  5018.0  5018.0  5093.9  5119.2  5176.8  5226.7  5280.4  5289.1  5379.5
  782.95  781.32  777.62  774.99  772.04  769.99  769.15  768.20  768.20  768.20
  768.20  768.20  768.20  768.44  768.62  770.36  777.77  778.82  784.08
  739.90  739.90  739.90  739.90  739.90  739.90  739.90  739.90  739.90  765.70
  765.70  739.90  739.90  739.90  739.90  739.90  739.90  739.90  739.90
BR Coef=1,1,0,1.25,0,,,0.8,0,2,0,
WSPro=,,,, 1 ,,,, 0 ,,,, 0 ,,,,-1 ,-1 ,-1 , 0 , 0 , 0 , 0 , 0
BC Design=,,0,,0,,,,,,

Type RM Length L Ch R = 1,108,10,10,10
BEGIN DESCRIPTION:
Mount Carmel Church Rd (LFC) DS
END DESCRIPTION:
XS GIS Cut Line= 6
      1536715.33       877824.54      1536618.04       877785.99
      1536432.61       877675.83      1536285.73       877651.96
      1536182.91       877655.63      1536045.17       877743.79
#Sta/Elev= 30
  4634.3  785.63  4689.2  779.92  4761.2  774.43  4794.9  772.48  4807.1  770.91
  4816.6  770.72  4823.7  771.56  4837.4  770.10  4877.8  770.29  4950.8  768.85
  4974.6  768.24  4982.6  764.45  4990.4  759.65  5009.6  759.65  5017.4  764.45
  5023.9  767.13  5027.5  767.57  5071.7  765.87  5088.7  767.12  5095.8  766.37
  5114.8  767.72  5212.4  770.43  5233.2  771.06  5248.2  772.32  5263.3  774.92
  5277.5  777.16  5305.6  778.53  5324.7  779.75  5337.6  781.83  5370.0  784.48
#Mann=8,-1,0
  4634.3    0.15       0  4761.2    0.08       0  4950.8    0.15       0
  4982.6   0.048       0  5017.4    0.15       0  5212.4    0.08       0
  5263.3    0.15       0  5305.6    0.08       0
#XS Ineff=2,0
    0.00 4975.00  768.20 5025.00    0.00  768.20
Permanent Ineff=
       F       F
Bank Sta=4982.6,5017.4
XS Rating Curve= 0
Exp/Cntr=0.5,0.3

Type RM Length L Ch R = 1,98,11,11,11
BEGIN DESCRIPTION:
Little Forbush Creek 0.9
END DESCRIPTION:
XS GIS Cut Line= 6
      1536658.88       877770.62      1536424.05       877667.89
      1536356.71       877652.35      1536226.35       877640.26
      1536181.45       877649.76      1536057.96       877726.62
#Sta/Elev= 30
  4704.2  783.27  4744.2  776.18  4759.2  772.32  4788.3  770.98  4805.3  768.56
  4879.1  769.81  4893.3  768.95  4899.2  769.65  4941.9  768.92  4969.3  768.64
  4980.1  763.87  4991.2  759.37  5008.8  759.37  5013.4  763.87  5022.5  766.32
  5034.0  767.11  5063.0  765.95  5083.9  767.28  5088.5  766.57  5105.4  767.16
  5115.8  766.40  5130.1  767.09  5147.8  766.81  5167.2  768.55  5216.9  770.54
  5234.9  770.97  5272.1  775.84  5322.7  778.78  5336.1  780.89  5351.9  782.21
#Mann=6,-1,0
  4704.2    0.15       0  4759.2    0.08       0  4941.9    0.09       0
  4980.1   0.048       0  5013.4    0.15       0  5216.9    0.08       0
#XS Ineff=2,0
    0.00 4870.70  775.32               0
Permanent Ineff=
       F       F
Bank Sta=4980.1,5013.4
XS Rating Curve= 0
Exp/Cntr=0.3,0.1

Type RM Length L Ch R = 1,87,0,0,0
BEGIN DESCRIPTION:
Little Forbush Creek 0.5
END DESCRIPTION:
XS GIS Cut Line= 5
      1536707.96       877773.12      1536581.32       877723.56
      1536417.92       877650.13      1536204.95       877631.77
      1536056.25       877714.37
#Sta/Elev= 30
  4652.3  791.40  4684.3  782.87  4714.9  779.11  4751.1  772.31  4760.8  771.06
  4786.7  769.87  4795.1  768.85  4820.4  768.34  4926.2  768.11  4971.2  769.81
  4976.1  767.64  4980.5  767.15  4986.9  763.84  4987.8  759.34  5012.2  759.34
  5013.1  763.84  5030.0  766.87  5038.1  767.43  5057.4  766.23  5071.7  766.44
  5080.8  767.44  5106.9  767.34  5115.7  766.57  5148.9  766.71  5168.0  768.14
  5194.1  768.63  5240.6  771.04  5276.4  775.13  5298.6  776.02  5351.3  780.74
#Mann=5,-1,0
  4652.3    0.15       0  4751.1    0.08       0  4986.9   0.048       0
  5013.1    0.15       0  5298.6    0.08       0
#XS Ineff=2,0
    0.00 4879.20  776.32               0
Permanent Ineff=
       F       F
Bank Sta=4986.9,5013.1
XS Rating Curve= 0
Exp/Cntr=0.3,0.1

Chan Stop Cuts=-1