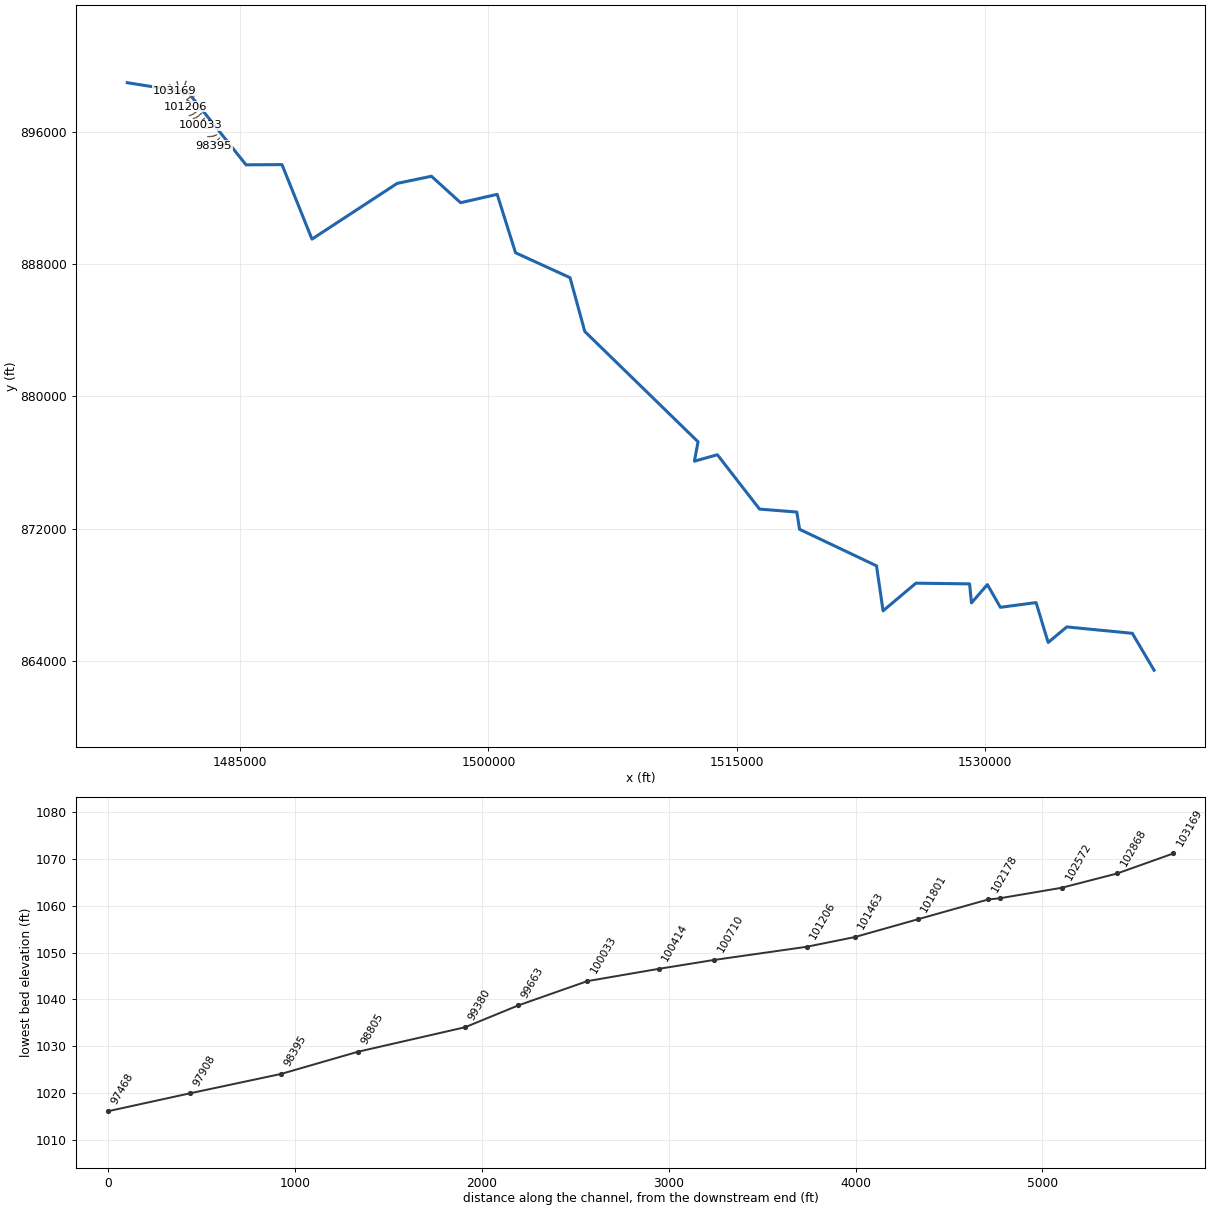
--- North Deep Creek.prj (project) ---

Proj Title=North Deep Creek Limited Detail Study
Current Plan=p01
Default Exp/Contr=0.3,0.1
English Units
Geom File=g01
Flow File=f01
Plan File=p01
Y Axis Title=Elevation
X Axis Title(PF)=Main Channel Distance
X Axis Title(XS)=Station
BEGIN DESCRIPTION:
North Deep Creek
END DESCRIPTION:
DSS Export Rating Curves= 0
DSS Export Rating Curve Sorted= 0
DSS Export Volume Flow Curves= 0
DXF OffsetX= 0
DXF OffsetY= 0
DXF ScaleX= 1
DXF ScaleY= 10

--- North Deep Creek.p01 (plan) ---

Plan Title=Floodway Run
Program Version=3.12
Short Identifier=Floodway
Geom File=g01
Flow File=f01
Subcritical Flow
K Sum by GR= 0
Std Step Tol= 0.01
Critical Tol= 0.01
Num of Std Step Trials= 20
Max Error Tol= 0.3
Flow Tol Ratio= 0.001
Split Flow NTrial= 30
Split Flow Tol= 0.02
Split Flow Ratio= 0.02
Log Output Level= 0
Friction Slope Method= 0
Unsteady Friction Slope Method= 2
Unsteady Bridges Friction Slope Method= 1
Calc Critical at every XS
Parabolic Critical Depth
Global Vel Dist= 0 , 0 , 0
Global Log Level= 0
CheckData=True
Encroach Param=-1 ,5,5, 2
Encroach River=North Deep Creek
Encroach Reach=Reach-1
Encroach Node=103169
       1    4975    5025
Encroach Node=102868
       1    4953    5031
Encroach Node=102572
       1    4875    5011
Encroach Node=102239
       1    4973    5065
Encroach Node=102178
       1    4973    5065
Encroach Node=101801
       1    4962    5063
Encroach Node=101463
       1    4962    5037
Encroach Node=101206
       1    4941    5007
Encroach Node=100710
       1    4940    5005
Encroach Node=100414
       1    4890    5007
Encroach Node=100033
       1    4990    5099
Encroach Node=99663
       1    4991    5039
Encroach Node=99380
       1    4988    5064
Encroach Node=98805
       1    4975    5008
Encroach Node=98395
       1    4990    5133
Encroach Node=97908
       1    4981    5034
Encroach Node=97468
       1    4941    5012
Encroach Node=97330
       1    4943    5023
Encroach Node=96851
       1    4986    5060
Encroach Node=96529
       1    4965    5042
Encroach Node=96097
       1    4916    5131
Encroach Node=95774
       1    4776    5010
Encroach Node=95536
       1    4843    5061
Encroach Node=95398
       1    4843    5061
Encroach Node=95178
       1    4908    5154
Encroach Node=94945
       1    4982    5176
Encroach Node=94441
       1    4915    5120
Encroach Node=94070
       1    4936    5250
Encroach Node=93388
       1    4918    5179
Encroach Node=93004
       1    4871    5180
Encroach Node=92618
       1    4880    5152
Encroach Node=92062
       1    4800    5388
Encroach Node=91819
       1    4959    5010
Encroach Node=91577
       1    4868    5025
Encroach Node=91330
       1    4870    5020
Encroach Node=91149
       1    4945    5065
Encroach Node=90908
       1    4855    5010
Encroach Node=90608
       1    4908    5010
Encroach Node=90476
       1    4957    5013
Encroach Node=90203
       1    4977    5018
Encroach Node=90045
       1    4973    5036
Encroach Node=89949
       1    4970    5033
Encroach Node=89702
       1    4961    5014
Encroach Node=89401
       1    4980    5030
Encroach Node=89150
       1    4947    5013
Encroach Node=88813
       1    4850    5020
Encroach Node=88407
       1    4925    5018
Encroach Node=88093
       1    4970    5010
Encroach Node=87813
       1    4950    5025
Encroach Node=87531
       1    4950    5030
Encroach Node=87439
       1    4937    5021
Encroach Node=87046
       1    4900    5035
Encroach Node=86736
       1    4951    5011
Encroach Node=86359
       1    4985    5018
Encroach Node=86082
       1    4955    5031
Encroach Node=85914
       1    4964    5010
Encroach Node=85771
       1    4951    5010
Encroach Node=85551
       1    4989    5083
Encroach Node=85115
       1    4989    5090
Encroach Node=84922
       1    4989    5088
Encroach Node=84719
       1    4989    5105
Encroach Node=84500
       1    4891    5010
Encroach Node=84358
       1    4868    5010
Encroach Node=84085
       1    4979    5012
Encroach Node=83910
       1    4988    5013
Encroach Node=83636
       1    4988    5018
Encroach Node=83424
       1    4988    5013
Encroach Node=83315
       1    4988    5016
Encroach Node=82921
       1    4988    5077
Encroach Node=82628
       1    4988    5027
Encroach Node=82435
       1    4988    5054
Encroach Node=82205
       1    4977    5016
Encroach Node=81740
       1    4988    5041
Encroach Node=81523
       1    4978    5032
Encroach Node=81299
       1    4977    5036
Encroach Node=81020
       1    4876    5016
Encroach Node=80738
       1    4889    5031
Encroach Node=80444
       1    4988    5049
Encroach Node=80238
       1    4984    5014
Encroach Node=80097
       1    4985    5012
Encroach Node=79669
       1    4987    5025
Encroach Node=79315
       1    4987    5013
Encroach Node=78966
       1    4984    5022
Encroach Node=78588
       1    4987    5058
Encroach Node=78322
       1    4934    5016
Encroach Node=78057
       1    4987    5025
Encroach Node=77919
       1    4979    5022
Encroach Node=77733
       1    4984    5056
Encroach Node=77481
       1    4987    5029
Encroach Node=77166
       1    4917    5013
Encroach Node=76890
       1    4959    5030
Encroach Node=76692
       1    4986    5029
Encroach Node=76451
       1    4956    5100
Encroach Node=76390
       1    4955    5069
Encroach Node=76297
       1    4966    5034
Encroach Node=76074
       1    4980    5075
Encroach Node=75734
       1    4970    5025
Encroach Node=75439
       1    4977    5016
Encroach Node=74973
       1    4971    5012
Encroach Node=74694
       1    4934    5178
Encroach Node=74085
       1    4894    5124
Encroach Node=73687
       1    4987    5204
Encroach Node=73136
       1    4800    5027
Encroach Node=72845
       1    4768    5091
Encroach Node=72456
       1    4877    5093
Encroach Node=72266
       1    4925    5075
Encroach Node=72149
       1    4950    5050
Encroach Node=72127
       1    4945    5045
Encroach Node=72110
       1    4925    5045
Encroach Node=72082
       1    4915    5037
Encroach Node=71992
       1    4915    5012
Encroach Node=71821
       1    4960    5030
Encroach Node=71577
       1    4986    5049
Encroach Node=71147
       1    4971    5048
Encroach Node=70951
       1    4972    5024
Encroach Node=70599
       1    4969    5015
Encroach Node=70345
       1    4978    5039
Encroach Node=70156
       1    4981    5049
Encroach Node=69766
       1    4944    5061
Encroach Node=69441
       1    4945    5129
Encroach Node=69042
       1    4962    5029
Encroach Node=68817
       1    4933    5035
Encroach Node=68547
       1    4905    5076
Encroach Node=68190
       1    4874    5162
Encroach Node=67895
       1    4825    5104
Encroach Node=67657
       1    4847    5015
Encroach Node=67429
       1    4869    5015
Encroach Node=67153
       1    4759    5015
Encroach Node=66794
       1    4955    5090
Encroach Node=66564
       1    4935    5025
Encroach Node=66110
       1    4871    5015
Encroach Node=65795
       1    4898    5080
Encroach Node=65288
       1    4900    5140
Encroach Node=65087
       1    4924    5140
Encroach Node=64920
       1    4924    5125
Encroach Node=64781
       1    4975    5030
Encroach Node=64653
       1  4979.5    5028
Encroach Node=64500
       1    4971    5030
Encroach Node=64360
       1    4955    5030
Encroach Node=64099
       1    4925    5035
Encroach Node=63652
       1    4850    5100
Encroach Node=63082
       1    4750    5228
Encroach Node=62586
       1    4750    5200
Encroach Node=62169
       1    4834    5073
Encroach Node=61862
       1    4822    5048
Encroach Node=61600
       1    4787    5070
Encroach Node=61312
       1    4960    5078
Encroach Node=61066
       1    4893    5087
Encroach Node=60937
       1    4890    5089
Encroach Node=60585
       1    4872    5023
Encroach Node=60130
       1    4906    5023
Encroach Node=59610
       1    4906    5037
Encroach Node=59027
       1    4583    5025
Encroach Node=58705
       1    4670    5025
Encroach Node=58327
       1    4700    5025
Encroach Node=57931
       1    4700    5156
Encroach Node=57435
       1    4865    5310
Encroach Node=57202
       1    4875    5200
Encroach Node=56828
       1    4870    5240
Encroach Node=56545
       1    4915    5290
Encroach Node=56178
       1    4930    5200
Encroach Node=56072
       1    4925    5200
Encroach Node=55942
       1    4908    5149
Encroach Node=55644
       1    4954    5207
Encroach Node=55332
       1    4835    5087
Encroach Node=54979
       1    4762    5024
Encroach Node=54641
       1    4824    5123
Encroach Node=54280
       1    4950    5185
Encroach Node=54068
       1    4922    5184
Encroach Node=53775
       1    4898    5210
Encroach Node=53517
       1    4978    5183
Encroach Node=53293
       1    4861    5051
Encroach Node=53017
       1    4670    5055
Encroach Node=52528
       1    4975    5334
Encroach Node=52197
       1    4759    5020
Encroach Node=51916
       1    4848    5148
Encroach Node=51322
       1    4973    5287
Encroach Node=50940
       1    4750    5117
Encroach Node=50737
       1    4825    5026
Encroach Node=50612
       1    4923    5051
Encroach Node=50491
       1    4870    5058
Encroach Node=50420
       1    4875    5040
Encroach Node=50092
       1    4921    5120
Encroach Node=49724
       1    4907    5065
Encroach Node=49545
       1    4947    5106
Encroach Node=49180
       1    4968    5098
Encroach Node=48849
       1    4829    5098
Encroach Node=48534
       1    4879    5037
Encroach Node=48102
       1    4921    5093
Encroach Node=47762
       1    4880    5202
Encroach Node=47374
       1    4970    5433
Encroach Node=47087
       1    4933    5297
Encroach Node=46492
       1    4643    5023
Encroach Node=45968
       1    4711    5049
Encroach Node=45759
       1    4600    5018
Encroach Node=45420
       1    4825    5086
Encroach Node=45114
       1    4599    5023
Encroach Node=44653
       1    4957    5225
Encroach Node=44428
       1    4976    5335
Encroach Node=44190
       1    4971    5195
Encroach Node=43998
       1    4968    5108
Encroach Node=43644
       1    4793    5072
Encroach Node=43279
       1    4850    5165
Encroach Node=42904
       1    4782    5025
Encroach Node=42578
       1    4754    5181
Encroach Node=42252
       1    4756    5035
Encroach Node=41825
       1    4749    5128
Encroach Node=41574
       1    4679    5028
Encroach Node=41225
       1    4810    5026
Encroach Node=40848
       1    4982    5275
Encroach Node=40491
       1    4879    5350
Encroach Node=39815
       1    4763    5300
Encroach Node=39191
       1    4687    5056
Encroach Node=38827
       1    4806    5026
Encroach Node=38552
       1    4914    5029
Encroach Node=38007
       1    4875    5028
Encroach Node=37575
       1    4641    5034
Encroach Node=37452
       1    4670    5077
Encroach Node=37222
       1    4670    5110
Encroach Node=36864
       1    4800    5175
Encroach Node=36422
       1    4950    5375
Encroach Node=36113
       1    4895    5377
Encroach Node=35776
       1    4889    5170
Encroach Node=35615
       1    4946    5120
Encroach Node=35409
       1    4887    5119
Encroach Node=35223
       1    4856    5027
Encroach Node=34925
       1    4856    5033
Encroach Node=34400
       1    4955    5025
Encroach Node=33964
       1    4932    5096
Encroach Node=33699
       1    4911    5143
Encroach Node=33217
       1    4761    5130
Encroach Node=32789
       1    4633    5031
Encroach Node=32462
       1    4625    5025
Encroach Node=31871
       1    4763    5030
Encroach Node=31431
       1    4815    5033
Encroach Node=30853
       1    4736    5083
Encroach Node=30401
       1    4865    5050
Encroach Node=30024
       1    4960    5058
Encroach Node=29770
       1    4944    5030
Encroach Node=29441
       1    4962    5030
Encroach Node=29024
       1    4970    5030
Encroach Node=28650
       1    4969    5080
Encroach Node=28309
       1    4970    5030
Encroach Node=27925
       1    4956    5046
Encroach Node=27485
       1    4950    5206
Encroach Node=26976
       1    4866    5200
Encroach Node=26704
       1    4759    5101
Encroach Node=26159
       1    4953    5297
Encroach Node=25484
       1    4654    5145
Encroach Node=24958
       1    4747    5039
Encroach Node=24266
       1    4870    5136
Encroach Node=23824
       1    4842    5037
Encroach Node=23471
       1    4945    5152
Encroach Node=23187
       1    4950    5245
Encroach Node=22972
       1    4969    5196
Encroach Node=22570
       1    4977    5146
Encroach Node=22399
       1    4971    5104
Encroach Node=22018
       1    4967    5021
Encroach Node=21663
       1    4963    5034
Encroach Node=21268
       1    4920    5035
Encroach Node=20966
       1    4960    5035
Encroach Node=20664
       1    4915    5038
Encroach Node=20269
       1    4903    5032
Encroach Node=19795
       1    4960    5160
Encroach Node=19634
       1    4973    5170
Encroach Node=19437
       1    4975    5050
Encroach Node=19245
       1    4968    5031
Encroach Node=19027
       1    4973    5026
Encroach Node=18719
       1    4970    5029
Encroach Node=18406
       1    4968    5036
Encroach Node=18006
       1    4976    5035
Encroach Node=17919
       1    4964    5050
Encroach Node=17858
       1    4969    5038
Encroach Node=17525
       1    4973    5109
Encroach Node=17208
       1    4972    5060
Encroach Node=17073
       1    4951    5100
Encroach Node=16946
       1    4954    5090
Encroach Node=16695
       1    4964    5050
Encroach Node=16441
       1  4968.2  5031.8
Encroach Node=16133
       1 4957.41 5042.95
Encroach Node=15881
       1 4967.03  5031.8
Encroach Node=15522
       1  4968.2  5031.8
Encroach Node=15224
       1  4968.2  5031.8
Encroach Node=14831
       1  4962.8  5037.2
Encroach Node=14290
       1  4968.2  5031.8
Encroach Node=13992
       1  4968.2  5031.8
Encroach Node=13553
       1  4965.5    5033
Encroach Node=13132
       1  4962.8  5037.2
Encroach Node=12743
       1  4962.8  5037.2
Encroach Node=12450
       1  4973.6  5026.4
Encroach Node=12141
       1  4968.2  5031.8
Encroach Node=11798
       1 4933.16 5043.23
Encroach Node=11483
       1 4971.85  5031.1
Encroach Node=11077
       1 4960.68 5051.83
Encroach Node=10967
       1  4957.2 5047.76
Encroach Node=10465
       1  4967.7  5068.8
Encroach Node=10246
       1 4939.48    5035
Encroach Node=9959
       1 4922.84  5032.3
Encroach Node=9687
       1 4958.36  5032.3
Encroach Node=9485
       1    4950    5050
Encroach Node=9182
       1    4955    5035
Encroach Node=8960
       1    4937    5035
Encroach Node=8636
       1    4967    5070
Encroach Node=7990
       1    4800    5035
Encroach Node=7457
       1    4975    5135
Encroach Node=7063
       1    4979    5030
Encroach Node=6861
       1    4973    5030
Encroach Node=6517
       1    4967    5036
Encroach Node=6315
       1    4967    5029
Encroach Node=6034
       1    4967    5023
Encroach Node=5637
       1    4964    5028
Encroach Node=5307
       1    4960    5028
Encroach Node=4947
       1    4960    5025
Encroach Node=4433
       1    4935    5075
Encroach Node=3939
       1    4925    5200
Encroach Node=3332
       1    4730    5180
Encroach Node=2797
       1    4650    5125
Encroach Node=2405
       1    4675    5125
Encroach Node=2132
       1    4870    5130
Encroach Node=1996
       1    4925    5100
Encroach Node=1687
       1    4820    5250
Encroach Node=1334
       1    4850    5175
Encroach Node=1189
       1    4931    5069
Encroach Node=1179
       1    4933    5068
Encroach Node=1051
       1 4891.89 5101.77
Encroach Node=777
       1 4769.58  5201.4
BEGIN DESCRIPTION:
Floodway Run
END DESCRIPTION:
Computation Interval=1HOUR
Output Interval=1HOUR
Run HTab= 0
Run UNet= 0
Run PostProcess= 0
UNET Theta= 1
UNET Theta Warmup= 1
UNET ZTol= 0.02
UNET ZSATol= 0.05
UNET MxIter= 20
UNET MaxInSteps= 0
UNET DtIC= 0
UNET DtMin= 0
UNET MaxCRTS= 20
UNET WFStab= 2
UNET SFStab= 1
UNET WFX= 1
UNET SFX= 1
UNET DSS MLevel= 4
UNET DZMax Abort= 100
UNET Convert EG Bridges=-1
UNET Use Existing IB Tables=-1
UNET Froude Reduction=False
UNET Froude Limit= 1
UNET Froude Power= 10
Instantaneous Interval=1HOUR
Write IC File= 0
Echo Input=False
Echo Output=False
Write Detailed= 0
Detailed Automatic Start=False, 10

--- North Deep Creek.f01 (steady flow) ---

Flow Title=Floodway
Number of Profiles=2
Profile Names=100-year,100-FW
River Rch & RM= North Deep Creek,Reach-1,103169
     677     677
River Rch & RM= North Deep Creek,Reach-1,101801
     835     835
River Rch & RM= North Deep Creek,Reach-1,99380
     927     927
River Rch & RM= North Deep Creek,Reach-1,97330
    1118    1118
River Rch & RM= North Deep Creek,Reach-1,96851
    1228    1228
River Rch & RM= North Deep Creek,Reach-1,94070
    1393    1393
River Rch & RM= North Deep Creek,Reach-1,91149
    1543    1543
River Rch & RM= North Deep Creek,Reach-1,89401
    1735    1735
River Rch & RM= North Deep Creek,Reach-1,84085
    2007    2007
River Rch & RM= North Deep Creek,Reach-1,79669
    2244    2244
River Rch & RM= North Deep Creek,Reach-1,76451
    2319    2319
River Rch & RM= North Deep Creek,Reach-1,73687
    2476    2476
River Rch & RM= North Deep Creek,Reach-1,71147
    2584    2584
River Rch & RM= North Deep Creek,Reach-1,66110
    2692    2692
River Rch & RM= North Deep Creek,Reach-1,64920
    2722    2722
River Rch & RM= North Deep Creek,Reach-1,63652
    5160    5160
River Rch & RM= North Deep Creek,Reach-1,60585
    5270    5270
River Rch & RM= North Deep Creek,Reach-1,59027
    5746    5746
River Rch & RM= North Deep Creek,Reach-1,52197
    6311    6311
River Rch & RM= North Deep Creek,Reach-1,49545
    6644    6644
River Rch & RM= North Deep Creek,Reach-1,47374
    6717    6717
River Rch & RM= North Deep Creek,Reach-1,43279
    6895    6895
River Rch & RM= North Deep Creek,Reach-1,37222
    7034    7034
River Rch & RM= North Deep Creek,Reach-1,33699
    7106    7106
River Rch & RM= North Deep Creek,Reach-1,27485
    7441    7441
River Rch & RM= North Deep Creek,Reach-1,22399
    7569    7569
River Rch & RM= North Deep Creek,Reach-1,19795
    7729    7729
River Rch & RM= North Deep Creek,Reach-1,11077
    7857    7857
River Rch & RM= North Deep Creek,Reach-1,5637
    8002    8002
Boundary for River Rch & Prof#=North Deep Creek,Reach-1,1
Up Type=0
Dn Type=3
Dn Slope=0.002
Boundary for River Rch & Prof#=North Deep Creek,Reach-1,2
Up Type=0
Dn Type=3
Dn Slope=0.002

--- North Deep Creek.g01 (geometry) ---

Geom Title=Existing Conditions
Program Version=3.12

River Reach=North Deep Creek,Reach-1
Reach XY= 30
      1478181.13       898968.56      1481855.75       898389.75
       1485358.4        894002.8      1487530.62       894015.45
      1489341.36       889509.44      1494489.76       892879.44
      1496560.77       893312.15      1498322.75       891711.81
        1500533.       892217.69        1501642.       888684.25
      1504935.38       887177.31      1505827.13       883921.88
       1512668.5       877251.94      1512449.75       876079.19
      1513836.75       876469.63       1516384.5       873181.19
      1518637.62       873003.77      1518802.88       871959.81
      1523452.88       869749.56      1523849.38       867028.81
      1525834.88       868701.38      1529075.63       868658.94
      1529189.63       867505.94      1530151.25       868616.38
      1530936.63       867241.63      1533093.75       867527.19
      1533824.38       865116.38       1534948.5       866055.19
      1538907.25       865669.31      1540223.75       863436.69

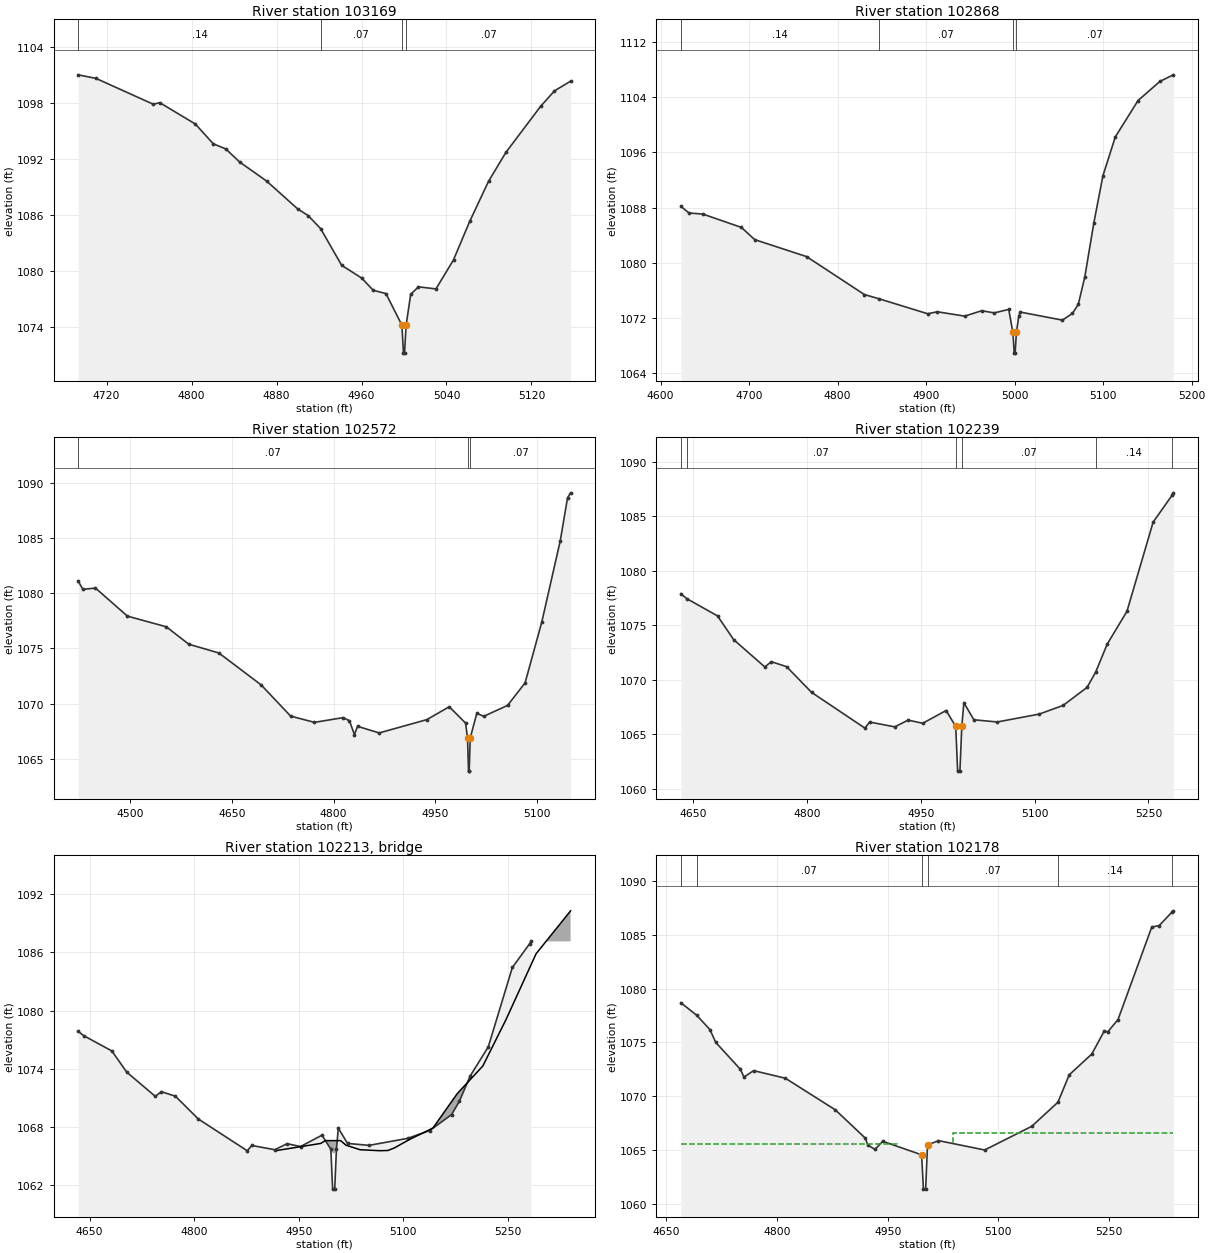
Type RM Length L Ch R = 1 ,103169  ,301,301,301
BEGIN DESCRIPTION:
North Deep Creek 302.0
END DESCRIPTION:
XS GIS Cut Line= 4
        1480749.       898843.65       1480892.4       898694.94
      1480916.29        898615.3      1481025.16       898479.87
#Sta/Elev= 30
  4693.3 1101.01    4710 1100.63    4764 1097.86  4770.1 1098.03  4803.6 1095.74
  4820.5 1093.62  4832.3 1093.07  4845.2 1091.68  4870.6 1089.64  4899.9 1086.65
  4909.8 1085.93  4921.5 1084.54  4941.3 1080.61  4960.3 1079.23    4971 1077.93
    4983 1077.58    4998  1074.2  4999.5  1071.2  5000.5  1071.2    5002  1074.2
  5006.3  1077.5  5013.6  1078.3  5030.1 1078.08  5046.6 1081.19  5061.8  1085.3
  5079.6 1089.61  5095.9  1092.7  5128.5 1097.62  5141.6 1099.29  5156.8 1100.33
#Mann= 4 ,-1 , 0
  4693.3     .14       0  4921.5     .07       0    4998     .05       0
    5002     .07       0
Bank Sta=4998,5002
Exp/Cntr=0.3,0.1

Type RM Length L Ch R = 1 ,102868  ,296,296,296
BEGIN DESCRIPTION:
North Deep Creek 301.0
END DESCRIPTION:
XS GIS Cut Line= 4
      1481192.39       899021.54      1481250.81       898782.56
      1481181.78       898594.06      1481139.31       898493.19
#Sta/Elev= 30
    4623 1088.17  4632.2 1087.21  4647.9 1087.05  4691.3 1085.12  4706.4 1083.35
    4765 1080.89  4830.2  1075.4  4847.1 1074.77  4901.9 1072.61  4912.6  1072.9
  4943.6 1072.27  4962.7 1073.05    4977 1072.74  4993.3 1073.24    4998 1069.91
  4999.5 1066.91  5000.5 1066.91    5002 1069.91  5004.7  1072.3  5006.3 1072.86
  5053.9 1071.69  5065.2 1072.65  5071.9 1073.98  5079.3 1077.99  5089.5 1085.81
  5099.7  1092.6  5113.7 1098.23  5139.4  1103.5    5164 1106.26  5179.2 1107.22
#Mann= 4 ,-1 , 0
    4623     .14       0  4847.1     .07       0    4998     .05       0
    5002     .07       0
Bank Sta=4998,5002
Exp/Cntr=0.3,0.1

Type RM Length L Ch R = 1 ,102572  ,333,333,333
BEGIN DESCRIPTION:
North Deep Creek 300.0
END DESCRIPTION:
XS GIS Cut Line= 4
       1481728.7       899042.74      1481649.05       898790.52
      1481428.69       898482.55       1481410.1       898400.21
#Sta/Elev= 30
  4422.7 1081.13  4429.7 1080.37  4448.2 1080.49  4495.5 1077.94    4553 1076.97
  4586.1 1075.39  4630.7 1074.59  4693.1 1071.69  4736.6 1068.86  4771.8 1068.29
  4814.3 1068.72  4823.5 1068.44  4830.9 1067.18  4835.5 1067.93  4867.5 1067.33
    4938 1068.54    4971 1069.71  4995.2 1068.22    4998 1066.86  4999.5 1063.86
  5000.5 1063.86    5002 1066.86  5011.7 1069.11    5022 1068.84  5057.2 1069.83
  5083.1 1071.88  5107.7 1077.39  5135.1  1084.8  5145.8 1088.69  5150.3 1089.14
#Mann= 3 ,-1 , 0
  4422.7     .07       0    4998     .05       0    5002     .07       0
Bank Sta=4998,5002
Exp/Cntr=0.5,0.3

Type RM Length L Ch R = 1 ,102239  ,61,61,61
BEGIN DESCRIPTION:
Private Dr 3 (NDC) us
END DESCRIPTION:
XS GIS Cut Line= 5
       1481988.9       898692.31      1481784.45       898490.51
      1481755.25       898376.35      1481707.46       898309.98
      1481556.13       898251.57
#Sta/Elev= 30
  4633.7 1077.87  4641.5 1077.42    4682 1075.84  4703.3 1073.66  4744.3 1071.16
    4753 1071.64  4773.1 1071.18  4805.9 1068.83  4876.2 1065.55  4882.6  1066.1
  4915.7 1065.66  4933.2 1066.28  4952.5 1065.99  4983.3 1067.16    4996  1065.7
  4998.5  1061.6  5001.5  1061.6    5004  1065.7  5006.7 1067.88  5019.9 1066.31
  5050.7 1066.11    5106 1066.83  5137.6 1067.63  5169.1 1069.28  5180.4 1070.67
  5195.6 1073.24  5221.7 1076.26  5256.2 1084.44  5281.2 1086.91  5282.8 1087.13
#Mann= 6 ,-1 , 0
  4633.7     .14       0  4641.5     .07       0    4996     .05       0
    5004     .07       0  5180.4     .14       0  5281.2     .07       0
#XS Ineff= 2 , 0
       0    4971 1066.08    5029       0 1066.07
Permanent Ineff=
       F       F
Bank Sta=4996,5004
Exp/Cntr=0.5,0.3

Type RM Length L Ch R = 3 ,102213  ,,,
BEGIN DESCRIPTION:
Private Dr 3 (NDC) tor
Structure ID: LDS_NDC_24
Approximate Survey Structure
END DESCRIPTION:
Bridge Culvert--1,0,-1,-1, 0
Deck Dist Width WeirC Skew NumUp NumDn MinLoCord MaxHiCord MaxSubmerge Is_Ogee
20,12,3,0, 20, 20, , , 0.95, 0, 1,1,,
  4919.4  4981.5  4988.1    4991    4991    5009    5009    5010  5017.6  5037.9
  5065.7  5077.8  5087.2  5108.6  5142.4  5177.2  5213.9  5247.1  5290.2  5339.7
 1065.59 1066.31  1066.6  1066.6  1066.6  1066.6  1066.6  1066.6 1066.13 1065.66
 1065.56 1065.58 1065.85 1066.71  1067.9 1071.44 1074.29 1079.07 1085.85 1090.28
 1041.52 1041.52 1041.52 1041.52  1065.3  1065.3 1041.52 1041.52 1041.52 1041.52
 1041.52 1041.52 1041.52 1041.52 1041.52 1041.52 1041.52 1041.52 1041.52 1041.52
  4919.4  4981.5  4988.1    4991    4991    5009    5009    5010  5017.6  5037.9
  5065.7  5077.8  5087.2  5108.6  5142.4  5177.2  5213.9  5247.1  5290.2  5339.7
 1065.59 1066.31  1066.6  1066.6  1066.6  1066.6  1066.6  1066.6 1066.13 1065.66
 1065.56 1065.58 1065.85 1066.71  1067.9 1071.44 1074.29 1079.07 1085.85 1090.28
 1041.52 1041.52 1041.52 1041.52  1065.3  1065.3 1041.52 1041.52 1041.52 1041.52
 1041.52 1041.52 1041.52 1041.52 1041.52 1041.52 1041.52 1041.52 1041.52 1041.52
Abutment Skew #Up #Dn= , 2 , 2
    4991    4995
  1065.3 1065.78
    4991    4995
  1065.3 1064.64
Abutment Skew #Up #Dn= , 2 , 2
    5005    5009
 1066.51  1065.3
    5005    5009
 1065.45  1065.3
BR Coef= 1 , 1 , 0 ,1.25, 0 ,,,0.8,0,2,0,
WSPro=,,,, 1 ,,,, 0 ,,,, 0 ,,,,-1 ,-1 ,-1 , 0 , 0 , 0 , 0 , 0
BC Design=,, 0 ,, 0 ,,,,,,
BC HTab HWMax=1087.13

Type RM Length L Ch R = 1 ,102178  ,377,377,377
BEGIN DESCRIPTION:
Private Dr 3 (NDC) ds
END DESCRIPTION:
XS GIS Cut Line= 5
      1482060.55       898604.67      1481842.86       898463.97
      1481816.31        898373.7      1481736.66       898280.78
      1481558.75       898209.08
#Sta/Elev= 30
  4669.7 1078.68  4691.3 1077.51  4709.1 1076.18  4716.9    1075  4750.5 1072.48
  4755.2 1071.77  4768.3 1072.37  4811.4 1071.66  4879.1 1068.72  4919.7 1066.09
  4923.2 1065.43  4932.9 1065.05  4943.3  1065.8    4996 1064.54  4998.5 1061.35
  5001.5 1061.35    5004 1065.45  5018.9 1065.86  5081.5 1064.99  5145.3 1067.19
  5180.8 1069.43  5196.1 1071.98  5226.7 1073.91  5243.9 1076.09    5248 1075.95
  5262.2 1077.11    5308 1085.72  5318.1 1085.86  5335.2  1087.1  5337.2 1087.23
#Mann= 6 ,-1 , 0
  4669.7     .14       0  4691.3     .07       0    4996     .05       0
    5004     .07       0  5180.8     .14       0  5335.2     .07       0
#XS Ineff= 2 , 0
       0    4962 1065.57    5038       0  1066.6
Permanent Ineff=
       F       F
Bank Sta=4996,5004
Exp/Cntr=0.5,0.3

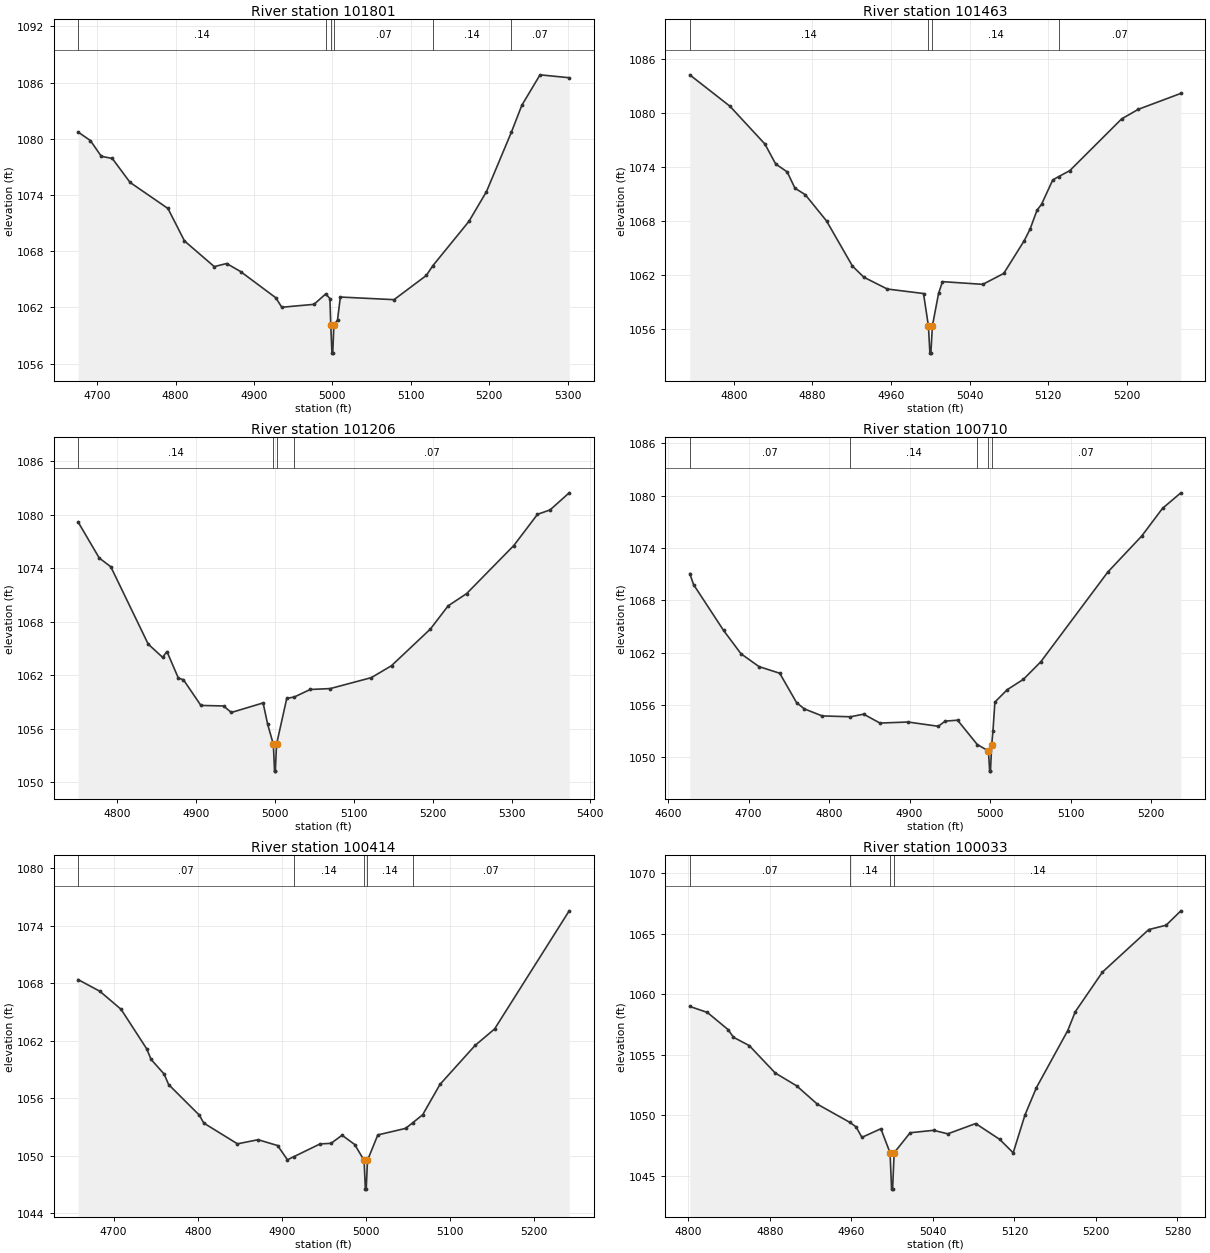
Type RM Length L Ch R = 1 ,101801  ,338,338,338
BEGIN DESCRIPTION:
North Deep Creek 299.0
END DESCRIPTION:
XS GIS Cut Line= 4
      1482341.95       898211.74      1482118.97       898137.41
      1481880.03        898025.9      1481787.13       897938.31
#Sta/Elev= 30
  4675.7 1080.72  4691.4 1079.81  4705.3 1078.13  4719.3  1077.9    4742 1075.34
  4790.3 1072.56  4811.4 1069.09  4849.4 1066.35  4865.2 1066.68    4883 1065.82
  4927.9 1063.02  4935.5 1062.01  4976.6 1062.32  4991.5 1063.43  4996.9 1062.94
    4998 1060.11  4999.5 1057.11  5000.5 1057.11    5002 1060.11  5006.6 1060.65
  5010.2  1063.1  5078.7 1062.82  5119.8  1065.4  5128.3 1066.46  5174.3 1071.19
  5196.6 1074.36  5228.4 1080.71  5241.7 1083.58  5264.9 1086.83  5302.1 1086.52
#Mann= 6 ,-1 , 0
  4675.7     .14       0  4991.5     .07       0    4998     .05       0
    5002     .07       0  5128.3     .14       0  5228.4     .07       0
Bank Sta=4998,5002
Exp/Cntr=0.3,0.1

Type RM Length L Ch R = 1 ,101463  ,257,257,257
BEGIN DESCRIPTION:
North Deep Creek 298.0
END DESCRIPTION:
XS GIS Cut Line= 4
      1482288.87       897744.49      1482140.21       897792.27
      1481986.23       897816.16      1481818.95       897901.13
#Sta/Elev= 30
  4755.2 1084.21    4796 1080.73  4831.6 1076.53  4842.6 1074.31  4854.3 1073.43
  4862.2 1071.62  4872.7  1070.9  4894.3 1067.99  4920.7 1062.97  4932.3 1061.73
  4956.2 1060.42    4993 1059.92    4998  1056.3  4999.5  1053.3  5000.5  1053.3
    5002  1056.3  5008.3 1059.93  5012.3 1061.24  5053.3 1060.94  5074.6 1062.15
  5095.4 1065.78  5101.4 1067.07  5108.4 1069.16  5113.1 1069.84  5124.5 1072.54
  5130.4  1072.9  5141.8 1073.57  5194.5 1079.31  5211.5 1080.38  5254.8 1082.15
#Mann= 4 ,-1 , 0
  4755.2     .14       0    4998     .05       0    5002     .14       0
  5130.4     .07       0
Bank Sta=4998,5002
Exp/Cntr=0.3,0.1

Type RM Length L Ch R = 1 ,101206  ,496,496,496
BEGIN DESCRIPTION:
North Deep Creek 297.0
END DESCRIPTION:
XS GIS Cut Line= 4
      1482288.87       897617.04      1482057.91       897550.67
      1481935.78       897540.05      1481678.28       897505.54
#Sta/Elev= 30
  4750.4 1079.18  4777.2 1075.14  4791.9 1074.15  4839.3 1065.48  4857.5    1064
  4863.1 1064.64  4877.5 1061.67    4884 1061.48  4906.1  1058.6  4934.8 1058.54
  4944.7 1057.81    4985 1058.88  4990.7 1056.51    4998 1054.23  4999.5 1051.23
  5000.5 1051.23    5002 1054.23    5015  1059.4  5024.4 1059.54  5044.7 1060.39
  5070.1 1060.49  5122.3 1061.72  5147.8 1063.06  5197.2 1067.18  5219.6 1069.77
  5243.1 1071.15  5302.9 1076.54  5332.9 1080.04  5348.8 1080.53  5373.1 1082.45
#Mann= 4 ,-1 , 0
  4750.4     .14       0    4998     .05       0    5002     .14       0
  5024.4     .07       0
Bank Sta=4998,5002
Exp/Cntr=0.3,0.1

Type RM Length L Ch R = 1 ,100710  ,296,296,296
BEGIN DESCRIPTION:
North Deep Creek 296.0
END DESCRIPTION:
XS GIS Cut Line= 4
      1482437.57       897311.74      1482339.33       897200.22
      1482166.76       897070.13      1481938.39       896979.85
#Sta/Elev= 30
  4626.8 1071.06  4631.6 1069.78  4668.8 1064.54  4690.5 1061.86  4712.9 1060.39
  4738.6 1059.63  4759.6 1056.25  4769.3 1055.54  4791.3 1054.74  4826.4 1054.64
  4842.9 1054.94  4863.1 1053.92    4898 1054.04  4935.6 1053.55  4944.2 1054.14
  4959.6 1054.25  4984.1 1051.46    4998 1050.72  4999.5 1048.41  5000.5 1048.41
    5002 1051.41  5003.6 1053.01    5006 1056.33  5021.4 1057.75  5041.5 1058.94
    5063 1060.94  5146.4 1071.24  5188.4 1075.35  5214.3 1078.53  5237.1 1080.31
#Mann= 5 ,-1 , 0
  4626.8     .07       0  4826.4     .14       0  4984.1     .07       0
    4998     .05       0    5002     .07       0
Bank Sta=4998,5002
Exp/Cntr=0.3,0.1

Type RM Length L Ch R = 1 ,100414  ,381,381,381
BEGIN DESCRIPTION:
North Deep Creek 295.0
END DESCRIPTION:
XS GIS Cut Line= 4
      1482663.24       897112.61      1482490.66       896963.93
      1482355.26       896868.36      1482177.41       896799.34
#Sta/Elev= 30
  4657.7 1068.39  4683.6 1067.17  4708.9 1065.28  4739.4 1061.15  4744.5 1060.06
  4760.1 1058.52  4765.4 1057.43    4802 1054.23  4807.2 1053.41  4847.3 1051.24
  4871.9 1051.67  4895.1 1051.06  4906.8 1049.57  4914.2 1049.89  4945.6 1051.23
  4958.6 1051.29  4971.8 1052.14  4986.8 1051.17    4998 1049.51  4999.5 1046.51
  5000.5 1046.51    5002 1049.51  5014.3 1052.17  5047.3 1052.85  5055.7 1053.43
  5067.7 1054.28  5088.3 1057.45  5130.1 1061.52  5153.2 1063.23    5242 1075.57
#Mann= 5 ,-1 , 0
  4657.7     .07       0  4914.2     .14       0    4998     .05       0
    5002     .14       0  5055.7     .07       0
Bank Sta=4998,5002
Exp/Cntr=0.3,0.1

Type RM Length L Ch R = 1 ,100033  ,370,370,370
BEGIN DESCRIPTION:
North Deep Creek 294.0
END DESCRIPTION:
XS GIS Cut Line= 4
      1482838.45       896799.33      1482724.29       896711.72
      1482655.27       896589.59      1482634.03       896393.12
#Sta/Elev= 30
  4801.5 1058.99  4818.8 1058.49    4839 1057.08  4844.4 1056.44  4859.9 1055.75
  4885.3 1053.49  4906.3 1052.43  4926.7 1050.91  4958.5 1049.41  4964.6 1049.04
  4970.4 1048.17    4989 1048.88    4998 1046.89  4999.5 1043.89  5000.5 1043.89
    5002 1046.89  5017.7 1048.55  5040.7 1048.75  5054.6 1048.46    5082 1049.31
  5105.6    1048  5118.8 1046.89  5130.4 1050.03  5141.6 1052.28  5172.3 1056.99
  5179.7 1058.55  5206.4 1061.83  5251.8 1065.34  5268.8  1065.7  5283.3 1066.89
#Mann= 4 ,-1 , 0
  4801.5     .07       0  4958.5     .14       0    4998     .05       0
    5002     .14       0
Bank Sta=4998,5002
Exp/Cntr=0.3,0.1

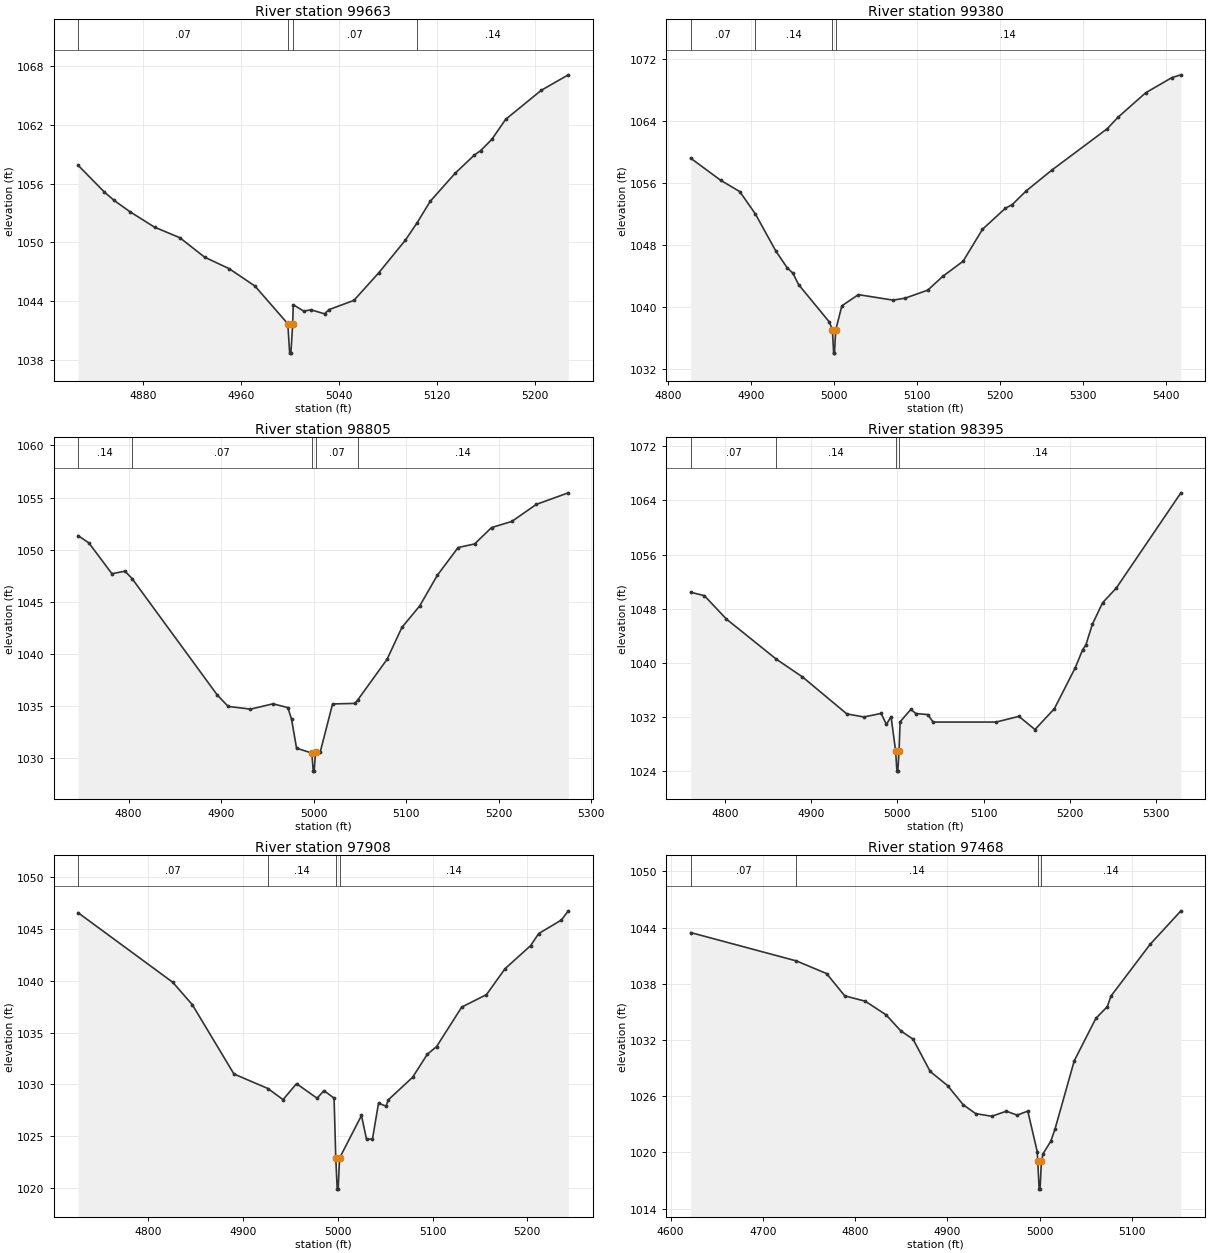
Type RM Length L Ch R = 1 ,99663   ,283,283,283
BEGIN DESCRIPTION:
North Deep Creek 293.0
END DESCRIPTION:
XS GIS Cut Line= 3
      1483064.13       896592.25      1482987.13        896435.6
      1482793.35       896318.81
#Sta/Elev= 30
  4826.5  1057.9    4848 1055.16    4856  1054.3  4868.9 1053.15    4889 1051.57
  4909.7 1050.49    4930  1048.5  4950.1 1047.32  4971.1 1045.55    4998 1041.69
  4999.5 1038.69  5000.5 1038.69    5002 1041.69  5002.4 1043.64  5011.1 1042.98
  5016.9 1043.12    5028 1042.71  5031.7 1043.14    5052 1044.08  5072.4 1046.91
    5094 1050.22  5103.8 1052.04  5114.4 1054.21  5134.8 1057.08  5150.6 1058.95
  5155.6 1059.39  5164.7 1060.53  5176.1 1062.59  5205.1 1065.55  5227.3 1067.14
#Mann= 4 ,-1 , 0
  4826.5     .07       0    4998     .05       0    5002     .07       0
  5103.8     .14       0
Bank Sta=4998,5002
Exp/Cntr=0.3,0.1

Type RM Length L Ch R = 1 ,99380   ,575,575,575
BEGIN DESCRIPTION:
North Deep Creek 292.0
END DESCRIPTION:
XS GIS Cut Line= 4
      1483380.03       896353.29      1483165.01       896255.07
       1483053.5       896225.87      1482814.59        896217.9
#Sta/Elev= 30
  4827.2 1059.17  4863.6  1056.3  4886.4 1054.86  4905.1 1051.99    4930 1047.17
  4943.4 1045.06  4950.5 1044.33  4957.2 1042.88  4994.4 1038.04    4998 1037.04
  4999.5 1034.04  5000.5 1034.04    5002 1037.04  5009.4 1040.14  5029.3 1041.58
  5071.1 1040.87  5085.8 1041.13  5112.9 1042.16  5130.9 1043.93  5155.5 1045.89
  5178.8    1050  5206.5 1052.72  5214.5 1053.17  5231.5 1054.95  5262.5 1057.64
  5329.1 1062.96  5342.3 1064.46  5375.5  1067.6    5407 1069.55  5417.9 1069.91
#Mann= 4 ,-1 , 0
  4827.2     .07       0  4905.1     .14       0    4998     .05       0
    5002     .14       0
Bank Sta=4998,5002
Exp/Cntr=0.3,0.1

Type RM Length L Ch R = 1 ,98805   ,410,410,410
BEGIN DESCRIPTION:
North Deep Creek 291.0
END DESCRIPTION:
XS GIS Cut Line= 4
      1483571.21       895819.66      1483425.19       895747.98
      1483297.76       895721.43      1483061.43        895705.5
#Sta/Elev= 30
  4745.4 1051.35  4757.1 1050.65    4782  1047.7  4796.1 1047.94  4803.8 1047.23
  4895.8 1036.08  4907.6 1034.98  4931.7 1034.72    4956 1035.23  4972.1 1034.87
  4976.1 1033.74  4981.5 1030.98    4998 1030.51  4999.5 1028.78  5000.5 1028.78
    5002  1030.6    5007 1030.59  5020.4 1035.22  5044.5 1035.27  5047.5 1035.59
  5079.3  1039.5  5095.3 1042.55  5114.6 1044.62  5133.6 1047.55  5156.1 1050.21
  5173.8 1050.55  5192.2 1052.12  5214.1 1052.71  5240.5 1054.34  5275.1 1055.45
#Mann= 5 ,-1 , 0
  4745.4     .14       0  4803.8     .07       0    4998     .05       0
    5002     .07       0  5047.5     .14       0
Bank Sta=4998,5002
Exp/Cntr=0.3,0.1

Type RM Length L Ch R = 1 ,98395   ,487,487,487
BEGIN DESCRIPTION:
North Deep Creek 290.0
END DESCRIPTION:
XS GIS Cut Line= 4
      1483746.43       895615.23      1483632.28       895501.07
      1483518.12       895283.37      1483406.58       895166.52
#Sta/Elev= 30
  4760.2 1050.44  4776.1 1049.93  4801.7 1046.48  4859.7 1040.55  4889.9 1037.95
  4941.4 1032.49  4961.1 1032.04  4981.2 1032.56  4987.3 1030.94  4992.7 1032.09
    4998 1027.05  4999.5 1024.05  5000.5 1024.05    5002 1027.05  5003.2 1031.33
  5015.7 1033.16  5021.4 1032.55  5035.4 1032.39  5041.4 1031.29  5114.7 1031.29
    5141 1032.13  5159.7 1030.19  5182.2 1033.26  5206.5 1039.32  5214.9 1041.93
  5218.7 1042.65  5226.3 1045.72  5238.1 1048.88    5254 1051.05    5329  1065.1
#Mann= 4 ,-1 , 0
  4760.2     .07       0  4859.7     .14       0    4998     .05       0
    5002     .14       0
Bank Sta=4998,5002
Exp/Cntr=0.3,0.1

Type RM Length L Ch R = 1 ,97908   ,440,440,440
BEGIN DESCRIPTION:
North Deep Creek 289.0
END DESCRIPTION:
XS GIS Cut Line= 4
      1484083.61       895530.31      1484080.96       895363.02
      1484033.17       895209.03      1484033.17       895020.58
#Sta/Elev= 30
  4726.2 1046.56  4826.1 1039.85  4846.8 1037.68  4890.6 1031.01  4926.4 1029.61
  4942.4 1028.54  4956.6 1030.08  4978.3 1028.67  4985.5 1029.41  4996.2 1028.68
    4998 1022.91  4999.5 1019.91  5000.5 1019.91    5002 1022.91  5025.1 1027.01
  5030.4 1024.72  5036.7 1024.75  5043.1 1028.21    5051  1027.9  5053.4 1028.52
    5079 1030.69  5094.5 1032.91  5104.3 1033.65  5130.8 1037.46  5156.9 1038.66
  5176.5 1041.16  5203.4 1043.38    5212 1044.55  5235.9 1045.85  5243.2 1046.74
#Mann= 4 ,-1 , 0
  4726.2     .07       0  4926.4     .14       0    4998     .05       0
    5002     .14       0
Bank Sta=4998,5002
Exp/Cntr=0.3,0.1

Type RM Length L Ch R = 1 ,97468   ,138,138,138
BEGIN DESCRIPTION:
North Deep Creek 288.0
END DESCRIPTION:
XS GIS Cut Line= 4
      1484232.32       895511.65      1484388.93       895304.61
      1484444.68       895203.72      1484444.68       895047.09
#Sta/Elev= 30
  4621.7 1043.46  4736.4 1040.43  4769.1 1039.08  4788.8  1036.7    4811 1036.13
  4833.5 1034.68  4849.6 1032.96  4862.8 1032.08  4881.4 1028.63  4900.2 1027.13
  4917.2 1025.08  4930.7 1024.13  4948.1 1023.85    4964 1024.39  4975.6 1023.97
  4987.2  1024.4  4997.5 1020.05    4998 1019.07  4999.5 1016.07  5000.5 1016.07
    5002 1019.07  5003.8 1019.86  5012.1 1021.18  5016.8 1022.51  5037.6 1029.78
    5061  1034.3  5073.4 1035.55  5077.4 1036.68  5119.8  1042.2  5153.2 1045.78
#Mann= 4 ,-1 , 0
  4621.7     .07       0  4736.4     .14       0    4998     .05       0
    5002     .14       0
Bank Sta=4998,5002
Exp/Cntr=0.3,0.1