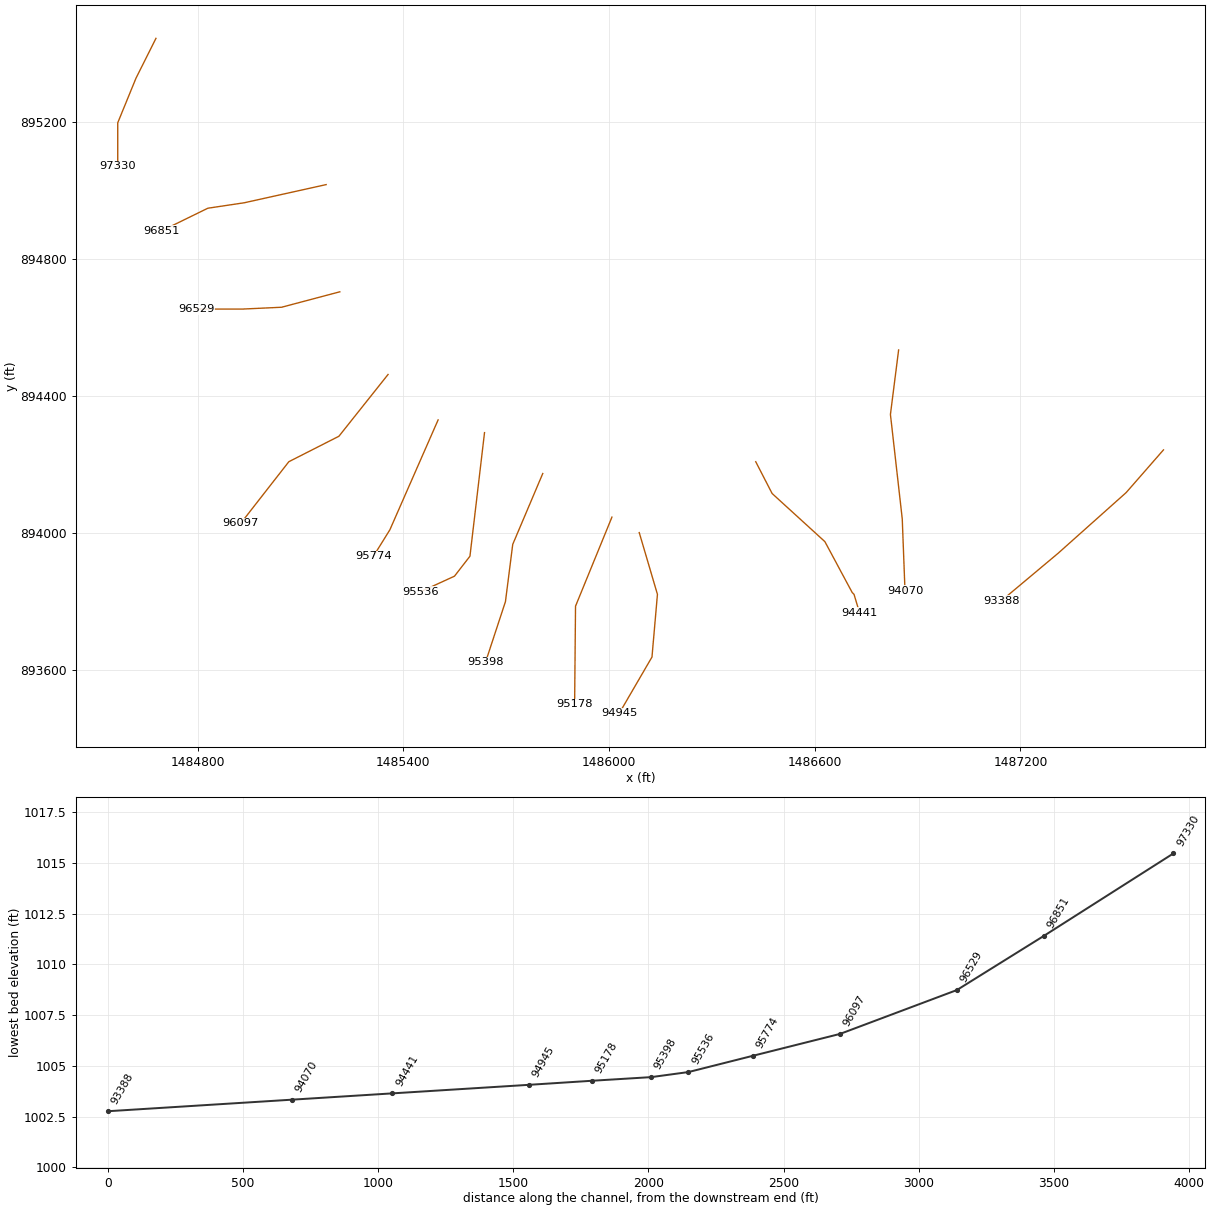
HEC-RAS study North Deep Creek.prj: North Deep Creek Limited Detail Study

--- North Deep Creek.g01 (geometry) --- (continued)

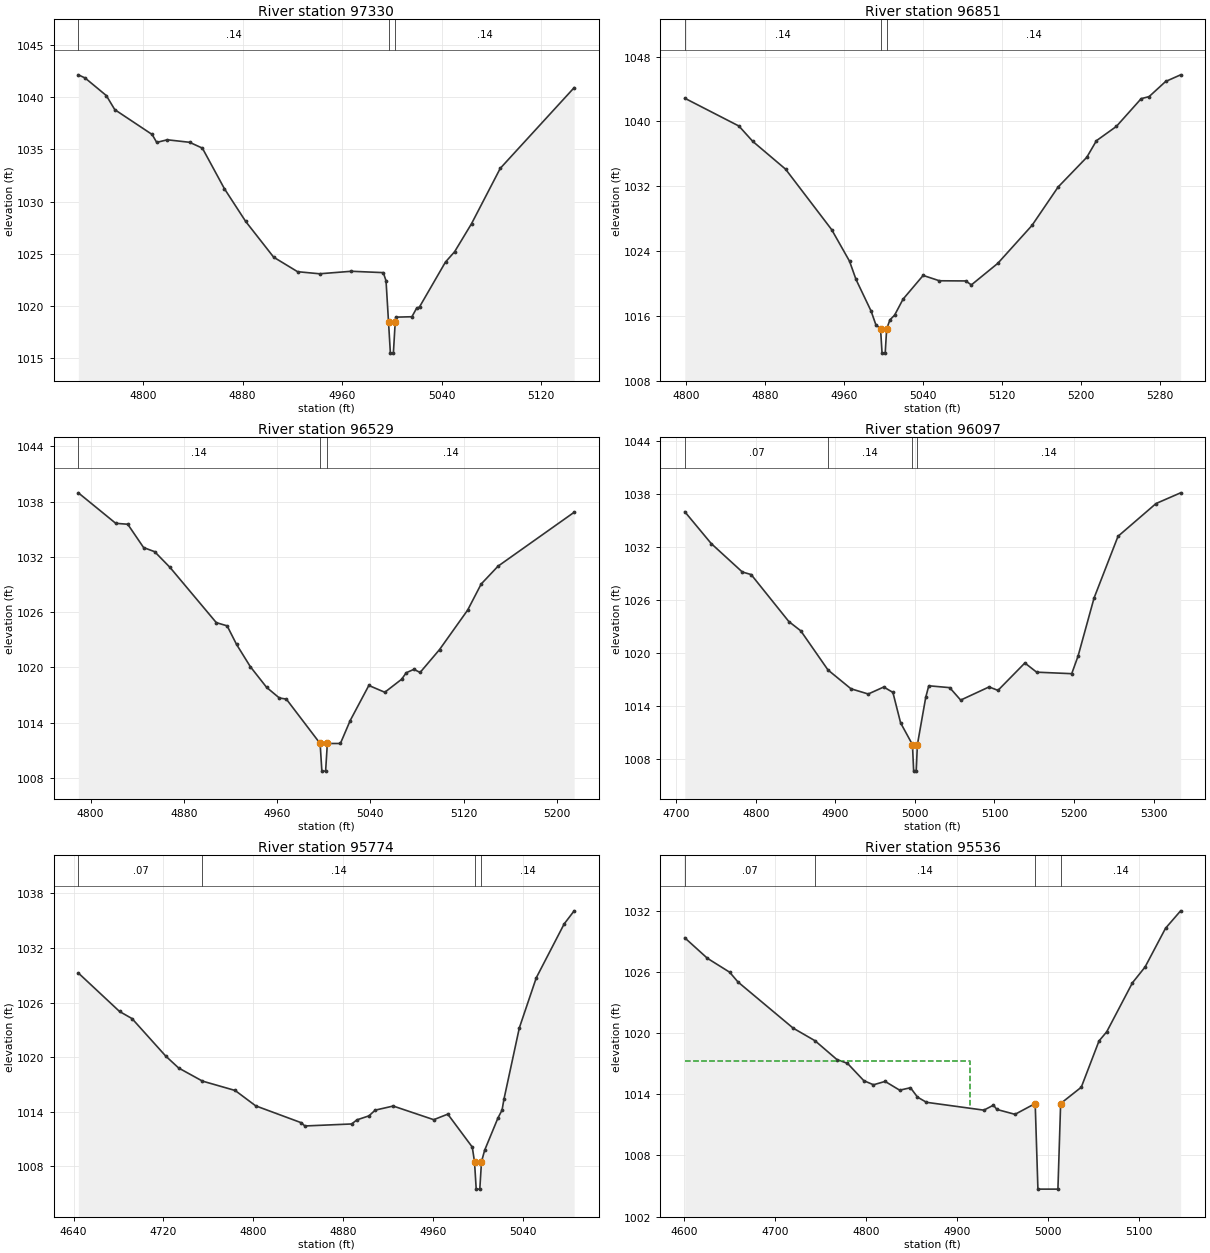
Type RM Length L Ch R = 1 ,97330   ,479,479,479
BEGIN DESCRIPTION:
North Deep Creek 287.0
END DESCRIPTION:
XS GIS Cut Line= 4
      1484678.31        895445.3      1484619.91        895328.5
      1484566.81       895198.41      1484566.81       895071.01
#Sta/Elev= 30
    4748 1042.16  4753.4 1041.86  4770.5 1040.17  4777.3 1038.82  4807.3 1036.44
    4811 1035.68  4819.5 1035.93  4837.4 1035.69  4847.7 1035.13  4865.4 1031.24
  4882.5  1028.1    4905 1024.67  4924.2 1023.28  4941.9 1023.08  4967.4 1023.32
  4993.1 1023.19  4995.3 1022.41  4997.3 1018.47  4998.8 1015.47  5001.2 1015.47
  5002.7 1018.47  5003.1 1018.92  5016.1 1018.96  5019.8 1019.76  5022.2  1019.9
  5043.1 1024.21  5050.4 1025.19    5064 1027.88  5087.1 1033.19  5146.5 1040.93
#Mann= 3 ,-1 , 0
    4748     .14       0  4997.3     .05       0  5002.7     .14       0
Bank Sta=4997.3,5002.7
Exp/Cntr=0.3,0.1

Type RM Length L Ch R = 1 ,96851   ,322,322,322
BEGIN DESCRIPTION:
North Deep Creek 286.0
END DESCRIPTION:
XS GIS Cut Line= 4
      1485174.81       895017.88      1484935.84       894964.78
      1484829.65       894948.85      1484694.22       894882.46
#Sta/Elev= 30
  4798.3 1042.87  4853.2 1039.44  4867.3 1037.54  4900.5 1034.12  4947.3 1026.65
  4965.4 1022.76    4972  1020.5  4987.3  1016.6  4992.1 1014.92  4996.9 1014.41
  4998.4 1011.41  5001.6 1011.41  5003.1 1014.41  5006.4 1015.52  5011.1 1016.09
  5019.7 1018.07  5040.1    1021  5056.6 1020.34  5083.3 1020.32    5089 1019.83
  5115.8 1022.49  5150.5 1027.17    5177 1031.91  5206.1 1035.58  5215.9 1037.63
  5236.1 1039.39  5261.3 1042.82  5269.3 1043.07  5286.1 1044.94  5301.3 1045.76
#Mann= 3 ,-1 , 0
  4798.3     .14       0  4996.9     .05       0  5003.1     .14       0
Bank Sta=4996.9,5003.1
Exp/Cntr=0.3,0.1

Type RM Length L Ch R = 1 ,96529   ,432,432,432
BEGIN DESCRIPTION:
North Deep Creek 285.0
END DESCRIPTION:
XS GIS Cut Line= 4
      1485214.65       894704.61       1485044.7       894659.46
      1484930.53       894654.15      1484795.17       894654.15
#Sta/Elev= 30
  4789.4 1038.95  4821.5 1035.64  4831.8 1035.54  4845.4 1033.01  4854.9 1032.56
  4868.1 1030.85  4907.8 1024.86  4917.1 1024.51  4925.2 1022.49    4937 1020.08
    4951 1017.83  4961.9 1016.68  4967.9 1016.56  4996.9 1011.74  4998.4 1008.74
  5001.6 1008.74  5003.1 1011.74  5014.3 1011.74  5022.7 1014.23  5038.7 1018.04
  5052.4  1017.3  5066.8 1018.71  5070.8 1019.42  5077.4 1019.79  5082.7 1019.45
  5099.4 1021.94  5123.5 1026.22  5135.1 1029.05  5149.6 1030.99  5214.9 1036.84
#Mann= 3 ,-1 , 0
  4789.4     .14       0  4996.9     .05       0  5003.1     .14       0
Bank Sta=4996.9,5003.1
Exp/Cntr=0.3,0.1

Type RM Length L Ch R = 1 ,96097   ,323,323,323
BEGIN DESCRIPTION:
North Deep Creek 284.0
END DESCRIPTION:
XS GIS Cut Line= 4
      1485355.35       894463.03      1485211.96       894282.46
      1485065.94       894208.12      1484925.24       894027.61
#Sta/Elev= 30
  4710.7 1035.94  4743.9 1032.34    4783 1029.12  4794.1 1028.83  4841.5 1023.51
  4856.5 1022.46  4890.7 1018.03  4919.6  1015.9  4941.3 1015.31  4960.8  1016.1
  4972.3 1015.49    4982 1012.04  4996.9 1009.58  4998.4 1006.58  5001.6 1006.58
  5003.1 1009.58  5013.6 1014.94  5017.4 1016.24  5043.7 1016.03  5057.5 1014.62
  5093.2 1016.11  5104.4 1015.72  5138.2 1018.82    5153 1017.78  5197.1 1017.61
  5205.1 1019.61  5225.2 1026.18  5255.3 1033.16  5303.1 1036.87    5334 1038.08
#Mann= 4 ,-1 , 0
  4710.7     .07       0  4890.7     .14       0  4996.9     .05       0
  5003.1     .14       0
Bank Sta=4996.9,5003.1
Exp/Cntr=0.3,0.1

Type RM Length L Ch R = 1 ,95774   ,238,238,238
BEGIN DESCRIPTION:
North Deep Creek 283.0
END DESCRIPTION:
XS GIS Cut Line= 3
      1485501.36       894330.28      1485360.63       894009.01
      1485312.82       893931.98
#Sta/Elev= 30
  4644.2 1029.25  4680.9 1025.02    4692 1024.24    4722 1020.12  4733.5 1018.81
  4754.7 1017.37  4783.8 1016.34  4802.1 1014.65  4842.8 1012.79  4845.8 1012.44
  4887.5 1012.66  4892.2 1013.11  4902.9 1013.55  4908.5 1014.18  4924.5 1014.63
  4960.6 1013.13  4973.1 1013.74  4994.9 1010.12  4996.9  1008.5  4998.4  1005.5
  5001.6  1005.5  5003.1  1008.5  5005.9 1009.77  5017.8 1013.33  5021.4 1014.18
  5023.1 1015.38  5036.8 1023.22  5051.9 1028.73  5076.7 1034.64  5085.6 1036.08
#Mann= 4 ,-1 , 0
  4644.2     .07       0  4754.7     .14       0  4996.9     .05       0
  5003.1     .14       0
Bank Sta=4996.9,5003.1
Exp/Cntr=0.5,0.3

Type RM Length L Ch R = 1 ,95536   ,138,138,138
BEGIN DESCRIPTION:
Spencer Rd (NDC) us
END DESCRIPTION:
XS GIS Cut Line= 4
      1485636.75       894293.09      1485594.27       893932.01
      1485549.13        893873.6      1485450.89       893828.47
#Sta/Elev= 30
  4600.5 1029.36  4625.4 1027.35  4649.8 1025.99  4659.1 1025.02  4719.7  1020.5
  4743.8 1019.26  4767.8 1017.42  4779.5 1017.04  4797.5 1015.34  4808.1 1014.94
  4820.9 1015.27  4836.9 1014.41  4848.8 1014.65  4856.5 1013.73  4866.4 1013.22
  4929.5 1012.45  4940.1 1012.94  4943.8 1012.52  4963.8 1012.04    4986  1013.1
    4989  1004.7    5011  1004.7    5014  1013.1  5036.7  1014.7  5056.2 1019.24
  5064.7 1020.14    5093 1024.95  5106.9  1026.5  5129.4  1030.3    5146 1032.01
#Mann= 4 ,-1 , 0
  4600.5     .07       0  4743.8     .14       0    4986     .05       0
    5014     .14       0
#XS Ineff= 2 , 0
       0    4914 1017.26    5086       0 1019.23
Permanent Ineff=
       F       F
Bank Sta=4986,5014
Exp/Cntr=0.5,0.3

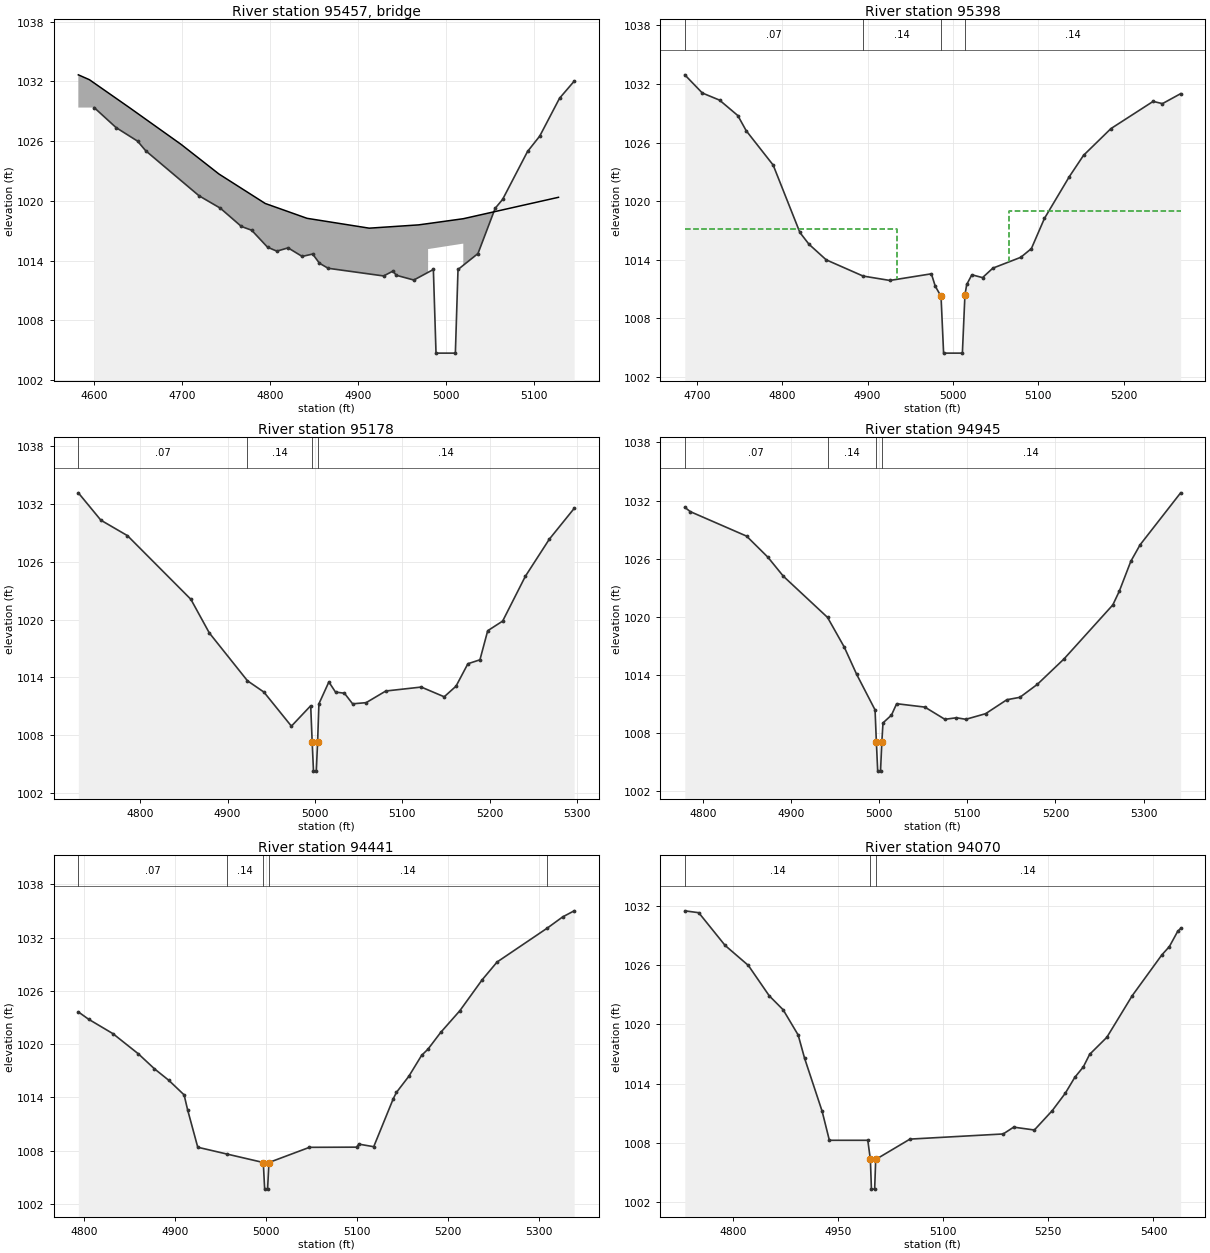
Type RM Length L Ch R = 3 ,95457   ,,,
BEGIN DESCRIPTION:
Spencer Rd (NDC) tor
Structure ID: LDS_NDC_22
Approximate Survey Structure
END DESCRIPTION:
Bridge Culvert--1,0,-1,-1, 0
Deck Dist Width WeirC Skew NumUp NumDn MinLoCord MaxHiCord MaxSubmerge Is_Ogee
66,26,3,0, 14, 14, , , 0.95, 0, 1,1,,
  4582.5  4595.1  4640.7  4699.2  4742.3  4794.9  4842.4  4913.1  4969.1    4980
    4980    5020    5020  5128.2
 1032.65 1032.16 1029.35 1025.67 1022.69 1019.73 1018.24 1017.25 1017.58 1017.71
 1017.71  1018.2  1018.2 1020.35
   984.7   984.7   984.7   984.7   984.7   984.7   984.7   984.7   984.7   984.7
 1015.15  1015.7   984.7   984.7
  4582.5  4595.1  4640.7  4699.2  4742.3  4794.9  4842.4  4913.1  4969.1    4980
    4980    5020    5020  5128.2
 1032.65 1032.16 1029.35 1025.67 1022.69 1019.73 1018.24 1017.25 1017.58 1017.71
 1017.71  1018.2  1018.2 1020.35
   984.7   984.7   984.7   984.7   984.7   984.7   984.7   984.7   984.7   984.7
 1015.15  1015.7   984.7   984.7
Abutment Skew #Up #Dn= , 2 , 2
    4980    4988
 1015.15  1007.5
    4980    4988
 1015.15 1007.25
Abutment Skew #Up #Dn= , 2 , 2
    5012    5020
  1007.5  1015.7
    5012    5020
 1007.25  1015.7
BR Coef= 1 , 1 , 0 ,1.25, 0 ,,,0.8,0,2,0,
WSPro=,,,, 1 ,,,, 0 ,,,, 0 ,,,,-1 ,-1 ,-1 , 0 , 0 , 0 , 0 , 0
BC Design=,, 0 ,, 0 ,,,,,,
BC HTab HWMax=1032.01

Type RM Length L Ch R = 1 ,95398   ,220,220,220
BEGIN DESCRIPTION:
Spencer Rd (NDC) ds
END DESCRIPTION:
XS GIS Cut Line= 4
      1485806.66       894173.62      1485719.05       893966.53
      1485697.81       893799.27       1485639.4       893621.38
#Sta/Elev= 30
  4685.9 1032.94  4706.4 1031.08  4726.6 1030.35    4748 1028.77  4757.8 1027.22
  4789.4  1023.7  4820.7  1016.8  4831.3  1015.6  4851.5    1014  4894.7 1012.34
  4926.1 1011.89  4974.7 1012.57  4979.2 1011.31    4986 1010.26    4989 1004.45
    5011 1004.45    5014 1010.42  5016.1 1011.48  5022.1 1012.47  5034.6 1012.18
  5046.7 1013.15  5079.4 1014.26  5091.8 1015.15  5107.1 1018.24  5136.2 1022.51
  5152.9  1024.7  5184.9 1027.43  5234.4 1030.22  5245.3 1029.99  5266.6 1031.01
#Mann= 4 ,-1 , 0
  4685.9     .07       0  4894.7     .14       0    4986     .05       0
    5014     .14       0
#XS Ineff= 2 , 0
       0    4934 1017.16    5066       0 1019.04
Permanent Ineff=
       F       F
Bank Sta=4986,5014
Exp/Cntr=0.5,0.3

Type RM Length L Ch R = 1 ,95178   ,233,233,233
BEGIN DESCRIPTION:
North Deep Creek 282.0
END DESCRIPTION:
XS GIS Cut Line= 3
      1486008.45       894046.21      1485902.24       893785.99
      1485899.58       893499.26
#Sta/Elev= 30
  4729.1 1033.17  4754.9 1030.33  4785.4 1028.72    4858 1022.11  4879.1 1018.62
  4922.8 1013.65  4941.6 1012.48  4973.1 1008.94  4995.2 1011.06  4996.9 1007.27
  4998.4 1004.27  5001.6 1004.27  5003.1 1007.27  5004.6 1011.26    5016 1013.53
  5023.6 1012.48  5033.8 1012.36  5043.2 1011.26  5058.7 1011.38  5081.2 1012.59
  5121.8    1013  5148.1 1011.99  5161.6 1013.09  5175.2 1015.42    5189 1015.83
  5197.9 1018.85    5215 1019.85    5241  1024.5  5268.4 1028.35  5296.9 1031.55
#Mann= 4 ,-1 , 0
  4729.1     .07       0  4922.8     .14       0  4996.9     .05       0
  5003.1     .14       0
Bank Sta=4996.9,5003.1
Exp/Cntr=0.3,0.1

Type RM Length L Ch R = 1 ,94945   ,504,504,504
BEGIN DESCRIPTION:
North Deep Creek 281.0
END DESCRIPTION:
XS GIS Cut Line= 4
      1486088.09         894001.      1486141.18       893820.51
      1486125.25       893637.32      1486029.65       893472.68
#Sta/Elev= 30
  4779.6 1031.31  4785.8 1030.86  4849.7 1028.33  4873.7 1026.17  4891.4 1024.19
  4941.5 1019.94  4960.5 1016.87  4974.6 1014.05  4995.4 1010.39  4996.9 1007.07
  4998.4 1004.07  5001.6 1004.07  5003.1 1007.07  5004.4 1009.05    5014 1009.85
  5019.9 1011.03  5051.9 1010.68  5074.6 1009.42  5087.7 1009.58  5098.4 1009.42
  5120.8    1010  5144.9 1011.44  5159.7 1011.69  5179.5 1013.03  5209.7 1015.65
  5265.1 1021.23  5272.5 1022.66  5285.5 1025.73    5296 1027.43    5342  1032.8
#Mann= 4 ,-1 , 0
  4779.6     .07       0  4941.5     .14       0  4996.9     .05       0
  5003.1     .14       0
Bank Sta=4996.9,5003.1
Exp/Cntr=0.3,0.1

Type RM Length L Ch R = 1 ,94441   ,371,371,371
BEGIN DESCRIPTION:
North Deep Creek 280.0
END DESCRIPTION:
XS GIS Cut Line= 6
      1486427.92        894208.1       1486475.7        894115.2
      1486629.68       893974.49      1486709.33       893825.82
      1486714.64       893820.51      1486730.58       893767.38
#Sta/Elev= 30
  4793.7 1023.62  4804.9  1022.8  4831.7 1021.17  4859.7 1018.89  4877.3 1017.21
  4893.1 1015.91  4909.9 1014.27  4913.7 1012.61  4924.9 1008.37  4957.5 1007.59
  4996.9 1006.65  4998.4 1003.65  5001.6 1003.65  5003.1 1006.65  5047.6 1008.36
  5099.3 1008.38  5101.9 1008.72  5118.2 1008.43  5139.7 1013.84  5143.1 1014.54
  5156.8 1016.37  5170.8 1018.72  5177.8 1019.42  5191.7  1021.3  5212.8 1023.75
  5237.2 1027.22  5253.7 1029.24  5309.1 1033.08  5325.7 1034.32  5338.4 1035.01
#Mann= 5 ,-1 , 0
  4793.7     .07       0  4957.5     .14       0  4996.9     .05       0
  5003.1     .14       0  5309.1     .07       0
Bank Sta=4996.9,5003.1
Exp/Cntr=0.3,0.1

Type RM Length L Ch R = 1 ,94070   ,682,682,682
BEGIN DESCRIPTION:
North Deep Creek 279.0
END DESCRIPTION:
XS GIS Cut Line= 4
      1486844.73       894534.69      1486820.84       894346.18
      1486855.35       894040.86      1486863.32       893831.09
#Sta/Elev= 30
  4731.5 1031.49  4751.4  1031.3    4789 1027.99  4822.1 1025.97    4852 1022.89
  4871.8 1021.48  4893.2 1018.93  4902.3 1016.59  4927.4 1011.21  4937.7 1008.28
  4992.5 1008.28  4996.2 1006.34  4997.7 1003.34  5002.3 1003.34  5003.8 1006.34
  5052.7  1008.4  5185.6 1008.92  5200.6 1009.61  5230.1 1009.32  5255.6 1011.28
  5274.2 1013.04  5287.7 1014.64  5299.9  1015.7  5308.9 1016.97  5333.5  1018.7
  5369.6  1022.9  5411.9 1027.03  5422.7 1027.88  5434.4  1029.4  5438.7 1029.71
#Mann= 3 ,-1 , 0
  4731.5     .14       0  4996.2     .05       0  5003.8     .14       0
Bank Sta=4996.2,5003.8
Exp/Cntr=0.3,0.1

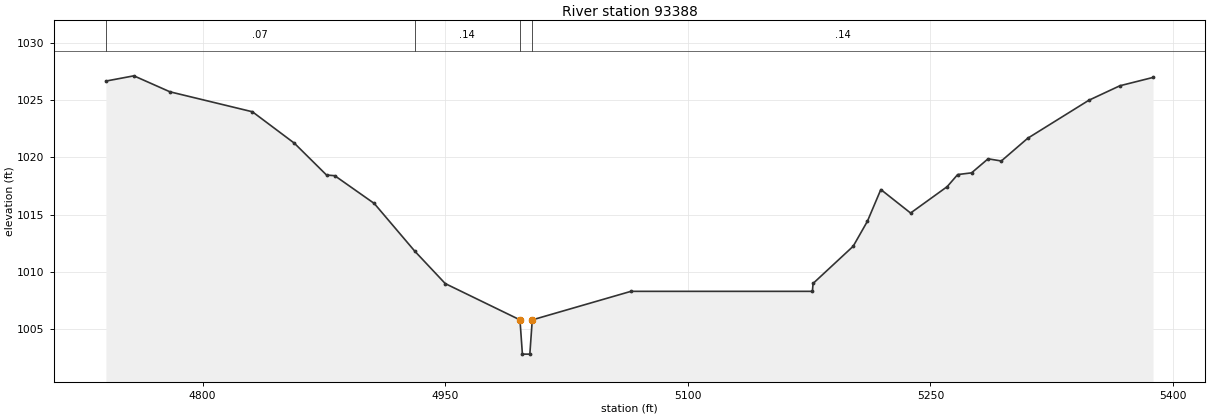
Type RM Length L Ch R = 1 ,93388   ,384,384,384
BEGIN DESCRIPTION:
North Deep Creek 278.0
END DESCRIPTION:
XS GIS Cut Line= 4
      1487617.33       894242.65      1487508.46       894117.86
      1487309.34       893939.98      1487144.77       893801.95
#Sta/Elev= 30
  4740.2 1026.69  4757.5 1027.15  4779.8 1025.75  4830.8    1024  4856.7 1021.25
  4876.6 1018.46  4881.7  1018.4  4906.1 1015.97  4931.1  1011.8    4950 1008.95
  4996.2 1005.77  4997.7 1002.77  5002.3 1002.77  5003.8 1005.77  5064.8 1008.27
    5177 1008.27  5177.4 1008.96  5202.2 1012.22    5211 1014.41  5219.3 1017.19
  5237.7 1015.13  5260.3 1017.44  5266.8  1018.5  5275.4 1018.65  5285.6 1019.88
  5293.8 1019.69  5310.1 1021.68  5347.9 1025.01  5367.1 1026.28  5387.6 1027.01
#Mann= 4 ,-1 , 0
  4740.2     .07       0  4931.1     .14       0  4996.2     .05       0
  5003.8     .14       0
Bank Sta=4996.2,5003.8
Exp/Cntr=0.3,0.1