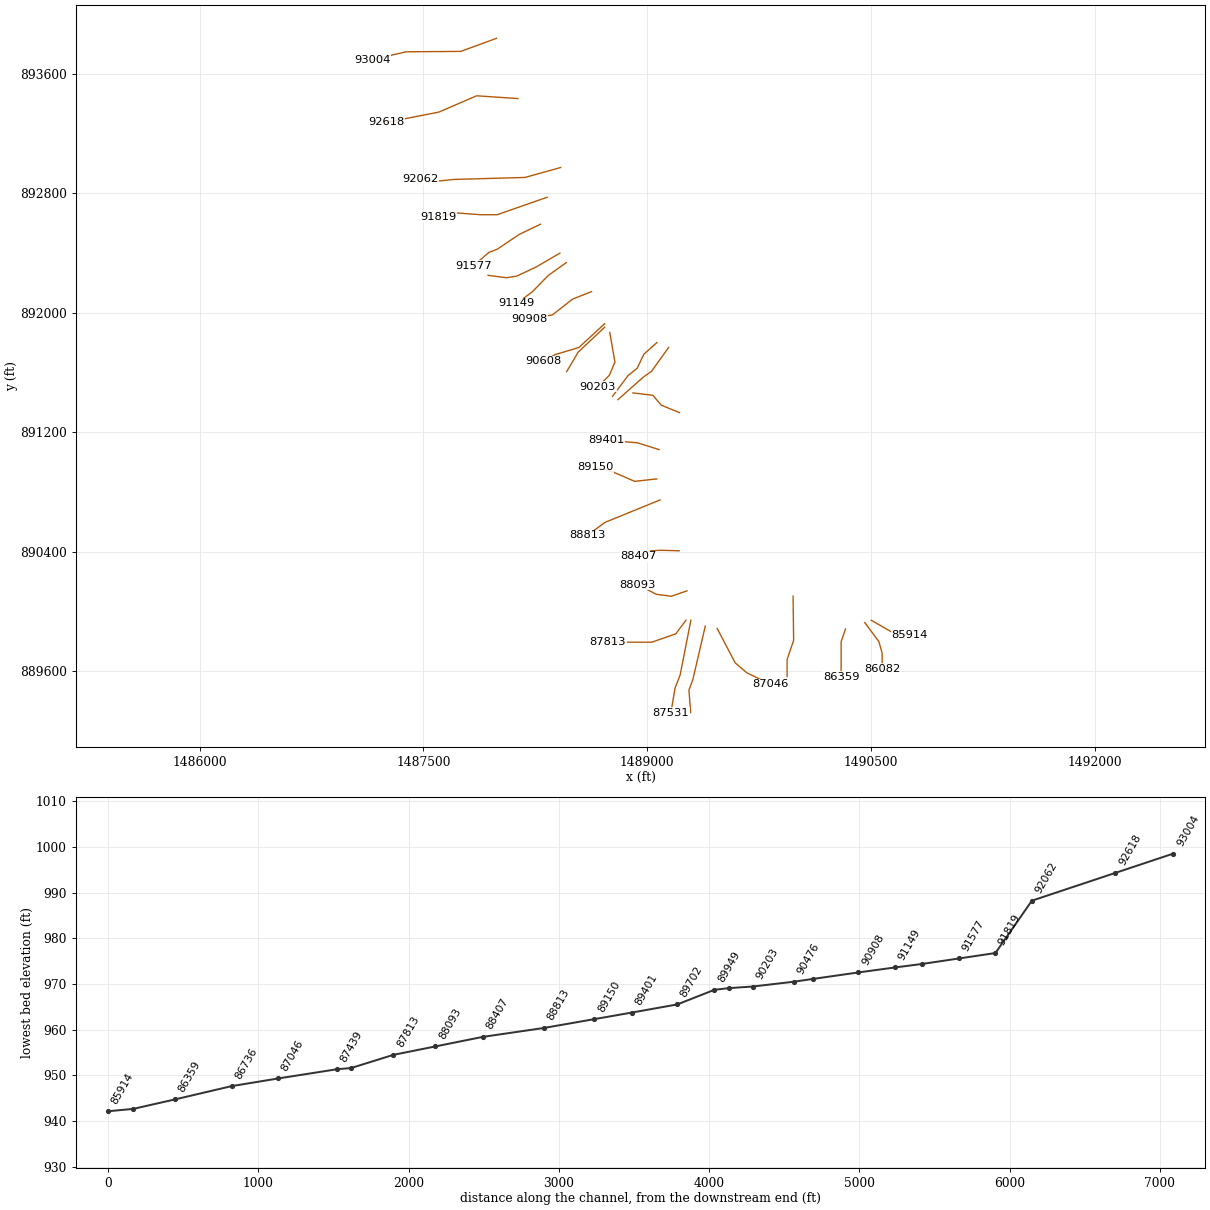
HEC-RAS study North Deep Creek.prj: North Deep Creek Limited Detail Study

--- North Deep Creek.g01 (geometry) --- (continued)

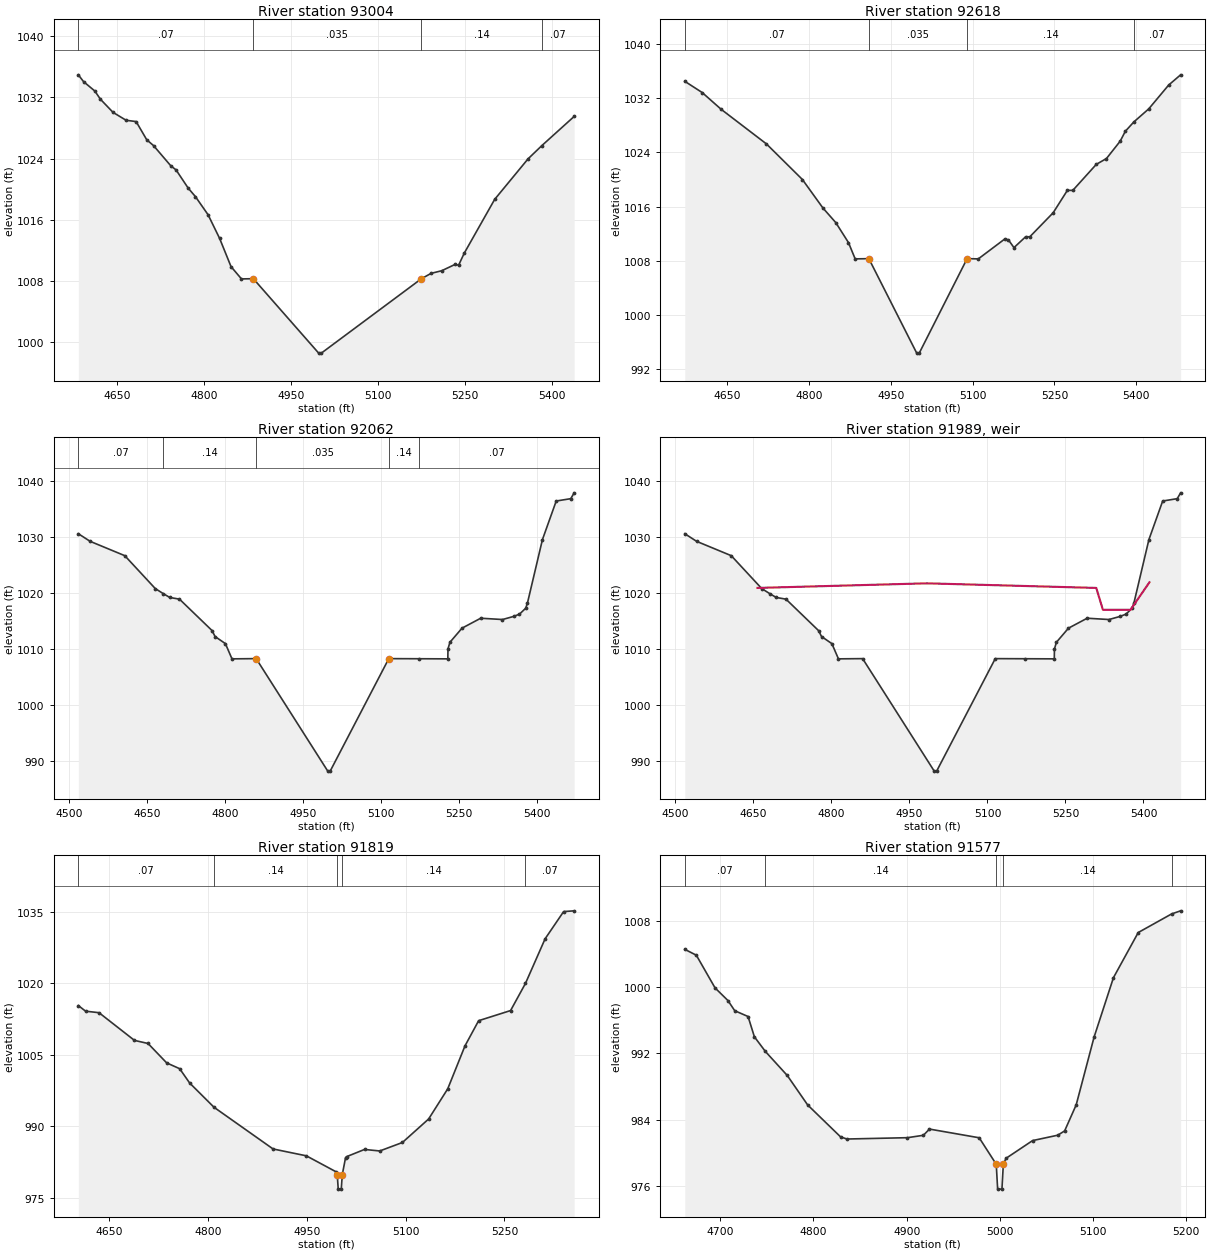
Type RM Length L Ch R = 1 ,93004   ,386,386,386
BEGIN DESCRIPTION:
North Deep Creek 277.0
END DESCRIPTION:
XS GIS Cut Line= 4
      1487988.99       893839.08      1487750.06       893751.48
      1487383.68       893748.82      1487155.35       893695.72
#Sta/Elev= 30
  4583.1 1034.95  4592.1 1034.06  4611.6 1032.83  4621.2 1031.76    4643 1030.04
  4665.5 1029.01  4682.8 1028.84  4701.1 1026.46  4712.8  1025.7  4742.7 1023.05
  4751.7 1022.52  4772.6 1020.14  4785.2 1019.02  4806.9 1016.66  4826.8 1013.57
  4846.5 1009.88  4864.5 1008.27    4885  1008.3  4997.7  998.57  5002.3  998.57
    5175  1008.3  5191.7    1009  5209.9 1009.34  5232.8 1010.16  5239.1 1010.07
  5248.9 1011.65  5301.3 1018.67  5358.8 1023.96  5382.7  1025.7  5438.4 1029.51
#Mann= 4 ,-1 , 0
  4583.1     .07       0    4885    .035       0    5175     .14       0
  5382.7     .07       0
Bank Sta=4885,5175
Exp/Cntr=0.3,0.1

Type RM Length L Ch R = 1 ,92618   ,556,556,556
BEGIN DESCRIPTION:
North Deep Creek 276.0
END DESCRIPTION:
XS GIS Cut Line= 4
      1488132.32       893435.55      1487856.26       893454.13
      1487604.04       893345.27      1487253.57       893276.24
#Sta/Elev= 30
  4572.7 1034.51  4604.6 1032.85  4639.4 1030.37  4722.3 1025.26  4788.2    1020
  4825.8 1015.79  4849.4 1013.63  4872.6 1010.68  4884.9 1008.27    4910  1008.3
  4997.7  994.34  5002.3  994.34    5090  1008.3  5110.6 1008.27  5159.4 1011.23
  5165.8 1011.07  5175.9 1009.93  5197.3 1011.54  5204.9 1011.53  5247.8 1015.09
  5273.8  1018.4  5283.7 1018.39  5326.8 1022.24  5345.4  1023.1  5370.6 1025.67
    5380 1027.13  5395.6 1028.51  5422.9 1030.44  5459.4 1033.96  5481.3 1035.47
#Mann= 4 ,-1 , 0
  4572.7     .07       0    4910    .035       0    5090     .14       0
  5395.6     .07       0
Bank Sta=4910,5090
Exp/Cntr=0.5,0.3

Type RM Length L Ch R = 1 ,92062   ,243,243,243
BEGIN DESCRIPTION:
Dam 1 (NDC) us
END DESCRIPTION:
XS GIS Cut Line= 5
      1488419.15        892973.6      1488180.16       892907.21
      1487704.93       892893.94      1487574.84       892880.66
      1487476.65       892893.93
#Sta/Elev= 30
  4518.1 1030.56  4540.9  1029.2  4607.4 1026.65    4666 1020.79  4681.3 1019.89
  4693.9  1019.2  4712.6  1018.9  4775.2  1013.3    4781 1012.24  4800.9 1010.97
  4813.5 1008.26    4860  1008.3  4997.7  988.25  5002.3  988.25    5115  1008.3
    5173 1008.28  5228.5 1008.26  5228.8 1010.03  5232.6 1011.22  5255.8 1013.73
  5291.7  1015.5  5333.6 1015.27    5355 1015.82  5366.3 1016.23  5378.2 1017.28
  5381.5 1018.17  5410.4 1029.51  5436.9 1036.39  5464.9 1036.81  5471.4 1037.85
#Mann= 5 ,-1 , 0
  4518.1     .07       0  4681.3     .14       0    4860    .035       0
    5115     .14       0    5173     .07       0
Bank Sta=4860,5115
Exp/Cntr=0.5,0.3

Type RM Length L Ch R = 5 ,91989   ,,,
BEGIN DESCRIPTION:
Dam 1 (NDC) tor
Structure ID: NDC Dam 1
Approximate Survey Structure
END DESCRIPTION:
IW Pilot Flow=0
#Inline Weir SE= 6
  4657.8  1020.9  4983.5 1021.72  5309.2  1020.9    5322    1017    5375    1017
  5411.5 1021.91
IW Dist,WD,Coef,Skew,MaxSub,Min_El,Is_Ogee,SpillHt,DesHd
23,100,3,0,0.95,, 0 ,,,1,1,

Type RM Length L Ch R = 1 ,91819   ,242,242,242
BEGIN DESCRIPTION:
Dam 1 (NDC) ds
END DESCRIPTION:
XS GIS Cut Line= 5
      1488328.84       892774.47      1487994.31       892657.65
      1487880.15       892657.65      1487704.93       892670.92
      1487601.35       892639.05
#Sta/Elev= 30
  4603.2 1015.36  4614.2 1014.18  4634.6 1013.86  4688.4 1008.04    4709 1007.39
  4737.3 1003.31    4757 1002.09  4772.2  999.08  4809.2  993.98  4898.8  985.22
  4949.3  983.78  4994.2  980.44  4996.2  979.78  4997.7  976.78  5002.3  976.78
  5003.8  979.78  5008.8  983.39  5010.5  983.61  5037.6  985.12  5060.7   984.8
  5095.1  986.58  5134.9  991.52  5163.9  997.86  5190.1 1006.89  5210.8 1012.18
  5259.3 1014.31  5281.9 1020.02  5311.7 1029.39  5339.8 1035.11  5355.8 1035.27
#Mann= 5 ,-1 , 0
  4603.2     .07       0  4809.2     .14       0  4996.2     .05       0
  5003.8     .14       0  5281.9     .07       0
Bank Sta=4996.2,5003.8
Exp/Cntr=0.5,0.3

Type RM Length L Ch R = 1 ,91577   ,247,247,247
BEGIN DESCRIPTION:
North Deep Creek 275.0
END DESCRIPTION:
XS GIS Cut Line= 5
      1488283.74       892593.95      1488140.34        892524.9
      1487994.31       892426.67      1487938.56       892405.43
        1487835.       892315.15
#Sta/Elev= 30
  4661.9 1004.55  4674.3 1003.84  4694.4  999.89  4708.2  998.37  4715.5  997.14
  4729.8  996.44  4736.6  993.99  4748.4  992.22  4771.9  989.32  4793.8  985.76
  4829.1  981.91  4835.9  981.65  4900.8  981.81    4918   982.1  4924.5  982.85
  4977.9   981.8  4996.2   978.6  4997.7   975.6  5002.3   975.6  5003.8   978.6
  5006.7  979.32  5035.2  981.46  5062.2  982.11  5069.6  982.63    5082  985.77
  5101.2  993.95    5122 1001.13  5148.6 1006.58  5184.5 1008.83  5194.1  1009.2
#Mann= 5 ,-1 , 0
  4661.9     .07       0  4748.4     .14       0  4996.2     .05       0
  5003.8     .14       0  5184.5     .07       0
Bank Sta=4996.2,5003.8
Exp/Cntr=0.3,0.1

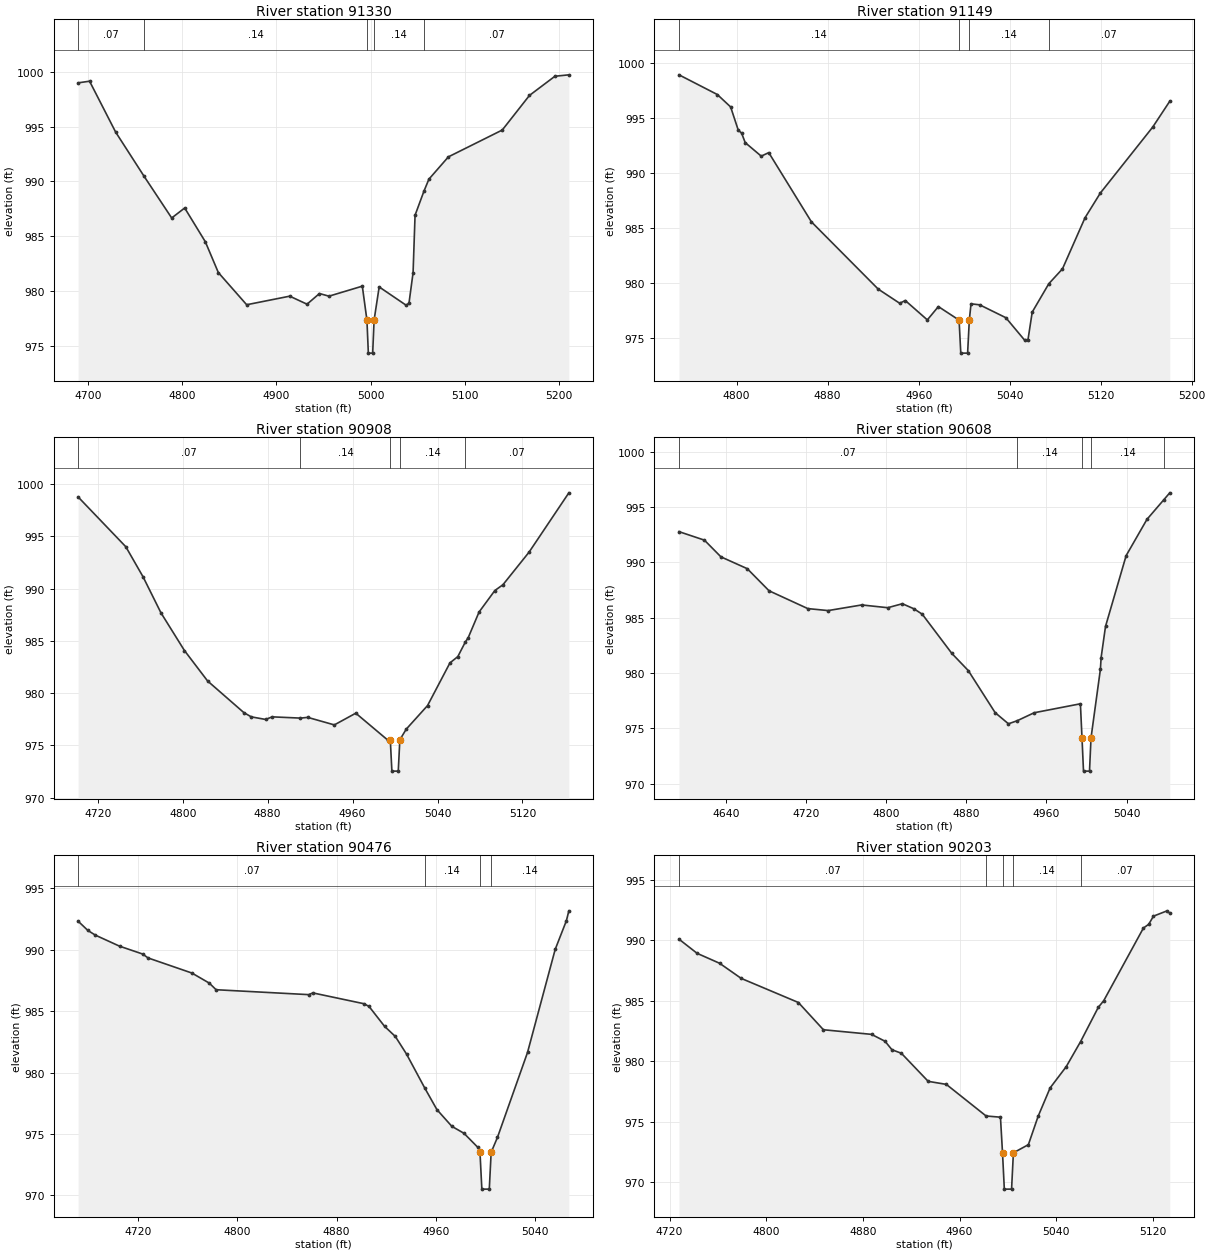
Type RM Length L Ch R = 1 ,91330   ,181,181,181
BEGIN DESCRIPTION:
North Deep Creek 274.0
END DESCRIPTION:
XS GIS Cut Line= 5
      1488413.78       892400.12       1488254.5        892307.2
      1488124.41       892246.14      1488055.38       892235.52
      1487933.27       892251.44
#Sta/Elev= 30
  4689.5  998.97  4701.7  999.12  4729.4  994.49  4759.3  990.51  4788.9  986.68
  4802.7  987.59  4824.6  984.52  4838.4  981.72  4868.5  978.79  4914.2  979.57
  4932.6  978.84  4945.8  979.81  4955.9  979.57  4991.3  980.48  4996.2  977.39
  4997.7  974.39  5002.3  974.39  5003.8  977.39  5009.2  980.41  5038.1  978.73
  5040.9  978.96  5045.2  981.71  5047.3  986.93  5056.7  989.11    5062  990.21
  5082.7  992.24  5139.9  994.68  5168.8  997.83  5195.8  999.57  5210.6   999.7
#Mann= 5 ,-1 , 0
  4689.5     .07       0  4759.3     .14       0  4996.2     .05       0
  5003.8     .14       0  5056.7     .07       0
Bank Sta=4996.2,5003.8
Exp/Cntr=0.3,0.1

Type RM Length L Ch R = 1 ,91149   ,241,241,241
BEGIN DESCRIPTION:
North Deep Creek 273.0
END DESCRIPTION:
XS GIS Cut Line= 4
      1488456.29       892336.42       1488336.8       892251.45
       1488230.6       892142.59      1488124.44       892062.97
#Sta/Elev= 30
  4749.3  998.91    4783  997.12  4794.7  995.99  4801.4  993.88  4804.3  993.62
  4807.5  992.75  4821.6  991.52  4828.2  991.84  4865.7  985.55  4924.4  979.44
  4943.3  978.15  4948.2   978.4  4967.6  976.64  4977.3  977.85  4995.5  976.62
    4997  973.62    5003  973.62  5004.5  976.62    5006   978.1  5013.6  978.01
  5036.6  976.84  5053.1   974.8    5056  974.79  5059.8  977.35  5074.4  979.93
  5086.4  981.28  5106.2  985.92  5119.7  988.17  5165.7  994.16  5180.7  996.51
#Mann= 4 ,-1 , 0
  4749.3     .14       0  4995.5     .05       0  5004.5     .14       0
  5074.4     .07       0
Bank Sta=4995.5,5004.5
Exp/Cntr=0.3,0.1

Type RM Length L Ch R = 1 ,90908   ,300,300,300
BEGIN DESCRIPTION:
North Deep Creek 272.0
END DESCRIPTION:
XS GIS Cut Line= 4
      1488626.18       892142.59      1488498.75       892092.15
      1488363.35       891985.95      1488212.05       891962.07
#Sta/Elev= 30
  4701.4  998.76  4746.4  993.99  4762.6  991.12  4779.5  987.67  4801.6  984.07
  4823.4  981.16  4857.5  978.14  4864.5  977.73  4878.1  977.48  4884.2  977.73
  4910.9  977.61  4917.7  977.68  4942.8  976.96    4963  978.08  4993.2   975.5
  4995.5  975.54    4997  972.54    5003  972.54  5004.5  975.54  5010.5  976.55
  5030.6  978.81  5051.7  982.89  5059.1  983.49    5066  984.85  5068.9   985.3
  5079.1  987.75    5094  989.81  5101.6  990.36  5126.3  993.49  5163.7  999.15
#Mann= 5 ,-1 , 0
  4701.4     .07       0  4910.9     .14       0  4995.5     .05       0
  5004.5     .14       0    5066     .07       0
Bank Sta=4995.5,5004.5
Exp/Cntr=0.3,0.1

Type RM Length L Ch R = 1 ,90608   ,132,132,132
BEGIN DESCRIPTION:
North Deep Creek 271.0
END DESCRIPTION:
XS GIS Cut Line= 4
      1488713.77       891927.52      1488541.23       891768.25
      1488381.93       891720.46      1488304.92       891675.31
#Sta/Elev= 30
  4592.8  992.79  4618.2  992.02  4634.7  990.51    4661  989.44  4682.8  987.44
  4721.5  985.83  4741.8  985.65  4775.4  986.16  4801.4  985.91    4816  986.27
  4827.6  985.81  4835.9  985.32  4865.5  981.77  4881.9  980.22  4908.7  976.42
    4922  975.41  4930.8  975.69  4947.7  976.41  4993.9  977.22  4995.5  974.13
    4997  971.13    5003  971.13  5004.5  974.13  5013.9  980.35  5014.6   981.4
    5019  984.22  5039.6  990.62  5060.4   993.9  5077.4  995.69  5083.2   996.3
#Mann= 5 ,-1 , 0
  4592.8     .07       0  4930.8     .14       0  4995.5     .05       0
  5004.5     .14       0  5077.4     .07       0
Bank Sta=4995.5,5004.5
Exp/Cntr=0.3,0.1

Type RM Length L Ch R = 1 ,90476   ,273,273,273
BEGIN DESCRIPTION:
North Deep Creek 270.0
END DESCRIPTION:
XS GIS Cut Line= 4
      1488713.83       891903.68      1488535.92       891736.39
      1488490.79        891659.4      1488458.91       891606.28
#Sta/Elev= 30
  4671.7  992.34  4679.6  991.58  4685.6   991.2  4705.1   990.3  4723.7  989.66
  4728.1  989.34  4763.4  988.11  4777.4  987.29  4782.9  986.75  4857.5  986.35
  4860.9  986.49    4902  985.61  4906.1  985.39  4918.6  983.77  4927.3  982.94
  4936.3  981.51    4951  978.74  4960.8  976.98  4972.8  975.62  4982.6  975.05
  4993.8   973.9  4995.5   973.5    4997   970.5    5003   970.5  5004.5   973.5
  5009.6  974.72  5033.8  981.64  5056.1  990.04  5065.1  992.37  5067.1  993.18
#Mann= 4 ,-1 , 0
  4671.7     .07       0    4951     .14       0  4995.5     .05       0
  5004.5     .14       0
Bank Sta=4995.5,5004.5
Exp/Cntr=0.3,0.1

Type RM Length L Ch R = 1 ,90203   ,158,158,158
BEGIN DESCRIPTION:
North Deep Creek 269.0
END DESCRIPTION:
XS GIS Cut Line= 4
      1488748.31       891869.13      1488782.83       891670.02
      1488745.66       891582.41      1488668.69       891505.44
#Sta/Elev= 30
  4727.8  990.09  4742.8  988.92  4761.4   988.1  4779.3  986.85  4826.6  984.86
  4847.3  982.61  4887.1  982.23  4898.3  981.66    4904  980.96  4911.8  980.67
    4934  978.35    4949   978.1  4981.9  975.49  4993.8  975.39  4995.5  972.45
    4997  969.45    5003  969.45  5004.5  972.45  5016.9  973.12    5025  975.47
  5034.9  977.81  5048.2  979.56  5060.1  981.63  5074.8  984.47  5079.2     985
  5112.1  991.01  5116.5  991.32  5120.4  991.99  5131.7  992.43  5133.9  992.23
#Mann= 5 ,-1 , 0
  4727.8     .07       0  4981.9     .14       0  4995.5     .05       0
  5004.5     .14       0  5060.1     .07       0
Bank Sta=4995.5,5004.5
Exp/Cntr=0.5,0.3

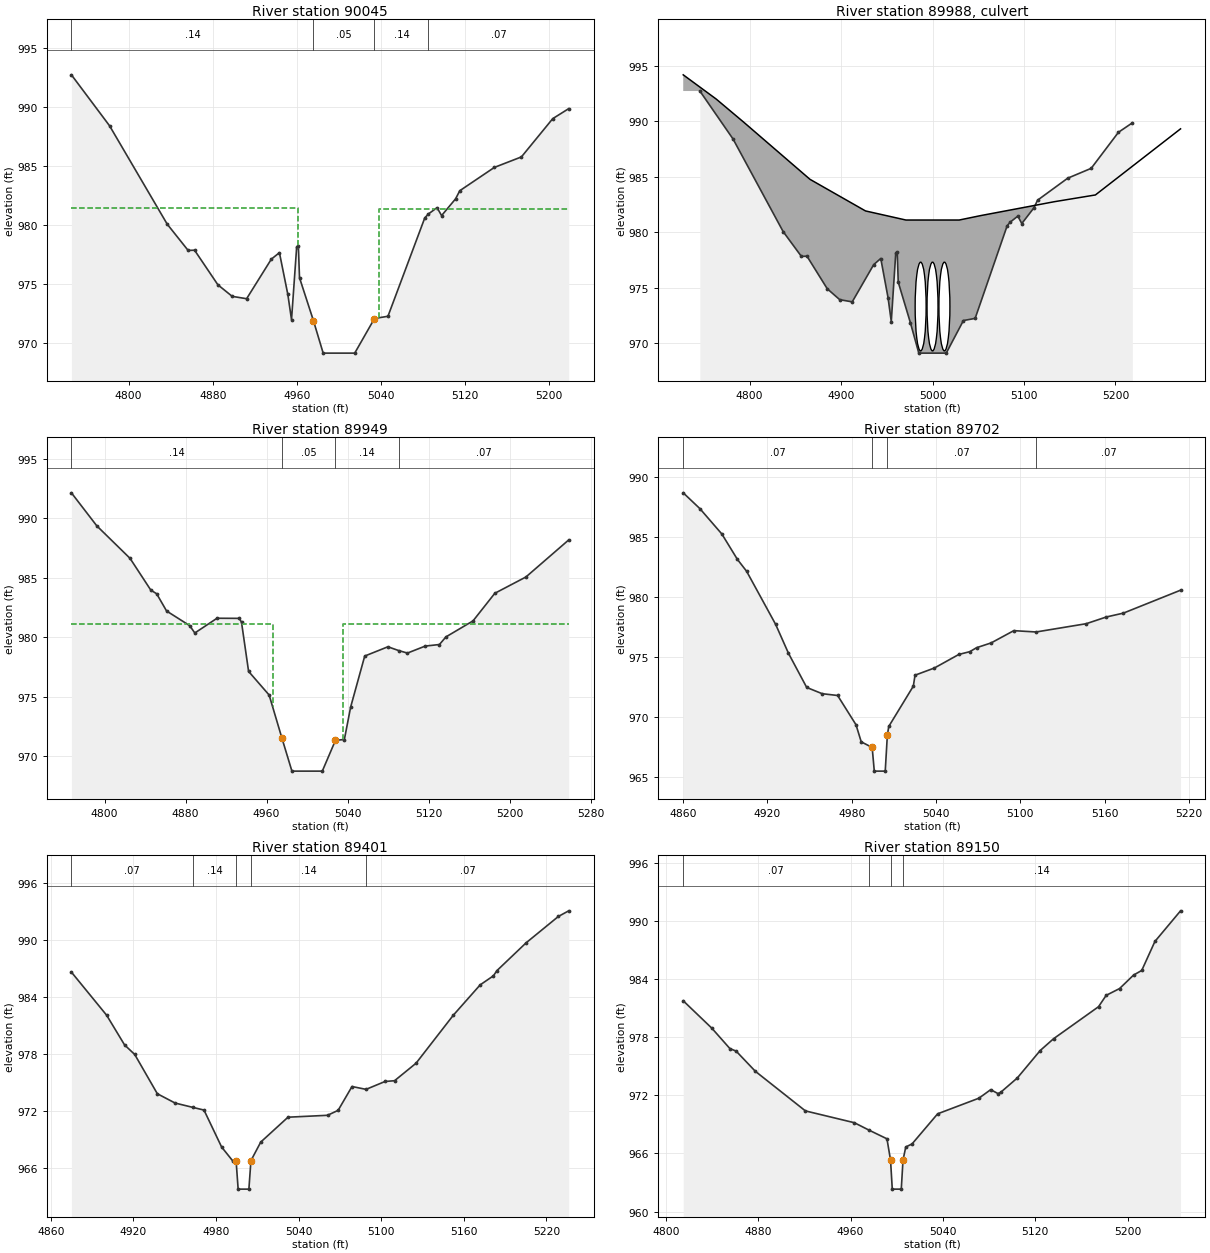
Type RM Length L Ch R = 1 ,90045   ,96,96,96
BEGIN DESCRIPTION:
Sprouse Rd (NDC) us
END DESCRIPTION:
XS GIS Cut Line= 5
      1489064.24       891801.43      1488976.64       891723.12
       1488931.5       891628.87      1488870.44       891579.75
      1488766.92       891441.72
#Sta/Elev= 30
  4745.6  992.73  4781.9   988.4  4836.7  980.05  4856.6  977.82  4862.7  977.84
  4884.9   974.9  4898.5  973.92  4912.2  973.72  4935.7  977.08  4943.4  977.63
  4951.4  974.08  4954.9  971.94  4959.8  978.12  4961.4  978.22  4962.5   975.5
  4975.8  971.84    4985   969.1    5015   969.1  5033.8  972.04  5046.6  972.23
  5081.6  980.58  5085.1  980.92  5093.3  981.45  5097.6  980.78  5110.9   982.2
  5114.9  982.89  5147.8  984.87  5173.5  985.76  5203.3  989.01  5218.5  989.86
#Mann= 4 ,-1 , 0
  4745.6     .14       0  4975.8     .05       0  5033.8     .14       0
  5085.1     .07       0
#XS Ineff= 2 , 0
       0  4961.5  981.44  5038.5       0   981.3
Permanent Ineff=
       F       F
Bank Sta=4975.8,5033.8
Exp/Cntr=0.5,0.3

Type RM Length L Ch R = 2 ,89988   ,,,
BEGIN DESCRIPTION:
Sprouse Rd (NDC) tor
Structure ID: LDS_NDC_20
Approximate Survey Structure
END DESCRIPTION:
Bridge Culvert--1,0,-1,-1, 0
Deck Dist Width WeirC Skew NumUp NumDn MinLoCord MaxHiCord MaxSubmerge Is_Ogee
19.5,75,3,0, 11, 11, , , 0.95, 0, 1,1,,
  4727.4  4763.4  4793.7    4866  4926.7  4970.9  5029.2  5052.7  5133.1  5178.1
  5271.2
  994.19  992.01  989.91  984.77  981.92   981.1   981.1   981.5  982.75  983.36
  989.32
   949.1   949.1   949.1   949.1   949.1   949.1   949.1   949.1   949.1   949.1
   949.1
  4727.4  4763.4  4793.7    4866  4926.7  4970.9  5029.2  5052.7  5133.1  5178.1
  5271.2
  994.19  992.01  989.91  984.77  981.92   981.1   981.1   981.5  982.75  983.36
  989.32
  948.73  948.73  948.73  948.73  948.73  948.73  948.73  948.73  948.73  948.73
  948.73
Culvert=3,8,12,75,0.024,0.5,1,34,1,969.3,4987,968.93,4987,Culvert #1  , 0 ,19.5
Culvert Bottom n=0.024
Culvert=3,8,12,75,0.024,0.5,1,34,1,969.3,5000,968.93,5000,Culvert #2  , 0 ,19.5
Culvert Bottom n=0.024
Culvert=3,8,12,75,0.024,0.5,1,34,1,969.3,5013,968.93,5013,Culvert #3  , 0 ,19.5
Culvert Bottom n=0.024
BC Design=,, 0 ,, 0 ,,,,,,
BC HTab HWMax=992.73

Type RM Length L Ch R = 1 ,89949   ,247,247,247
BEGIN DESCRIPTION:
Sprouse Rd (NDC) ds
END DESCRIPTION:
XS GIS Cut Line= 4
      1489142.57       891768.25      1489027.08       891607.63
      1488975.31       891571.79      1488802.73       891419.12
#Sta/Elev= 30
  4767.2  992.14  4792.3  989.36  4825.1  986.63  4845.6  983.96  4851.4  983.65
  4861.2   982.2    4884  980.97  4889.1  980.35    4911  981.59    4933  981.58
  4935.2  981.26  4942.2  977.12  4962.5  975.13    4975  971.54    4985  968.73
    5015  968.73    5028  971.32  5036.8  971.39    5043  974.12  5056.9  978.41
  5079.8  979.19  5090.5  978.87  5099.1  978.66  5116.7  979.25  5130.7  979.38
  5137.1  980.02  5163.9  981.37  5185.4  983.69  5216.1  985.06  5258.4  988.18
#Mann= 4 ,-1 , 0
  4767.2     .14       0    4975     .05       0    5028     .14       0
  5090.5     .07       0
#XS Ineff= 2 , 0
       0  4966.1   981.1  5035.4       0   981.1
Permanent Ineff=
       F       F
Bank Sta=4975,5028
Exp/Cntr=0.5,0.3

Type RM Length L Ch R = 1 ,89702   ,301,301,301
BEGIN DESCRIPTION:
North Deep Creek 268.0
END DESCRIPTION:
XS GIS Cut Line= 4
      1489215.85       891331.68      1489093.32       891381.69
      1489037.07       891447.94       1488903.3       891464.19
#Sta/Elev= 30
  4860.1  988.71    4872  987.39  4887.6  985.28  4898.7  983.16  4905.2  982.18
  4925.9  977.75    4935  975.35    4948   972.5    4959  971.98    4970  971.83
  4983.1  969.39  4986.8  967.97  4994.6   967.5  4996.1  965.53  5003.9  965.53
  5005.4  968.53  5006.4  969.25  5023.9  972.61  5025.1  973.52  5038.9  974.12
  5056.3  975.25  5064.1  975.48  5068.9  975.81  5079.3  976.21  5095.4  977.23
  5111.3  977.12    5147  977.81  5161.3  978.37  5173.4  978.69  5214.1   980.6
#Mann= 4 ,-1 , 0
  4860.1     .07       0  4994.6    .045       0  5005.4     .07       0
  5111.3     .07       0
Bank Sta=4994.6,5005.4
Exp/Cntr=0.3,0.1

Type RM Length L Ch R = 1 ,89401   ,251,251,251
BEGIN DESCRIPTION:
North Deep Creek 267.0
END DESCRIPTION:
XS GIS Cut Line= 3
      1489078.89       891084.36      1488931.57       891130.19
      1488725.31       891146.56
#Sta/Elev= 30
    4875   986.6  4900.6  982.06  4913.6  978.94    4921  977.93  4937.4   973.8
  4950.3  972.82  4963.3  972.36  4971.3  972.08  4984.1  968.19    4992  966.76
  4994.6  966.76  4996.1  963.76  5003.9  963.76  5005.4  966.76  5012.5  968.71
  5032.3  971.33    5061  971.53  5068.7  972.05  5078.8  974.56    5089  974.26
  5102.8  975.09  5109.7  975.17  5125.3  977.01  5152.4  982.07  5171.9  985.26
  5181.5  986.21    5184  986.75  5205.3  989.69  5228.7  992.46  5236.2  993.05
#Mann= 5 ,-1 , 0
    4875     .07       0  4963.3     .14       0  4994.6     .05       0
  5005.4     .14       0    5089     .07       0
Bank Sta=4994.6,5005.4
Exp/Cntr=0.3,0.1

Type RM Length L Ch R = 1 ,89150   ,337,337,337
BEGIN DESCRIPTION:
North Deep Creek 266.0
END DESCRIPTION:
XS GIS Cut Line= 4
      1489062.48       890887.91       1488915.2       890871.55
      1488771.14       890933.75      1488649.99        890966.5
#Sta/Elev= 30
  4815.1  981.74  4839.9  978.91  4855.5  976.81  4860.9  976.55  4877.6  974.46
  4920.9  970.38  4963.3  969.16  4975.9   968.4  4991.5   967.5  4994.6  965.31
  4996.1  962.31  5003.9  962.31  5005.4  965.31  5007.8  966.66  5013.2  966.97
  5035.4  970.08  5071.1  971.69  5081.3  972.57  5087.6  972.17  5089.9  972.29
  5104.3  973.77  5124.2  976.61  5135.7  977.82  5174.7  981.13  5181.3   982.3
  5192.9     983    5205  984.39  5212.1  984.87  5223.5  987.86  5245.7  991.02
#Mann= 4 ,-1 , 0
  4815.1     .07       0  4975.9     .14       0  4994.6     .05       0
  5005.4     .14       0
Bank Sta=4994.6,5005.4
Exp/Cntr=0.3,0.1

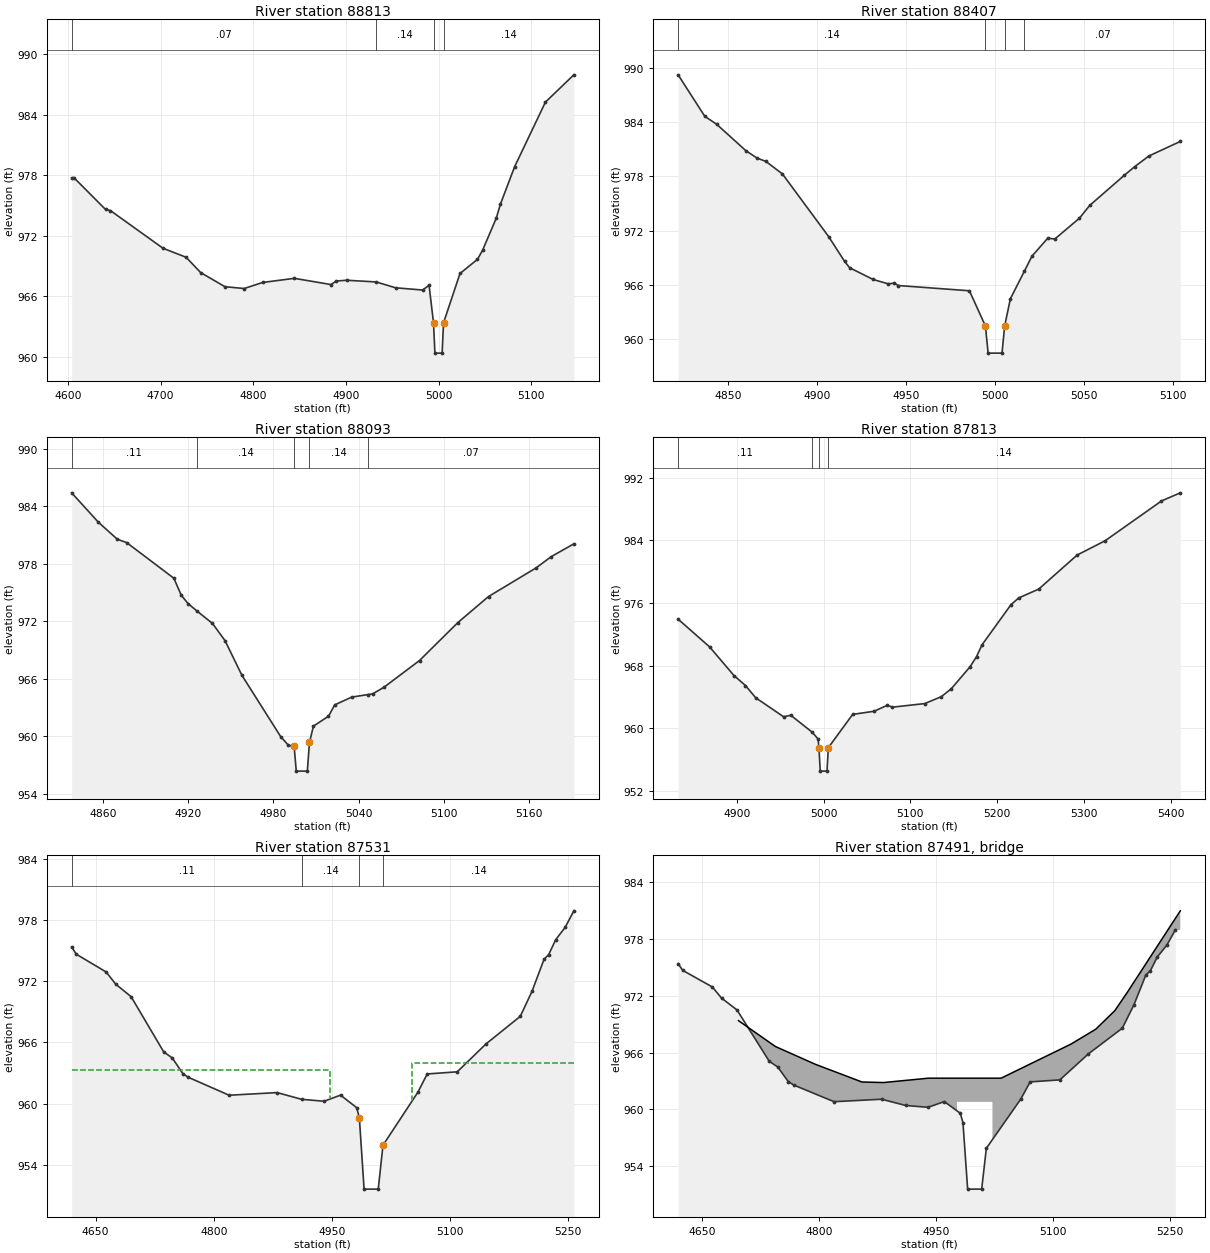
Type RM Length L Ch R = 1 ,88813   ,406,406,406
BEGIN DESCRIPTION:
North Deep Creek 265.0
END DESCRIPTION:
XS GIS Cut Line= 3
      1489085.41       890747.12      1488715.48       890596.53
      1488600.86       890511.38
#Sta/Elev= 30
  4603.9  977.74  4606.2  977.79  4640.5  974.62  4645.8  974.51  4702.6  970.77
  4727.5  969.88  4743.2  968.36  4769.4  966.96  4790.2  966.78  4810.1  967.38
  4844.3  967.79  4884.1  967.17  4889.4  967.52  4900.8   967.6  4932.9  967.43
  4953.6  966.85  4982.9  966.63  4989.8   967.1  4994.6  963.37  4996.1  960.37
  5003.9  960.37  5005.4  963.37  5023.2  968.27    5042  969.67  5047.6  970.58
  5062.4  973.77  5066.8  975.14  5082.2  978.87  5115.4  985.27  5146.1  987.98
#Mann= 4 ,-1 , 0
  4603.9     .07       0  4932.9     .14       0  4994.6     .05       0
  5005.4     .14       0
Bank Sta=4994.6,5005.4
Exp/Cntr=0.3,0.1

Type RM Length L Ch R = 1 ,88407   ,314,314,314
BEGIN DESCRIPTION:
North Deep Creek 264.0
END DESCRIPTION:
XS GIS Cut Line= 4
      1489213.12       890406.64      1489088.72       890409.91
      1489026.51       890406.64      1488938.11       890370.62
#Sta/Elev= 30
  4821.9  989.26  4836.9  984.66  4843.5  983.79    4860  980.85  4866.3  980.03
  4871.2  979.67  4880.5  978.28  4906.5  971.33  4915.4   968.6  4918.3  967.88
  4931.5  966.58  4939.8  966.11  4943.4  966.16  4945.7  965.91  4985.6  965.33
  4994.6  961.42  4996.1  958.42  5003.9  958.42  5005.4  961.42  5008.6  964.44
  5016.5  967.51  5020.8  969.18  5029.6  971.15  5033.6  971.07  5047.4  973.37
  5053.2  974.79  5072.6  978.12  5078.5  979.09  5086.4  980.26  5104.1  981.88
#Mann= 4 ,-1 , 0
  4821.9     .14       0  4994.6     .05       0  5005.4     .14       0
  5016.5     .07       0
Bank Sta=4994.6,5005.4
Exp/Cntr=0.3,0.1

Type RM Length L Ch R = 1 ,88093   ,280,280,280
BEGIN DESCRIPTION:
North Deep Creek 263.0
END DESCRIPTION:
XS GIS Cut Line= 4
      1489265.55       890138.18      1489160.75       890102.16
      1489059.25       890115.25      1488934.88       890180.71
#Sta/Elev= 30
  4837.9   985.4  4856.8  982.32  4870.1  980.55  4876.7   980.2  4909.9  976.48
  4915.1  974.71  4919.9  973.83    4926  973.08  4937.1  971.76    4946  969.95
  4957.8  966.35  4985.1  959.95  4990.6  959.03  4994.6  958.94  4996.1  956.34
  5003.9  956.34  5005.4  959.34  5008.2  961.04  5018.8  962.07  5023.2  963.26
  5035.2  964.07  5046.9  964.34  5049.8   964.4  5057.8  965.09  5082.9  967.89
  5109.9  971.85  5131.5  974.57    5165  977.56  5175.8  978.75  5191.6  980.07
#Mann= 5 ,-1 , 0
  4837.9     .11       0    4926     .14       0  4994.6     .05       0
  5005.4     .14       0  5046.9     .07       0
Bank Sta=4994.6,5005.4
Exp/Cntr=0.3,0.1

Type RM Length L Ch R = 1 ,87813   ,282,282,282
BEGIN DESCRIPTION:
North Deep Creek 262.0
END DESCRIPTION:
XS GIS Cut Line= 4
      1489258.98       889941.74      1489190.21       889850.06
      1489029.79        889794.4       1488735.1        889794.4
#Sta/Elev= 30
  4832.2  973.93  4868.6  970.37  4896.6  966.72  4909.9  965.44  4921.6  963.88
  4953.9  961.44  4962.1  961.64  4986.7  959.48  4993.6   958.6  4994.6  957.49
  4996.1  954.49  5003.9  954.49  5005.4  957.49  5033.5  961.75  5058.3  962.15
  5073.5  962.92  5079.2  962.67  5116.6  963.13  5135.8  964.02  5147.3  965.04
    5169  967.86  5176.3  969.13  5182.6  970.64  5215.9  975.76  5224.9  976.64
  5248.1  977.78  5292.3  982.13  5324.6  983.96  5389.6  989.05  5411.3  990.09
#Mann= 4 ,-1 , 0
  4832.2     .11       0  4986.7     .14       0  4994.6     .05       0
  5005.4     .14       0
Bank Sta=4994.6,5005.4
Exp/Cntr=0.5,0.3

Type RM Length L Ch R = 1 ,87531   ,92,92,92
BEGIN DESCRIPTION:
Mitchells Chapel Rd (NDC) us
END DESCRIPTION:
XS GIS Cut Line= 4
      1489291.71       889941.71      1489219.68       889575.04
       1489185.3       889486.64      1489157.48       889319.67
#Sta/Elev= 30
  4619.6  975.38  4625.5  974.67  4663.5  972.92  4675.4  971.74  4695.1   970.5
  4736.5  965.08  4747.4  964.48  4760.9  962.94  4767.8  962.58  4819.6  960.82
  4880.6  961.08  4911.6  960.42  4940.2  960.23  4961.1  960.83  4981.6   959.6
    4985   958.6    4991   951.6    5009   951.6    5015  955.91  5059.3  961.11
  5071.2  962.91  5109.3  963.12    5146  965.87  5189.4  968.57  5204.3  971.03
  5219.5  974.16  5225.5  974.64  5234.4   976.1  5246.4  977.31  5257.4  978.93
#Mann= 4 ,-1 , 0
  4619.6     .11       0  4911.6     .14       0    4985     .05       0
    5015     .14       0
#XS Ineff= 2 , 0
       0  4948.3   963.3  5051.8       0  963.98
Permanent Ineff=
       F       F
Bank Sta=4985,5015
Exp/Cntr=0.5,0.3

Type RM Length L Ch R = 3 ,87491   ,,,
BEGIN DESCRIPTION:
Mitchells Chapel Rd (NDC) tor
Structure ID: LDS_NDC_19
Approximate Survey Structure
END DESCRIPTION:
Bridge Culvert--1,0,-1,-1, 0
Deck Dist Width WeirC Skew NumUp NumDn MinLoCord MaxHiCord MaxSubmerge Is_Ogee
29,22,3,0, 16, 16, , , 0.95, 0, 1,1,,
    4697  4744.4  4795.8  4855.4  4882.9  4940.7  4977.3  4977.3  5022.8  5022.8
  5033.9  5123.7  5155.4  5179.9  5195.8  5263.8
  969.37  966.64  964.76   962.9  962.84   963.3   963.3   963.3   963.3   963.3
   963.3   966.9  968.47  970.43  972.35  980.95
   931.6   931.6   931.6   931.6   931.6   931.6   931.6   960.8   960.8   931.6
   931.6   931.6   931.6   931.6   931.6   931.6
    4697  4744.4  4795.8  4855.4  4882.9  4940.7  4977.3  4977.3  5022.8  5022.8
  5033.9  5123.7  5155.4  5179.9  5195.8  5263.8
  969.37  966.64  964.76   962.9  962.84   963.3   963.3   963.3   963.3   963.3
   963.3   966.9  968.47  970.43  972.35  980.95
   931.6   931.6   931.6   931.6   931.6   931.6   931.6   960.8   960.8   931.6
   931.6   931.6   931.6   931.6   931.6   931.6
Abutment Skew #Up #Dn= , 2 , 2
  4977.3    4986
   960.8  957.43
  4977.3    4986
   960.8  957.18
Abutment Skew #Up #Dn= , 2 , 2
    5014  5022.8
  957.43   960.8
    5014  5022.8
  957.18   960.8
BR Coef= 1 , 1 , 0 ,1.25, 0 ,,,0.8,0,2,0,
WSPro=,,,, 1 ,,,, 0 ,,,, 0 ,,,,-1 ,-1 ,-1 , 0 , 0 , 0 , 0 , 0
BC Design=,, 0 ,, 0 ,,,,,,
BC HTab HWMax=978.93

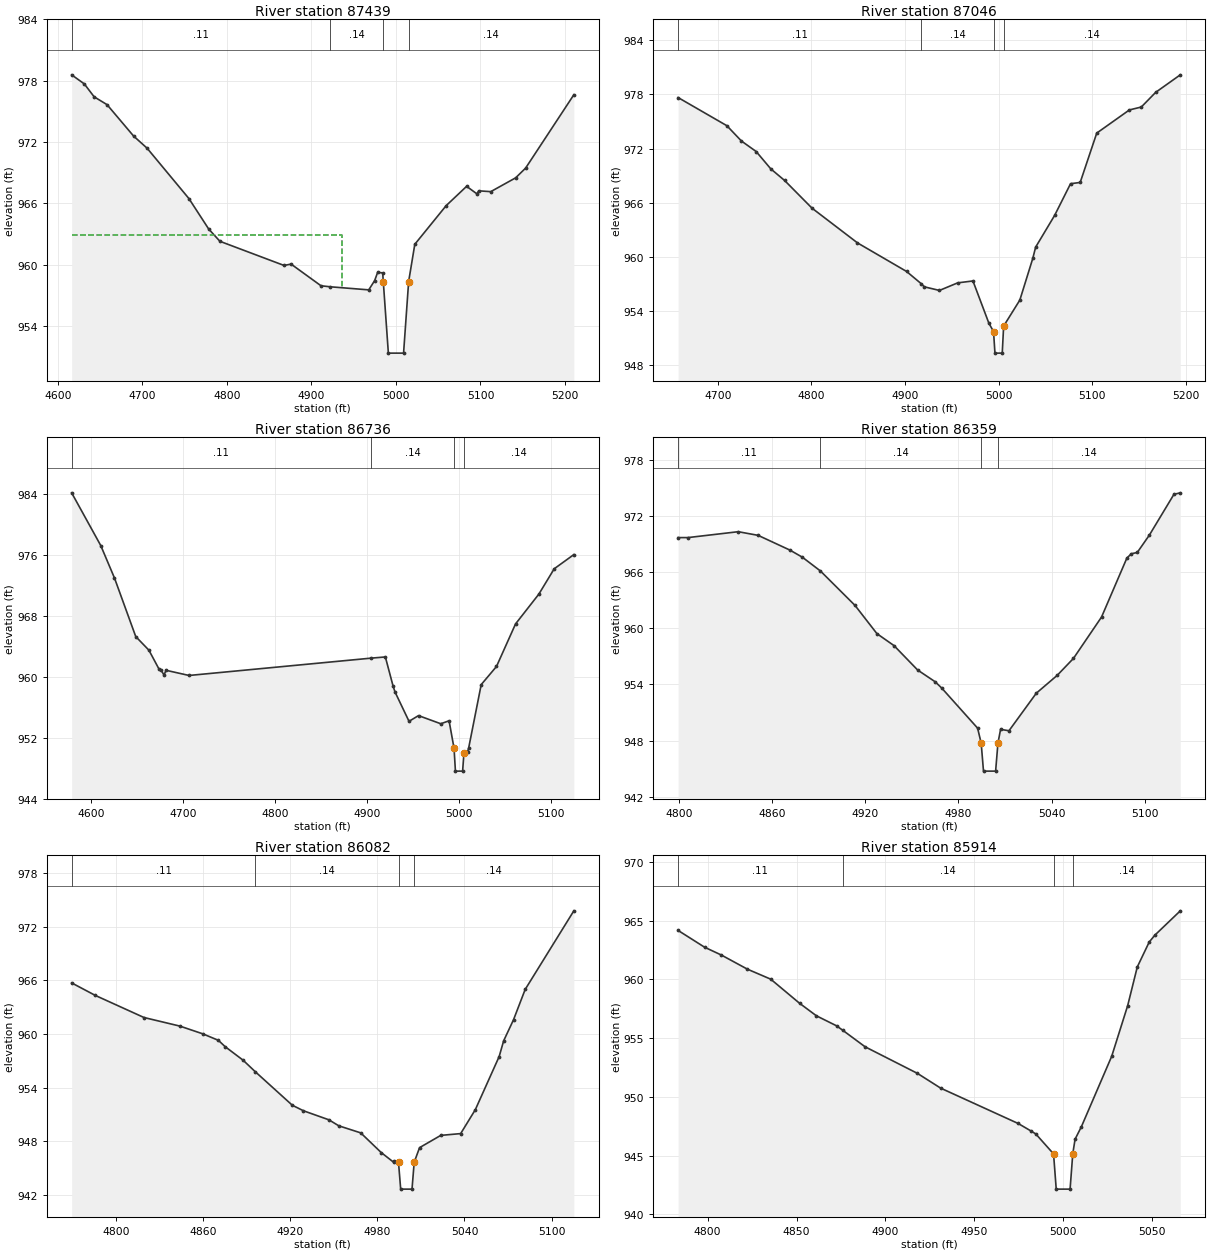
Type RM Length L Ch R = 1 ,87439   ,393,393,393
BEGIN DESCRIPTION:
Mitchells Chapel Rd (NDC) ds
END DESCRIPTION:
XS GIS Cut Line= 4
       1489388.3       889902.46       1489304.8       889543.94
      1489278.61       889473.55      1489290.07       889322.91
#Sta/Elev= 30
  4616.2  978.58  4631.2  977.69  4642.8  976.43  4658.1  975.66  4689.5  972.59
  4705.5   971.4    4755  966.47  4778.4  963.49  4791.7  962.29  4867.5  959.93
  4875.9  960.06  4911.3  957.94  4922.3  957.84  4967.8  957.54  4974.8  958.45
  4978.3  959.25  4984.3   959.2    4985  958.35    4991  951.35    5009  951.35
    5015  958.35  5022.3     962  5059.4  965.78  5083.6  967.67  5095.7  966.94
    5098  967.23  5112.2  967.15  5141.6   968.5  5153.4  969.45  5210.5  976.63
#Mann= 4 ,-1 , 0
  4616.2     .11       0  4922.3     .14       0    4985     .05       0
    5015     .14       0
#XS Ineff= 2 , 0
       0  4936.3  962.86  5063.8       0   964.6
Permanent Ineff=
       F       F
Bank Sta=4985,5015
Exp/Cntr=0.5,0.3

Type RM Length L Ch R = 1 ,87046   ,310,310,310
BEGIN DESCRIPTION:
North Deep Creek 261.0
END DESCRIPTION:
XS GIS Cut Line= 4
      1489467.59       889886.52      1489588.38       889655.93
      1489665.24       889590.05      1489822.63       889513.19
#Sta/Elev= 30
  4657.5  977.65  4709.6  974.53  4725.2  972.83  4740.9  971.67  4756.6  969.74
  4771.3  968.46  4800.6  965.39  4849.2  961.54  4901.7  958.37  4917.5     957
  4920.6  956.67  4936.8  956.27  4956.3  957.11  4972.6  957.32  4989.6  952.64
  4994.6  951.71  4996.1  949.32  5003.9  949.32  5005.4  952.32  5022.7   955.2
  5036.6  959.84  5039.6  961.07  5059.9  964.59  5076.9   968.1  5087.2  968.24
  5104.9  973.71  5139.8  976.28  5152.5   976.6  5167.9  978.23  5194.2  980.17
#Mann= 4 ,-1 , 0
  4657.5     .11       0  4917.5     .14       0  4994.6     .05       0
  5005.4     .14       0
Bank Sta=4994.6,5005.4
Exp/Cntr=0.3,0.1

Type RM Length L Ch R = 1 ,86736   ,377,377,377
BEGIN DESCRIPTION:
North Deep Creek 260.0
END DESCRIPTION:
XS GIS Cut Line= 4
      1489976.34       890102.46        1489980.       889805.99
      1489936.08       889677.89      1489936.08        889564.4
#Sta/Elev= 30
  4579.3  984.18  4610.9  977.26  4625.8     973  4648.9  965.31  4663.2  963.52
  4673.9   961.1  4676.4  960.91  4679.6  960.26  4681.8  960.88  4706.8   960.2
  4904.1  962.47    4920  962.63  4928.4   958.8  4930.5  958.03  4945.7  954.18
    4956  954.93  4980.2  953.86  4989.2  954.25  4994.6  950.64  4996.1  947.64
  5003.9  947.64  5005.4  950.06  5009.3  950.17  5010.4  950.63  5024.1     959
  5040.7  961.38  5061.4  966.97  5086.7  970.88  5103.4  974.21  5124.7  976.07
#Mann= 4 ,-1 , 0
  4579.3     .11       0  4904.1     .14       0  4994.6     .05       0
  5005.4     .14       0
Bank Sta=4994.6,5005.4
Exp/Cntr=0.3,0.1

Type RM Length L Ch R = 1 ,86359   ,277,277,277
BEGIN DESCRIPTION:
North Deep Creek 259.0
END DESCRIPTION:
XS GIS Cut Line= 3
      1490327.68       889882.82      1490298.41       889798.67
      1490298.41       889564.46
#Sta/Elev= 30
  4799.5  969.72  4805.8  969.72  4838.2  970.35    4851  969.96  4871.5  968.38
  4879.5  967.62  4891.1  966.15  4913.4  962.46  4927.5  959.44  4938.5  958.16
  4953.7  955.55    4965  954.29  4969.2  953.62  4992.3  949.33  4994.6  947.73
  4996.1  944.73  5003.9  944.73  5005.4  947.73  5007.1   949.2  5012.5  949.05
  5030.1  953.07  5043.5  954.97    5054  956.79  5072.1  961.22  5088.4  967.53
  5091.3  967.99  5095.1  968.13  5102.9  969.99  5118.7  974.35  5122.8  974.51
#Mann= 4 ,-1 , 0
  4799.5     .11       0  4891.1     .14       0  4994.6     .05       0
  5005.4     .14       0
Bank Sta=4994.6,5005.4
Exp/Cntr=0.3,0.1

Type RM Length L Ch R = 1 ,86082   ,168,168,168
BEGIN DESCRIPTION:
North Deep Creek 258.0
END DESCRIPTION:
XS GIS Cut Line= 4
      1490455.79       889926.77      1490550.95       889798.67
      1490572.91       889721.81      1490572.91       889615.62
#Sta/Elev= 30
  4769.6  965.72  4785.9  964.32  4819.4  961.85  4844.1  960.89  4859.8  960.03
  4870.6   959.3  4875.2   958.6  4887.6  957.08    4896  955.79  4921.5  952.04
  4929.2  951.42  4946.7  950.41  4953.5  949.74  4968.6  948.95  4982.7  946.75
  4991.3  945.66  4991.7  945.79  4994.6  945.66  4996.1  942.66  5003.9  942.66
  5005.4  945.66  5009.1   947.3  5023.7  948.67  5037.4  948.87  5047.5  951.55
  5063.9  957.49    5067  959.25  5073.8  961.61  5081.8  964.99  5115.3  973.78
#Mann= 4 ,-1 , 0
  4769.6     .11       0    4896     .14       0  4994.6     .05       0
  5005.4     .14       0
Bank Sta=4994.6,5005.4
Exp/Cntr=0.3,0.1

Type RM Length L Ch R = 1 ,85914   ,143,143,143
BEGIN DESCRIPTION:
North Deep Creek 257.0
END DESCRIPTION:
XS GIS Cut Line= 3
      1490499.74        889941.4      1490671.73       889842.59
      1490755.88       889842.59
#Sta/Elev= 27
  4783.4  964.17  4798.3  962.74  4807.8  962.07  4822.4  960.87  4835.5  960.02
  4851.7  957.97  4861.2   956.9  4872.5  956.05    4876  955.67  4888.6  954.26
    4918     952  4931.1  950.74  4974.7  947.73  4981.8   947.1  4984.6  946.84
  4994.6  945.14  4996.1  942.14  5003.9  942.14  5005.4  945.14  5006.7  946.39
  5010.3  947.47  5027.3  953.45  5036.3  957.77  5041.7  961.06  5048.4  963.18
  5051.6  963.77  5065.9  965.84
#Mann= 4 ,-1 , 0
  4783.4     .11       0    4876     .14       0  4994.6     .05       0
  5005.4     .14       0
Bank Sta=4994.6,5005.4
Exp/Cntr=0.3,0.1