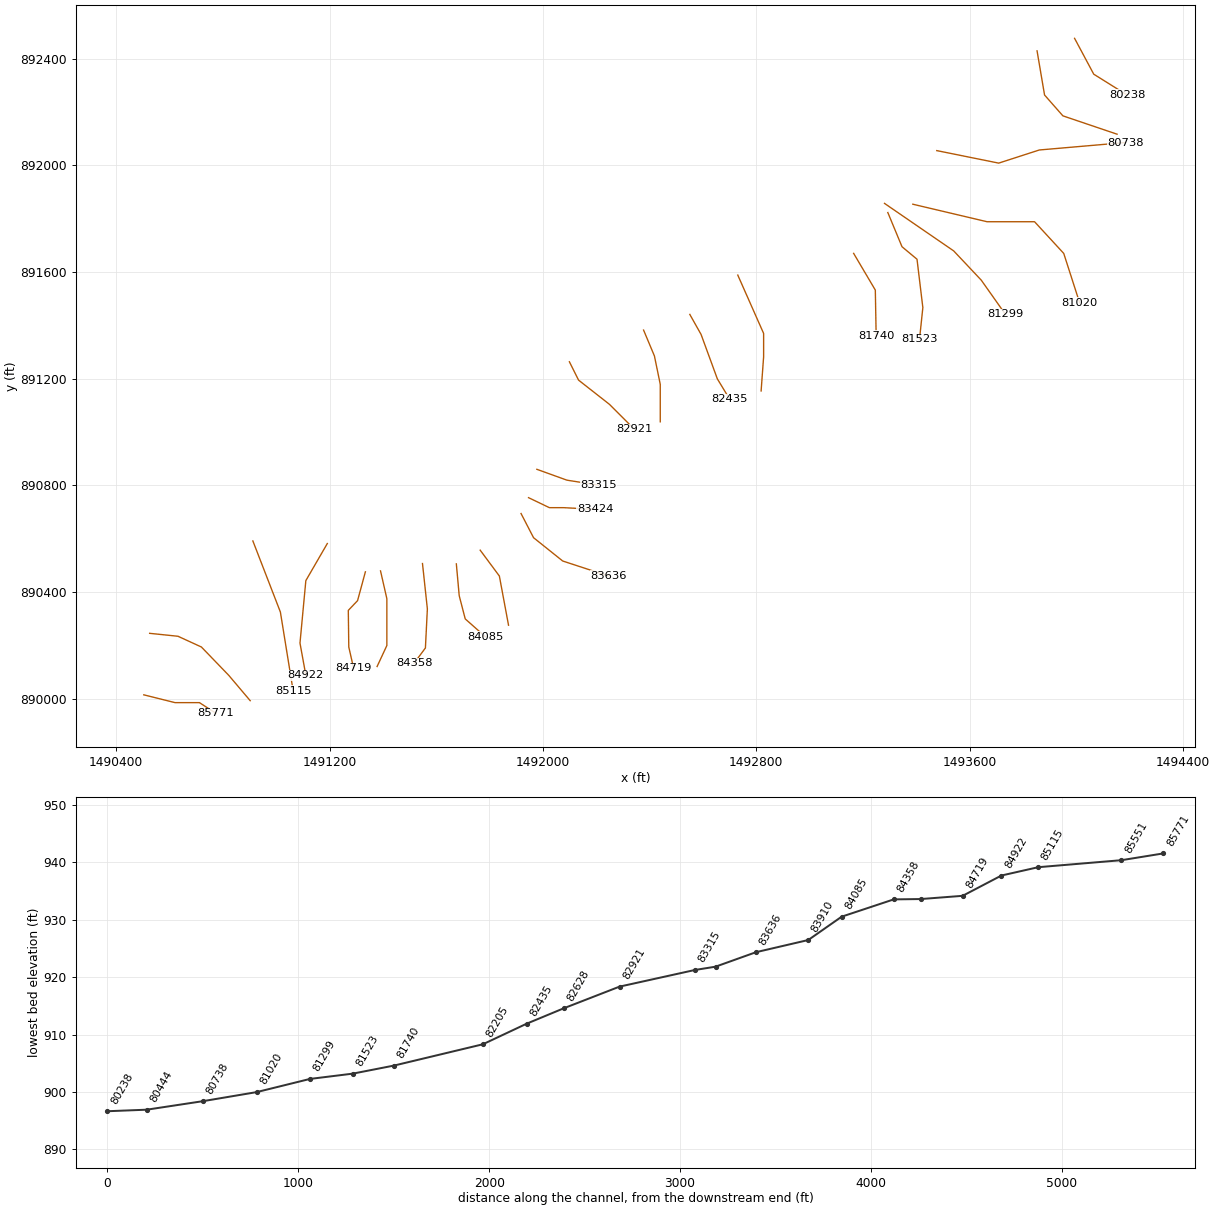
HEC-RAS study North Deep Creek.prj: North Deep Creek Limited Detail Study

--- North Deep Creek.g01 (geometry) --- (continued)

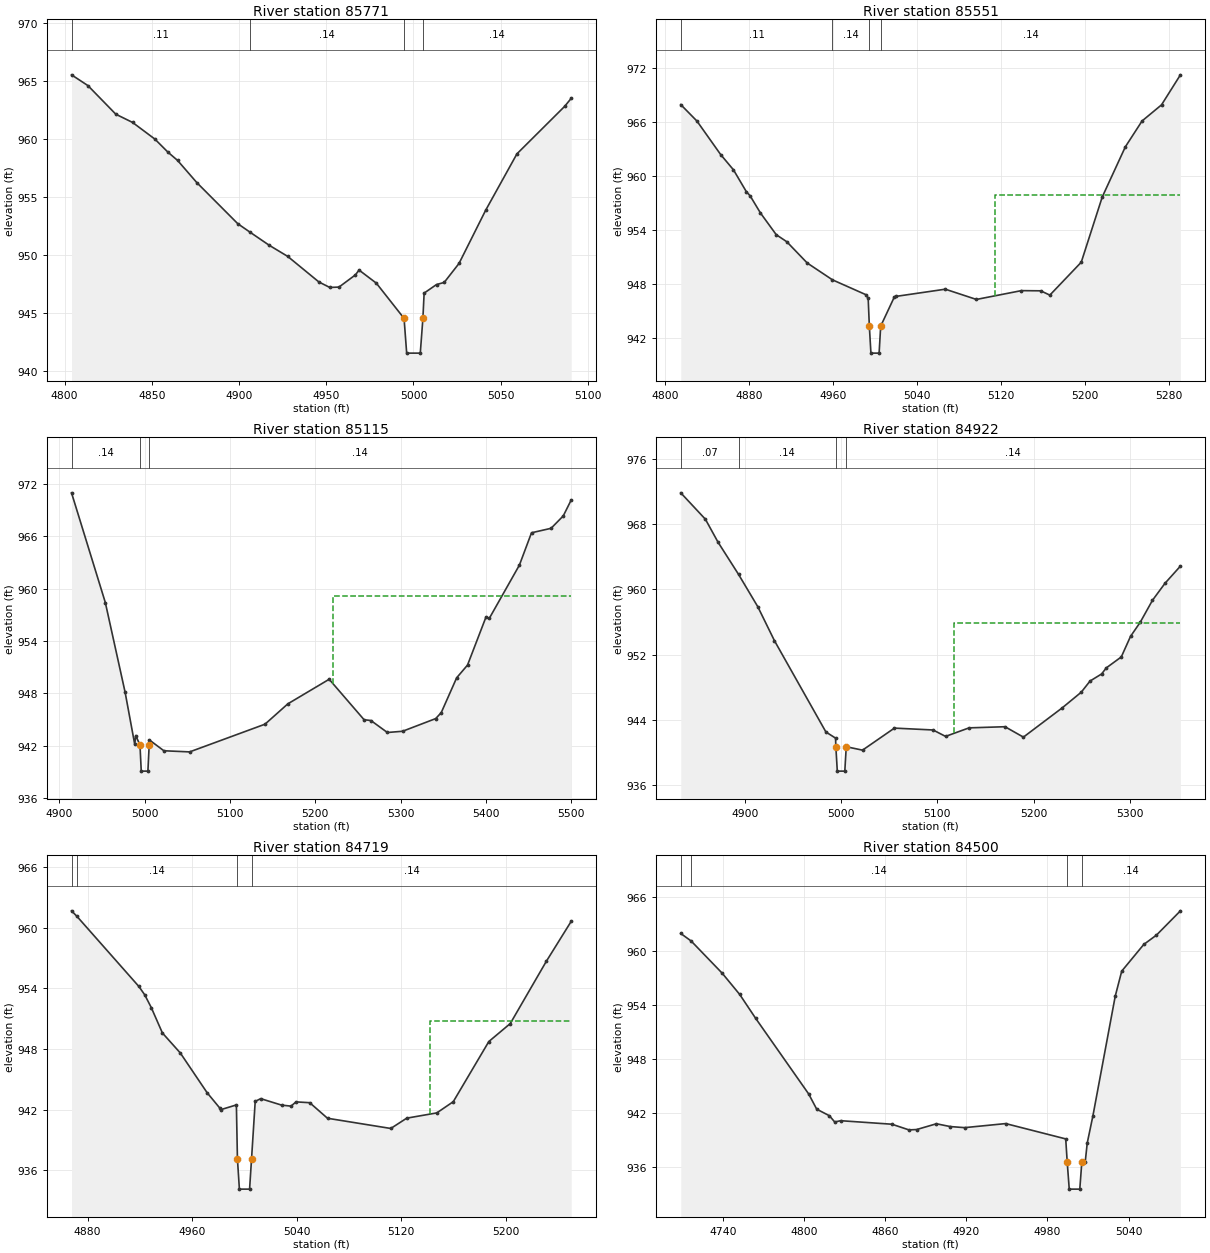
Type RM Length L Ch R = 1 ,85771   ,220,220,220
BEGIN DESCRIPTION:
North Deep Creek 256.0
END DESCRIPTION:
XS GIS Cut Line= 4
      1490503.35       890014.62      1490620.49       889985.33
      1490711.99       889985.33      1490774.24       889945.05
#Sta/Elev= 30
    4804  965.53  4813.4   964.6  4829.4  962.13    4839  961.42  4851.8  959.98
  4859.3  958.85  4864.8  958.14  4875.8  956.23  4899.3  952.68  4906.3  951.95
  4917.3  950.82  4927.9  949.86  4945.8  947.65    4952  947.18  4957.3  947.21
  4966.7  948.26  4968.8  948.68  4978.7  947.55  4994.6  944.51  4996.1  941.51
  5003.9  941.51  5005.4  944.51  5006.1  946.69  5013.2  947.43  5017.6  947.61
  5026.1  949.25  5041.4  953.85  5059.3  958.71  5086.6   962.8  5090.4   963.5
#Mann= 4 ,-1 , 0
    4804     .11       0  4906.3     .14       0  4994.6     .05       0
  5005.4     .14       0
Bank Sta=4994.6,5005.4
Exp/Cntr=0.3,0.1

Type RM Length L Ch R = 1 ,85551   ,436,436,436
BEGIN DESCRIPTION:
North Deep Creek 255.0
END DESCRIPTION:
XS GIS Cut Line= 5
      1490525.29       890245.19      1490631.47       890234.21
      1490719.31       890193.95      1490821.79       890087.81
      1490902.33       889992.62
#Sta/Elev= 30
  4815.1  967.97  4830.5  966.14  4853.1  962.41  4865.3  960.71  4877.5  958.29
  4881.2  957.81    4891  955.91    4906   953.5    4916  952.72  4935.5  950.35
  4959.5  948.48  4991.5  946.82  4993.5  946.41  4994.6  943.33  4996.1  940.33
  5003.9  940.33  5005.4  943.33  5018.5   946.6    5020  946.64  5066.9  947.44
  5096.5   946.3  5139.3  947.28  5157.7  947.26  5166.4  946.78  5196.3  950.44
  5216.3   957.7  5238.3  963.28  5254.2  966.15  5272.7  967.94  5290.7  971.28
#Mann= 4 ,-1 , 0
  4815.1     .11       0  4959.5     .14       0  4994.6     .05       0
  5005.4     .14       0
#XS Ineff= 2 , 0
       0                  5113.9       0  957.91
Permanent Ineff=
       F       F
Bank Sta=4994.6,5005.4
Exp/Cntr=0.3,0.1

Type RM Length L Ch R = 1 ,85115   ,193,193,193
BEGIN DESCRIPTION:
North Deep Creek 254.0
END DESCRIPTION:
XS GIS Cut Line= 3
      1490912.29        890591.6      1491015.46       890325.08
      1491063.35       890029.22
#Sta/Elev= 30
  4914.4  970.95    4954   958.4  4977.2  948.13  4988.5  942.16  4989.6  943.18
  4994.6  942.11  4996.1  939.11  5003.9  939.11  5005.4  942.11  5005.6  942.68
  5022.6  941.44  5052.8  941.31  5141.1  944.48  5167.9  946.81  5216.3  949.62
  5257.2  944.99  5265.2   944.9  5284.5  943.53  5302.3  943.67  5341.1  945.12
  5347.6   945.8  5365.7  949.79  5378.4  951.24  5399.9   956.7    5404   956.6
  5439.2  962.68  5453.4  966.38  5476.3  966.89  5490.6  968.31  5499.9  970.13
#Mann= 3 ,-1 , 0
  4914.4     .14       0  4994.6    .045       0  5005.4     .14       0
#XS Ineff= 2 , 0
       0                    5221       0   959.2
Permanent Ineff=
       F       F
Bank Sta=4994.6,5005.4
Exp/Cntr=0.3,0.1

Type RM Length L Ch R = 1 ,84922   ,203,203,203
BEGIN DESCRIPTION:
North Deep Creek 253.0
END DESCRIPTION:
XS GIS Cut Line= 4
      1491191.45       890581.91      1491110.93       890442.83
      1491088.97       890208.59      1491110.92       890087.85
#Sta/Elev= 30
  4833.6  971.88  4859.2  968.63  4872.3  965.81  4893.6  961.85  4913.6  957.87
  4930.9  953.69  4984.3  942.47  4994.3  941.72  4994.6  940.66  4996.1  937.66
  5003.9  937.66  5005.4  940.66  5022.3  940.24  5055.4  942.95  5095.5  942.72
  5108.5  941.93  5132.9  942.98  5170.2  943.12  5189.3  941.84  5229.6  945.44
  5249.3  947.36  5258.5  948.74  5270.5  949.61  5275.3  950.35  5290.9   951.7
  5300.5  954.23  5310.6  955.97  5323.3  958.67  5336.3  960.76  5352.3  962.87
#Mann= 4 ,-1 , 0
  4833.6     .07       0  4893.6     .14       0  4994.6     .05       0
  5005.4     .14       0
#XS Ineff= 2 , 0
       0                  5117.5       0  955.89
Permanent Ineff=
       F       F
Bank Sta=4994.6,5005.4
Exp/Cntr=0.3,0.1

Type RM Length L Ch R = 1 ,84719   ,219,219,219
BEGIN DESCRIPTION:
North Deep Creek 252.0
END DESCRIPTION:
XS GIS Cut Line= 5
      1491334.19       890475.81       1491304.9        890367.8
      1491270.13        890331.2      1491271.96       890193.95
      1491290.26       890113.45
#Sta/Elev= 30
  4867.7  961.66  4871.8  961.12  4919.2  954.18  4923.7  953.35  4928.7  952.09
  4937.2  949.58  4950.9   947.6  4971.4  943.67  4981.1  942.15  4982.1     942
  4993.8  942.46  4994.6  937.13  4996.1  934.13  5003.9  934.13  5005.4  937.13
  5008.2  942.81  5012.4  943.08  5028.4  942.44  5035.6  942.34  5039.4  942.76
  5049.9  942.68  5063.5  941.14  5111.9  940.13  5124.1  941.15  5147.1  941.67
  5159.7  942.78  5186.9  948.73  5203.3  950.51  5230.8  956.65  5249.9  960.62
#Mann= 4 ,-1 , 0
  4867.7     .07       0  4871.8     .14       0  4994.6     .05       0
  5005.4     .14       0
#XS Ineff= 2 , 0
       0                    5142       0   950.8
Permanent Ineff=
       F       F
Bank Sta=4994.6,5005.4
Exp/Cntr=0.3,0.1

Type RM Length L Ch R = 1 ,84500   ,142,142,142
BEGIN DESCRIPTION:
North Deep Creek 251.0
END DESCRIPTION:
XS GIS Cut Line= 4
      1491390.92        890479.4       1491414.7       890375.12
       1491414.7       890199.44      1491378.11       890120.77
#Sta/Elev= 30
  4708.9  961.93  4716.6  961.09  4739.6  957.51  4752.5  955.16  4764.2  952.53
  4803.5  944.12  4809.4  942.44  4818.8  941.71  4822.7  941.02  4827.2  941.16
    4865  940.77  4877.6  940.14  4883.3  940.18  4897.9  940.82  4908.1  940.51
  4918.8  940.39  4949.1  940.84  4993.5  939.14  4994.6  936.57  4996.1  933.57
  5003.9  933.57  5005.4  936.57  5007.9  936.57  5009.4  938.68  5013.6   941.7
  5030.1  954.97  5034.9  957.75  5051.2  960.71  5060.6  961.75  5078.3  964.44
#Mann= 4 ,-1 , 0
  4708.9     .07       0  4716.6     .14       0  4994.6     .05       0
  5005.4     .14       0
Bank Sta=4994.6,5005.4
Exp/Cntr=0.3,0.1

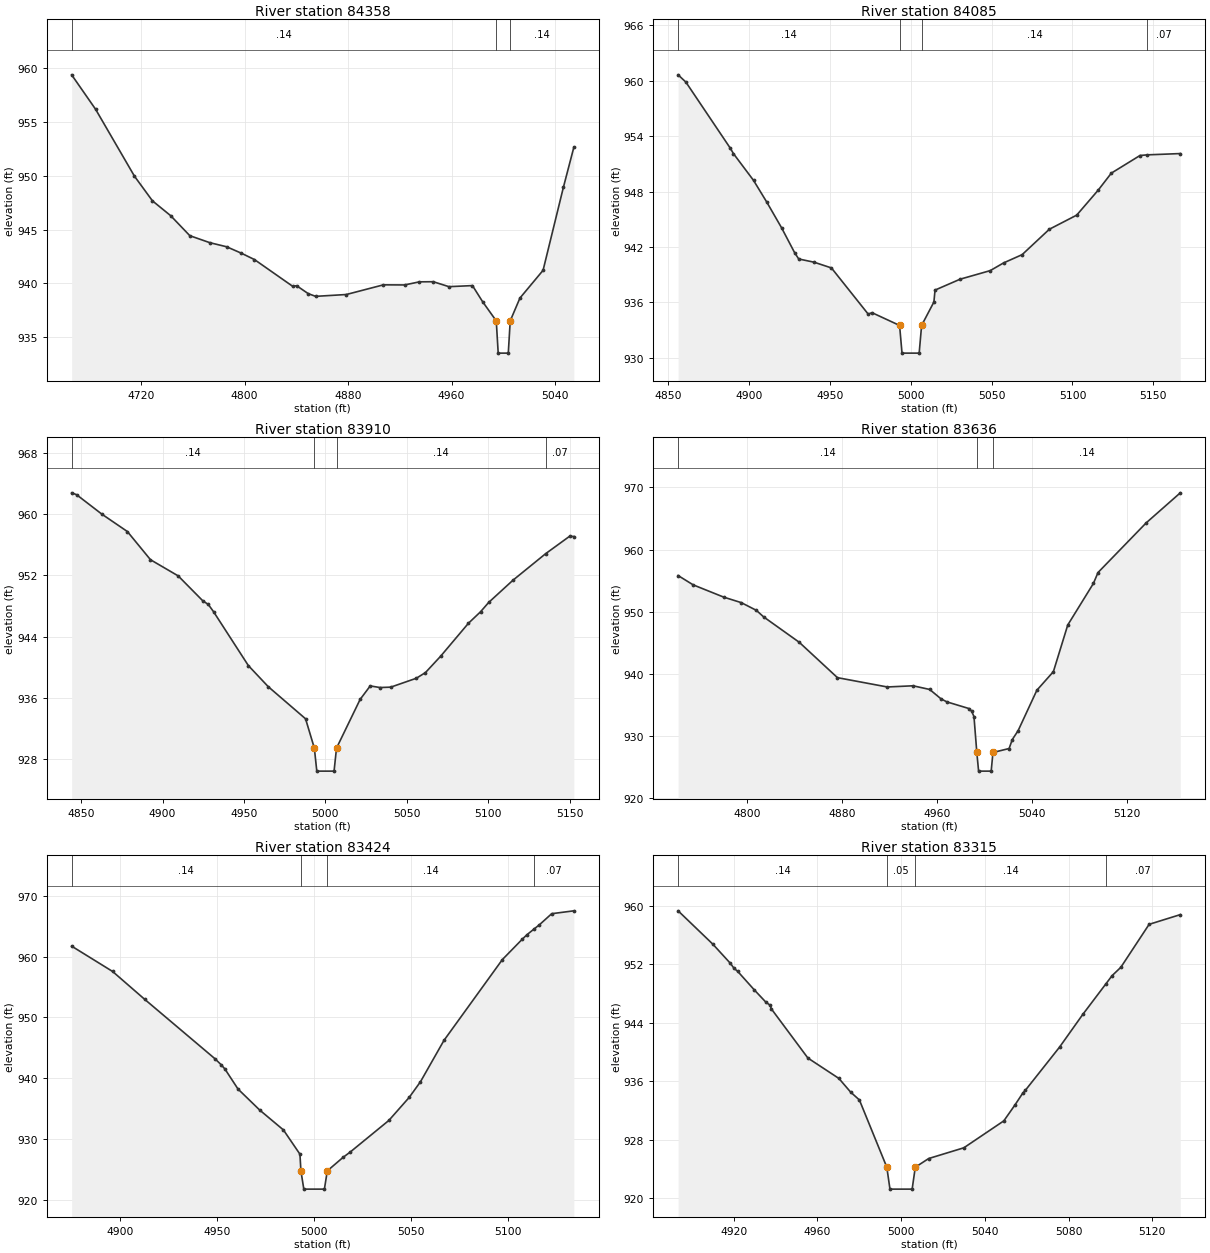
Type RM Length L Ch R = 1 ,84358   ,273,273,273
BEGIN DESCRIPTION:
North Deep Creek 250.0
END DESCRIPTION:
XS GIS Cut Line= 4
      1491548.29       890506.89      1491566.59       890336.69
      1491559.27       890190.29      1491517.18       890133.56
#Sta/Elev= 30
  4666.2  959.39  4684.7  956.19  4714.8  949.96  4728.7  947.67  4742.8  946.29
  4757.6  944.43  4773.1  943.78  4786.1   943.4  4797.5   942.8  4807.6  942.21
  4837.2  939.72  4840.2  939.78  4849.2  939.04  4854.9  938.79  4878.6  938.96
  4907.3  939.86  4923.7  939.85  4935.2  940.14  4945.9  940.15    4958  939.69
  4976.2  939.79    4984   938.3  4994.6  936.51  4996.1  933.51  5003.9  933.51
  5005.4  936.51  5012.9  938.63  5030.8  941.21  5046.5  948.92  5054.6  952.65
#Mann= 3 ,-1 , 0
  4666.2     .14       0  4994.6     .05       0  5005.4     .14       0
Bank Sta=4994.6,5005.4
Exp/Cntr=0.3,0.1

Type RM Length L Ch R = 1 ,84085   ,175,175,175
BEGIN DESCRIPTION:
North Deep Creek 249.0
END DESCRIPTION:
XS GIS Cut Line= 4
      1491675.22       890505.63      1491685.97       890386.32
      1491708.53       890299.29      1491783.76       890232.66
#Sta/Elev= 30
  4856.4  960.65  4861.2  959.86  4888.6  952.71  4890.6  952.11    4903  949.21
  4911.1  946.88  4920.3  944.08  4928.4  941.37  4930.9   940.7  4940.4  940.35
  4951.1  939.73  4973.8  934.73  4976.2  934.88  4993.2   933.5  4994.7   930.5
  5005.3   930.5  5006.8   933.5  5014.4  936.04  5015.1  937.33  5030.6  938.51
  5049.2  939.44  5057.4  940.27  5068.9  941.17  5085.7  943.92  5102.6  945.45
  5115.9  948.16    5124     950  5141.7  951.91  5146.2  951.98  5166.6  952.12
#Mann= 4 ,-1 , 0
  4856.4     .14       0  4993.2     .05       0  5006.8     .14       0
  5146.2     .07       0
Bank Sta=4993.2,5006.8
Exp/Cntr=0.3,0.1

Type RM Length L Ch R = 1 ,83910   ,274,274,274
BEGIN DESCRIPTION:
North Deep Creek 248.0
END DESCRIPTION:
XS GIS Cut Line= 3
      1491764.63       890556.98      1491836.53       890460.07
      1491870.92       890275.61
#Sta/Elev= 30
  4844.2  962.76  4847.2  962.52  4862.8  959.97  4878.4  957.71  4892.6  954.03
  4909.6  951.92  4924.7  948.67  4928.1  948.19  4931.3  947.25  4952.7  940.21
  4964.9  937.46  4987.8  933.27  4993.2  929.44  4994.7  926.44  5005.3  926.44
  5006.8  929.44  5021.3   935.8  5027.5  937.56  5033.5  937.35  5040.1   937.4
  5055.8  938.56  5061.4   939.3  5070.7  941.43  5087.8  945.74  5095.2  947.23
  5100.2  948.45  5115.1  951.35  5135.2  954.82  5149.9  957.09  5152.5  957.06
#Mann= 4 ,-1 , 0
  4844.2     .14       0  4993.2     .05       0  5006.8     .14       0
  5135.2     .07       0
Bank Sta=4993.2,5006.8
Exp/Cntr=0.3,0.1

Type RM Length L Ch R = 1 ,83636   ,212,212,212
BEGIN DESCRIPTION:
North Deep Creek 247.0
END DESCRIPTION:
XS GIS Cut Line= 4
      1491917.81       890694.48      1491964.68       890603.86
      1492074.08       890516.34      1492245.99       890460.08
#Sta/Elev= 30
  4741.6  955.81  4754.3  954.31  4780.1  952.33  4794.8  951.45  4807.5  950.21
  4813.6  949.16  4843.6  945.07  4875.8  939.37  4917.8  937.87  4939.5  938.06
  4953.5  937.47  4963.1  935.95    4968  935.47  4986.7  934.39  4988.8  933.98
  4990.8  933.11  4993.2  927.32  4994.7  924.32  5005.3  924.32  5006.8  927.32
  5020.4  927.96  5023.1  929.41    5028  930.84  5043.8  937.35  5057.7  940.34
  5069.8  947.85  5091.4  954.54  5095.3   956.3  5135.9   964.3  5164.6  969.13
#Mann= 3 ,-1 , 0
  4741.6     .14       0  4993.2     .05       0  5006.8     .14       0
Bank Sta=4993.2,5006.8
Exp/Cntr=0.3,0.1

Type RM Length L Ch R = 1 ,83424   ,109,109,109
BEGIN DESCRIPTION:
North Deep Creek 246.0
END DESCRIPTION:
XS GIS Cut Line= 4
      1491945.97       890753.87      1492024.07       890716.39
      1492077.21       890716.39      1492195.97       890710.13
#Sta/Elev= 27
  4875.1  961.71  4896.2  957.55  4912.7  952.98  4948.8  943.25  4952.1  942.24
  4954.1  941.51  4960.8  938.24    4972  934.78  4984.2  931.52  4992.7  927.54
  4993.2   924.8  4994.7   921.8  5005.3   921.8  5006.8   924.8  5014.9  927.01
  5018.6  927.89  5038.5  933.08    5049  936.87  5054.8  939.44  5066.9  946.23
    5097  959.51  5107.3  962.87  5109.7   963.6  5113.1  964.47  5116.1  965.23
  5122.4  967.04  5133.8  967.51
#Mann= 4 ,-1 , 0
  4875.1     .14       0  4993.2     .05       0  5006.8     .14       0
  5113.1     .07       0
Bank Sta=4993.2,5006.8
Exp/Cntr=0.3,0.1

Type RM Length L Ch R = 1 ,83315   ,394,394,394
BEGIN DESCRIPTION:
North Deep Creek 245.0
END DESCRIPTION:
XS GIS Cut Line= 3
      1491977.14       890860.19      1492089.71       890819.54
      1492208.46       890800.79
#Sta/Elev= 30
  4893.5  959.33  4910.1  954.76  4918.5  952.13  4920.2  951.46  4921.9  951.06
  4929.9   948.5  4935.5   946.8  4937.5   946.4    4938  945.92  4955.5  939.17
  4970.3  936.38  4975.9  934.51  4980.1  933.43  4993.2  924.22  4994.7  921.22
  5005.3  921.22  5006.8  924.22  5013.2  925.41    5030  926.88  5049.1  930.57
  5054.4  932.74  5058.2  934.39  5059.4  934.76  5075.7  940.66  5086.8  945.14
  5097.7  949.27  5100.8  950.45    5105   951.6  5118.5  957.48  5133.4  958.81
#Mann= 4 ,-1 , 0
  4893.5     .14       0  4993.2     .05       0  5006.8     .14       0
  5097.7     .07       0
Bank Sta=4993.2,5006.8
Exp/Cntr=0.3,0.1

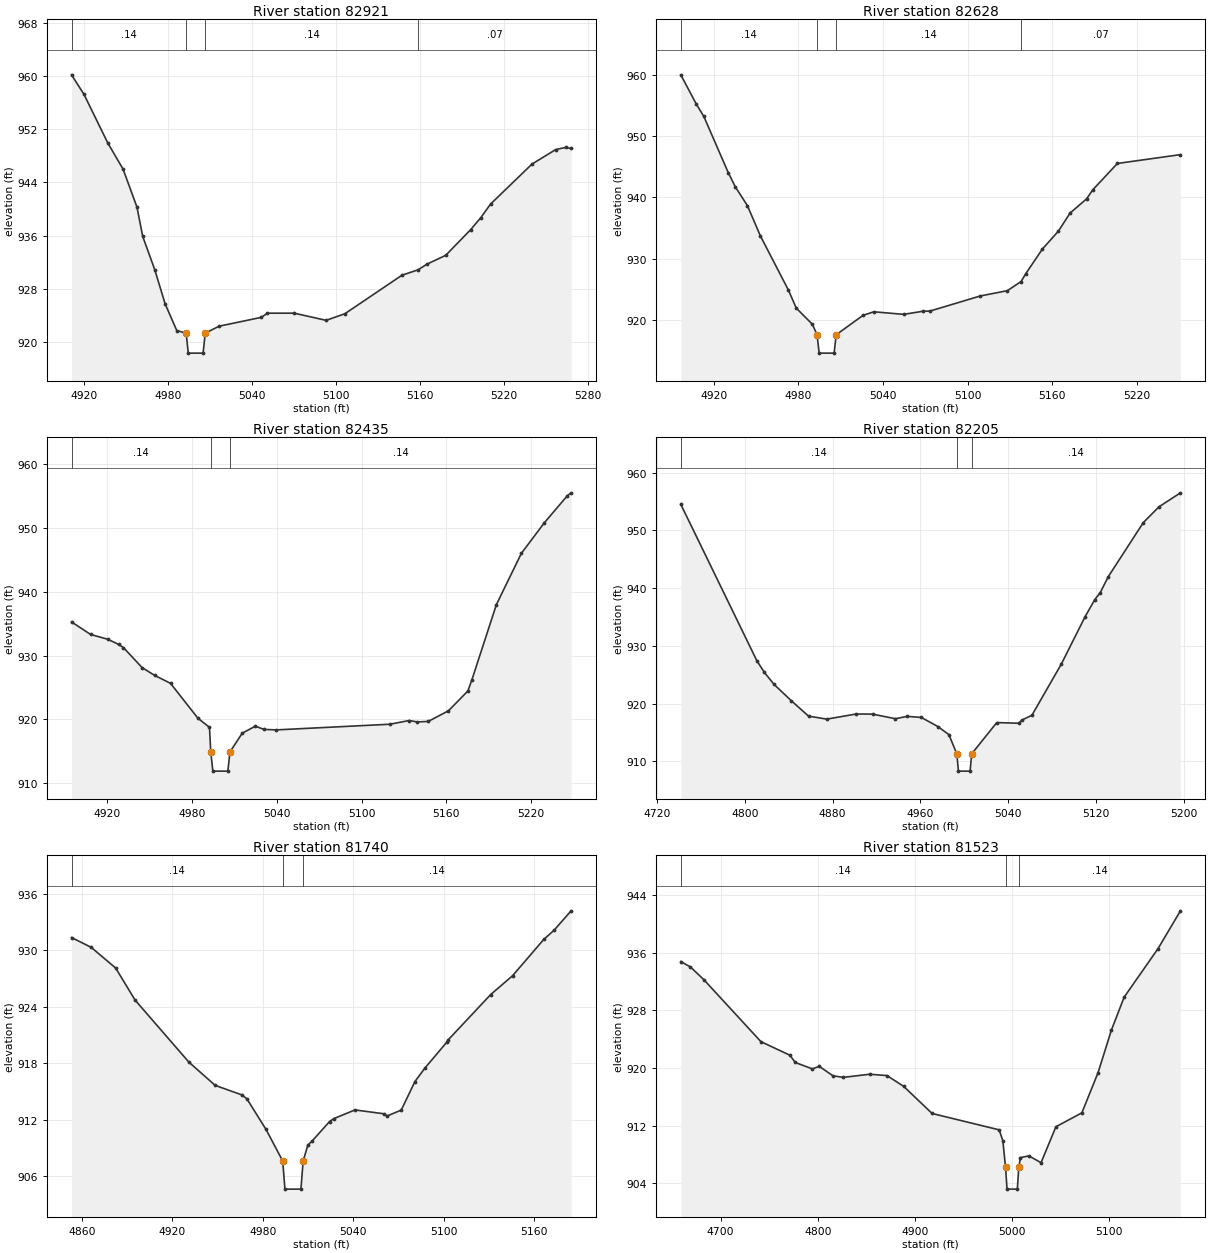
Type RM Length L Ch R = 1 ,82921   ,293,293,293
BEGIN DESCRIPTION:
North Deep Creek 243.0
END DESCRIPTION:
XS GIS Cut Line= 4
      1492099.08       891263.41      1492133.47       891194.63
      1492249.12       891103.98      1492342.93       891010.18
#Sta/Elev= 30
  4911.4  960.19  4920.3  957.25  4937.3  949.93  4948.2     946  4958.1  940.29
  4962.2  935.89  4970.8  930.87  4978.2  925.74  4986.5  921.73  4993.2  921.33
  4994.7  918.33  5005.3  918.33  5006.8  921.33  5016.7  922.38  5046.8  923.71
  5051.2  924.34  5070.3  924.34  5093.1  923.26  5106.5  924.26  5147.2  930.05
  5158.7  930.86    5165  931.71  5178.4  933.04  5196.1  936.88  5203.5  938.72
  5210.4  940.75    5240  946.77  5256.9  948.95  5263.9  949.26  5267.9  949.12
#Mann= 4 ,-1 , 0
  4911.4     .14       0  4993.2     .05       0  5006.8     .14       0
  5158.7     .07       0
Bank Sta=4993.2,5006.8
Exp/Cntr=0.3,0.1

Type RM Length L Ch R = 1 ,82628   ,193,193,193
BEGIN DESCRIPTION:
North Deep Creek 242.0
END DESCRIPTION:
XS GIS Cut Line= 4
      1492377.27        891382.2      1492417.92       891285.27
       1492439.8         891179.       1492439.8        891038.3
#Sta/Elev= 30
  4896.6  959.99  4907.5  955.24  4912.9   953.2  4930.2  944.04  4935.2  941.72
  4943.8  938.64    4953   933.7  4972.9  924.84  4978.5  921.89  4989.9  919.26
  4993.2  917.55  4994.7  914.55  5005.3  914.55  5006.8  917.55  5025.8  920.72
  5033.5   921.3  5054.6  920.88  5068.1  921.38  5073.3  921.42  5109.1  923.89
  5128.2  924.75  5137.9  926.24  5141.3  927.55    5153  931.54  5164.4  934.48
  5172.6  937.41  5184.3  939.73  5188.8  941.23  5206.2  945.52  5250.9  946.96
#Mann= 4 ,-1 , 0
  4896.6     .14       0  4993.2     .05       0  5006.8     .14       0
  5137.9     .07       0
Bank Sta=4993.2,5006.8
Exp/Cntr=0.3,0.1

Type RM Length L Ch R = 1 ,82435   ,230,230,230
BEGIN DESCRIPTION:
North Deep Creek 241.5
END DESCRIPTION:
XS GIS Cut Line= 4
      1492550.68       891440.93      1492592.87       891365.91
      1492653.83       891199.45      1492700.72       891122.09
#Sta/Elev= 30
  4894.6  935.27  4908.1  933.31  4920.3  932.55    4928  931.74  4931.4  931.24
  4944.6  928.11  4953.4   926.9  4964.7  925.65  4984.1  920.18  4992.3  918.75
  4993.2  914.89  4994.7  911.89  5005.3  911.89  5006.8  914.89  5015.5  917.84
  5024.8  918.93  5030.9  918.43  5039.5  918.35  5120.1  919.24  5133.7  919.82
  5139.4   919.6  5147.2  919.68  5161.5  921.34  5175.3  924.45  5178.1  926.18
  5195.5     938  5213.2  946.03  5229.4   950.8  5245.7  955.04  5248.4   955.5
#Mann= 3 ,-1 , 0
  4894.6     .14       0  4993.2     .05       0  5006.8     .14       0
Bank Sta=4993.2,5006.8
Exp/Cntr=0.3,0.1

Type RM Length L Ch R = 1 ,82205   ,465,465,465
BEGIN DESCRIPTION:
North Deep Creek 241.0
END DESCRIPTION:
XS GIS Cut Line= 4
      1492730.51       891588.43      1492827.39       891369.67
      1492827.39       891282.15      1492818.01       891153.97
#Sta/Elev= 30
  4741.7  954.52  4810.9  927.46  4817.8  925.41  4826.6  923.34  4842.3  920.51
  4858.1  917.83  4874.7  917.31  4901.6   918.2  4916.4  918.18  4937.3  917.38
    4948  917.79  4960.9   917.6  4975.9  916.03    4986  914.62  4993.2   911.3
  4994.7   908.3  5005.3   908.3  5006.8   911.3  5029.6  916.71  5049.5   916.6
  5052.8  917.18  5061.6  917.96  5088.4  926.83    5110  935.01  5118.9  938.01
  5123.8  939.19  5131.3  942.01  5163.2  951.37  5177.4  954.09    5197  956.52
#Mann= 3 ,-1 , 0
  4741.7     .14       0  4993.2     .05       0  5006.8     .14       0
Bank Sta=4993.2,5006.8
Exp/Cntr=0.3,0.1

Type RM Length L Ch R = 1 ,81740   ,217,217,217
BEGIN DESCRIPTION:
North Deep Creek 239.0
END DESCRIPTION:
XS GIS Cut Line= 3
      1493164.96       891669.75      1493246.24       891532.21
      1493249.36       891360.29
#Sta/Elev= 30
    4853  931.38  4866.1  930.33  4882.3  928.13  4895.2  924.72  4930.9  918.12
  4948.4  915.64  4965.9  914.64  4969.4  914.22  4982.1  910.96  4993.2   907.6
  4994.7   904.6  5005.3   904.6  5006.8   907.6  5009.9  909.28  5012.8  909.73
  5024.3  911.79  5027.1   912.1  5041.2  913.03  5060.4  912.62  5062.6  912.39
  5071.9  913.01    5081  916.05  5087.7   917.5    5102  920.21  5103.1  920.49
  5131.3  925.31  5145.8  927.31  5166.5  931.17  5173.4  932.16  5184.7  934.22
#Mann= 3 ,-1 , 0
    4853     .14       0  4993.2     .05       0  5006.8     .14       0
Bank Sta=4993.2,5006.8
Exp/Cntr=0.3,0.1

Type RM Length L Ch R = 1 ,81523   ,224,224,224
BEGIN DESCRIPTION:
North Deep Creek 238.0
END DESCRIPTION:
XS GIS Cut Line= 5
      1493293.12       891822.92      1493346.26       891694.74
      1493402.53       891647.86      1493424.41       891466.57
      1493411.91       891347.83
#Sta/Elev= 30
  4659.1  934.74  4668.9  934.01  4682.8  932.23  4741.5  923.64  4771.4  921.75
  4776.8  920.75  4794.5  919.86  4801.5  920.22  4815.7   918.9  4826.4  918.69
  4853.4  919.12  4871.1  918.94  4888.3  917.45  4917.6  913.68  4986.6  911.41
  4990.4   909.9  4993.2  906.19  4994.7  903.19  5005.3  903.19  5006.8  906.19
  5008.5  907.56  5017.1   907.8  5029.7  906.86    5045  911.84  5071.7  913.77
  5088.3  919.32  5102.1  925.25  5115.2  929.81  5150.1  936.55  5173.1  941.78
#Mann= 3 ,-1 , 0
  4659.1     .14       0  4993.2     .05       0  5006.8     .14       0
Bank Sta=4993.2,5006.8
Exp/Cntr=0.3,0.1

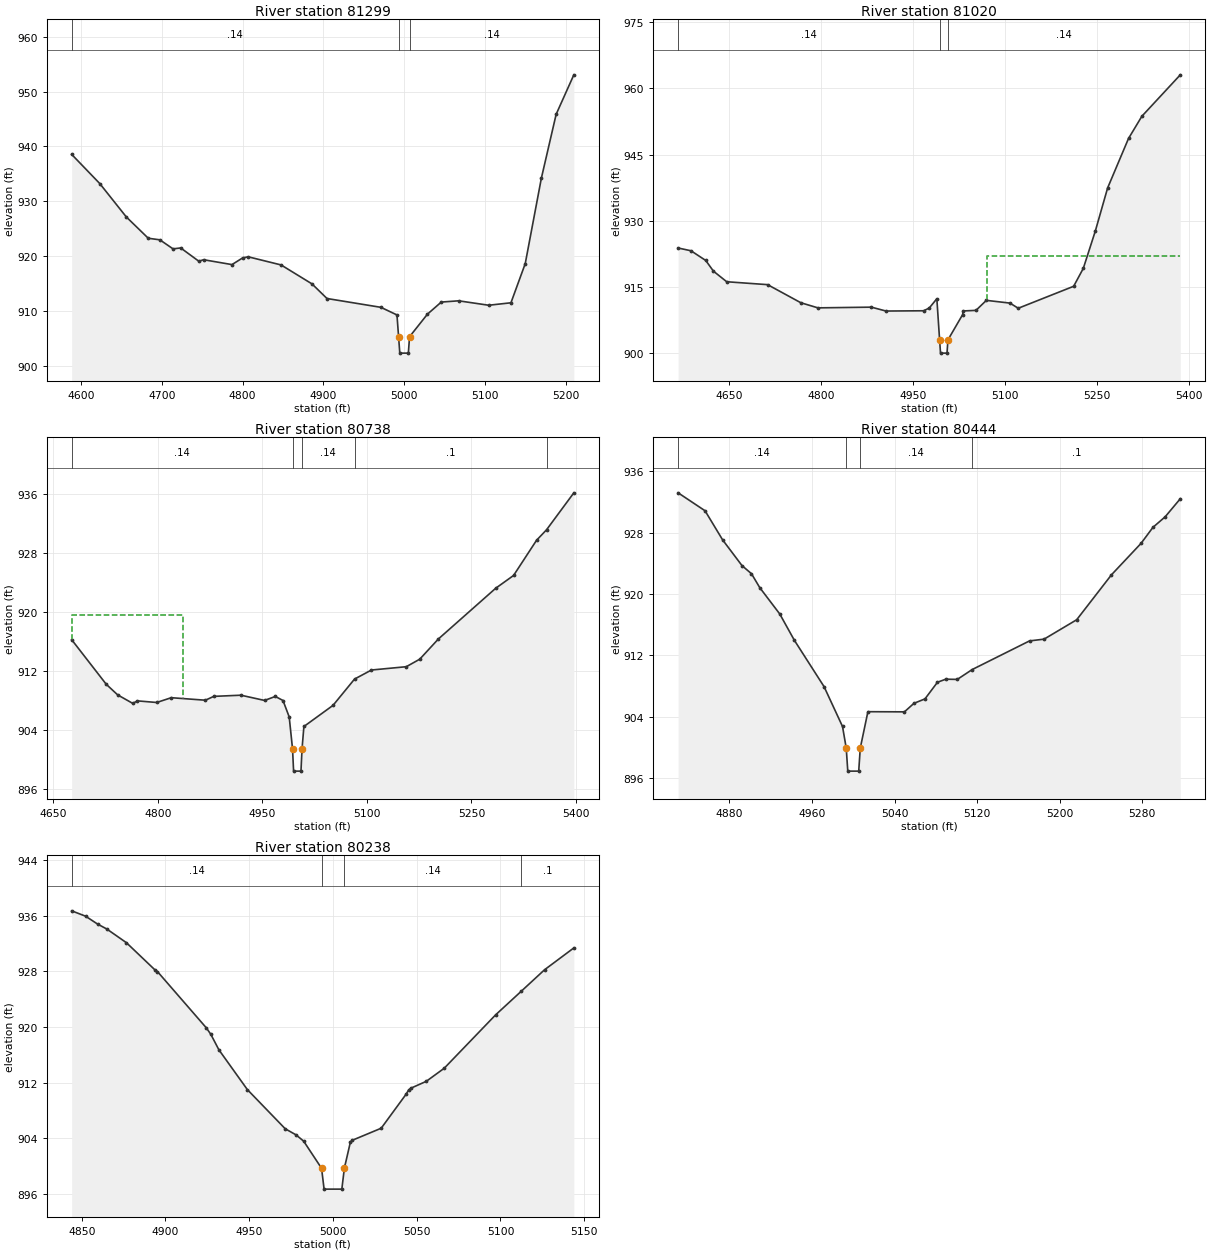
Type RM Length L Ch R = 1 ,81299   ,279,279,279
BEGIN DESCRIPTION:
North Deep Creek 237.0
END DESCRIPTION:
XS GIS Cut Line= 4
      1493280.62       891857.28      1493540.06       891679.12
      1493643.21       891569.71      1493733.88       891441.53
#Sta/Elev= 30
  4588.2  938.55  4623.1  933.21  4655.9  927.13  4683.1  923.24  4697.5  922.95
  4713.8   921.3  4723.3  921.47  4745.7  919.05  4751.7  919.32  4786.8  918.43
    4800  919.65    4807  919.85  4847.6  918.37  4885.9  914.91  4904.5  912.24
  4971.3  910.63  4991.2  909.24  4993.2  905.27  4994.7  902.27  5005.3  902.27
  5006.8  905.27    5029  909.39  5046.1  911.59  5067.6  911.82  5104.8  911.01
  5132.4  911.46  5150.1  918.61  5170.1  934.22  5188.4  945.87  5210.3  953.07
#Mann= 3 ,-1 , 0
  4588.2     .14       0  4993.2     .05       0  5006.8     .14       0
Bank Sta=4993.2,5006.8
Exp/Cntr=0.3,0.1

Type RM Length L Ch R = 1 ,81020   ,282,282,282
BEGIN DESCRIPTION:
North Deep Creek 236.0
END DESCRIPTION:
XS GIS Cut Line= 5
      1493386.87       891854.16      1493665.09       891788.52
      1493843.26       891788.52      1493952.66       891669.74
      1494012.06       891485.28
#Sta/Elev= 30
  4566.6  923.81  4587.6  923.18  4611.7  920.98  4624.2  918.56  4645.9  916.16
  4712.6   915.5  4766.8   911.4  4794.7  910.24  4881.9   910.4  4905.8  909.52
  4967.1  909.58  4976.3   910.2  4988.7  912.31  4993.2  902.98  4994.7  899.98
  5005.3  899.98  5006.8  902.98  5030.6  908.67    5032  909.54  5052.5  909.67
  5069.5  911.94    5108  911.32  5121.5  910.15  5211.9  915.13  5227.7  919.21
  5247.3  927.67  5267.3  937.41  5301.4  948.63  5323.2  953.67  5385.9  963.06
#Mann= 3 ,-1 , 0
  4566.6     .14       0  4993.2     .05       0  5006.8     .14       0
#XS Ineff= 2 , 0
       0                  5070.2       0  921.94
Permanent Ineff=
       F       F
Bank Sta=4993.2,5006.8
Exp/Cntr=0.3,0.1

Type RM Length L Ch R = 1 ,80738   ,294,294,294
BEGIN DESCRIPTION:
North Deep Creek 234.0
END DESCRIPTION:
XS GIS Cut Line= 4
      1493476.68       892055.18      1493708.82       892008.28
      1493861.21       892057.52      1494183.93       892085.46
#Sta/Elev= 30
  4676.1  916.25  4725.8  910.19  4742.2  908.75  4763.8   907.6  4770.6  907.94
  4798.2  907.72  4819.1  908.37  4868.1  908.03  4880.1  908.55  4919.1  908.71
    4953     908  4968.5  908.54  4979.5  907.99  4988.4  905.76  4993.2   901.4
  4994.7   898.4  5005.3   898.4  5006.8   901.4  5009.5  904.46  5051.3  907.33
  5082.2   910.9  5106.5  912.13  5156.5  912.58  5175.8   913.6  5202.6  916.35
  5284.8  923.23  5310.5  924.97  5343.5  929.75  5357.8  931.17    5397  936.19
#Mann= 5 ,-1 , 0
  4676.1     .14       0  4993.2     .05       0  5006.8     .14       0
  5082.2      .1       0  5357.8     .14       0
#XS Ineff= 2 , 0
       0  4835.9   919.6               0
Permanent Ineff=
       F       F
Bank Sta=4993.2,5006.8
Exp/Cntr=0.3,0.1

Type RM Length L Ch R = 1 ,80444   ,206,206,206
BEGIN DESCRIPTION:
North Deep Creek 233.0
END DESCRIPTION:
XS GIS Cut Line= 4
      1493852.64       892429.27      1493880.77       892263.63
      1493949.53       892185.49      1494152.71       892116.72
#Sta/Elev= 30
  4830.3  933.21  4856.4  930.87  4873.4  927.08  4892.2  923.72  4901.4  922.66
  4909.4  920.85  4928.8  917.41  4942.9  913.99  4971.7  907.94  4989.6  902.74
  4993.2  899.92  4994.7  896.92  5005.3  896.92  5006.8  899.92  5014.2  904.67
  5049.6  904.65  5058.8  905.76  5069.5  906.34  5081.6  908.51  5089.7  908.91
  5100.8  908.88  5115.3  910.17  5170.8   913.9  5184.9  914.13  5216.5  916.66
  5250.2  922.52  5278.8  926.61  5290.4  928.71  5302.2  930.08  5316.9  932.44
#Mann= 4 ,-1 , 0
  4830.3     .14       0  4993.2     .05       0  5006.8     .14       0
  5115.3      .1       0
Bank Sta=4993.2,5006.8
Exp/Cntr=0.3,0.1

Type RM Length L Ch R = 1 ,80238   ,141,141,141
BEGIN DESCRIPTION:
North Deep Creek 232.0
END DESCRIPTION:
XS GIS Cut Line= 3
      1493993.32       892476.14      1494065.18       892341.77
       1494190.2       892263.64
#Sta/Elev= 30
    4844  936.72  4852.3  935.95  4859.5  934.81    4865   934.1  4876.7  932.13
  4893.8   928.2  4895.2  927.98  4924.4  919.87  4927.1  918.93  4931.9  916.71
  4948.9  910.98  4971.5  905.34  4977.9  904.47  4982.5  903.56  4993.2  899.65
  4994.7  896.65  5005.3  896.65  5006.8  899.65  5010.4  903.42  5011.5  903.68
  5028.8  905.42  5043.7  910.33  5045.2  910.94  5046.6  911.19  5055.7  912.17
  5066.4  914.05  5097.1  921.74  5112.5  925.16  5126.3  928.23  5143.8  931.38
#Mann= 4 ,-1 , 0
    4844     .14       0  4993.2     .05       0  5006.8     .14       0
  5112.5      .1       0
Bank Sta=4993.2,5006.8
Exp/Cntr=0.3,0.1