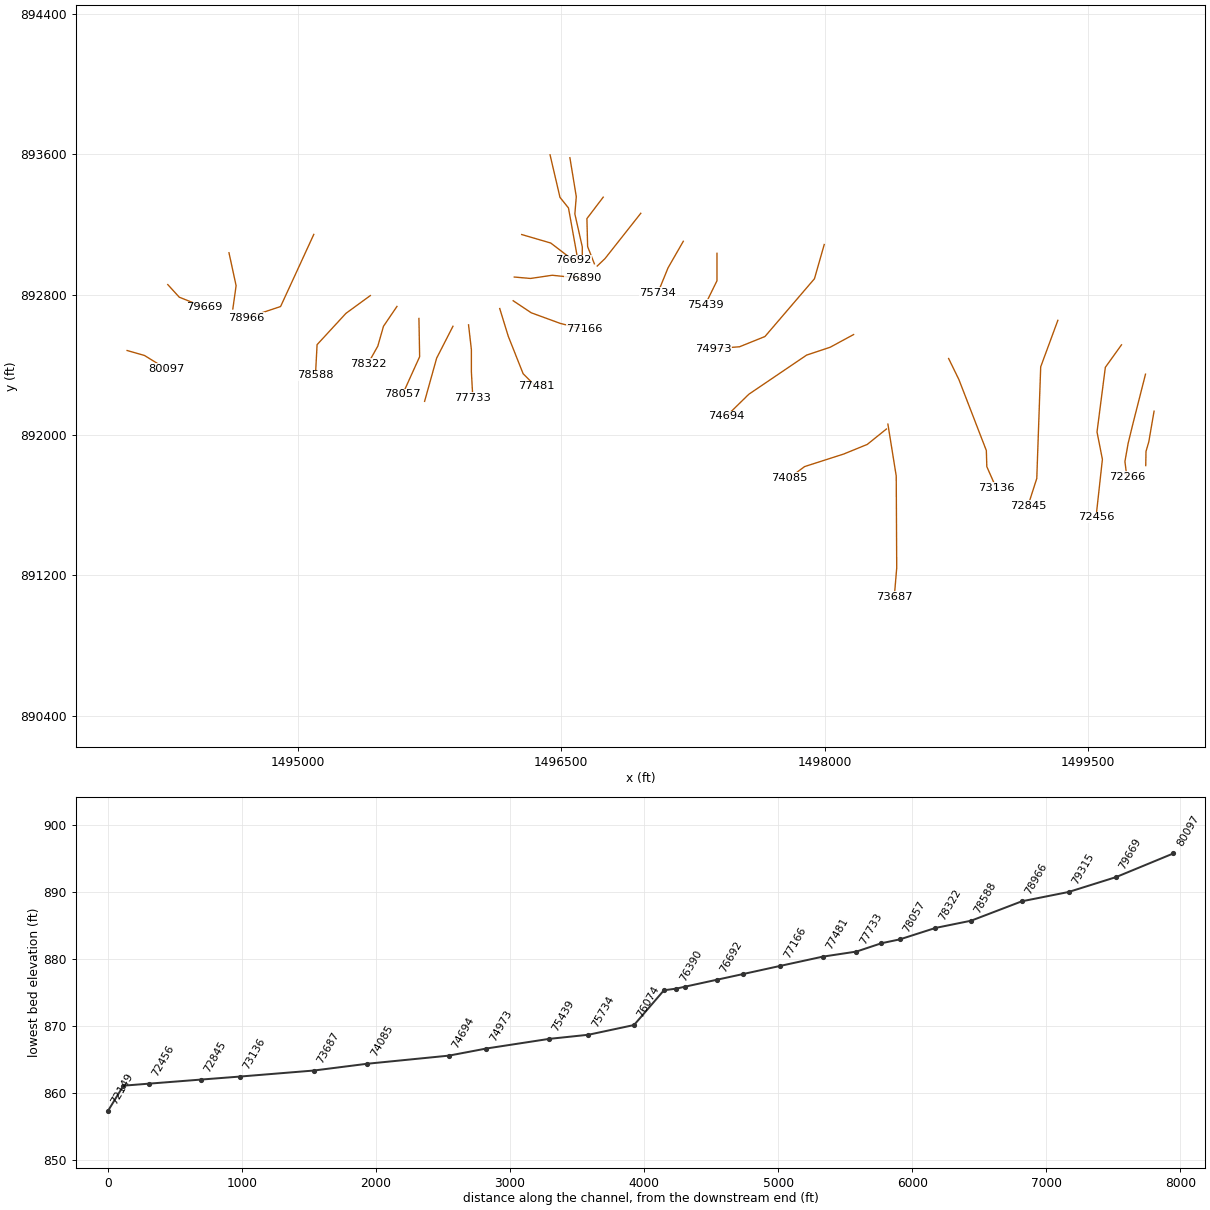
HEC-RAS study North Deep Creek.prj: North Deep Creek Limited Detail Study

--- North Deep Creek.g01 (geometry) --- (continued)

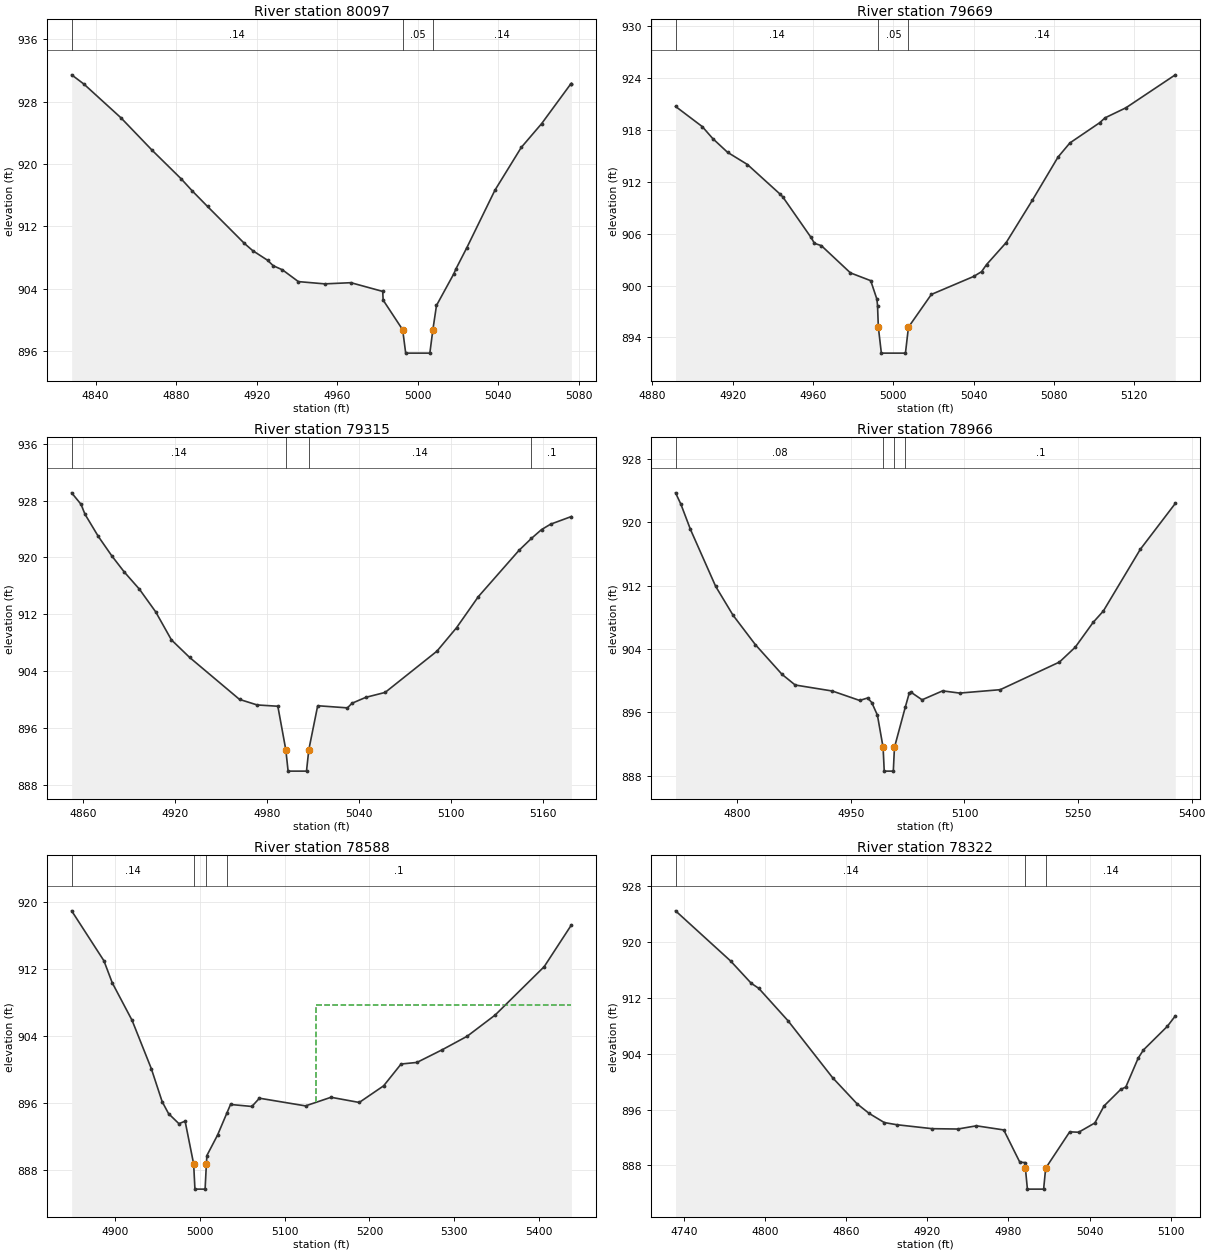
Type RM Length L Ch R = 1 ,80097   ,428,428,428
BEGIN DESCRIPTION:
North Deep Creek 231.0
END DESCRIPTION:
XS GIS Cut Line= 3
      1494027.66       892481.86      1494126.13       892453.73
      1494250.41       892377.52
#Sta/Elev= 30
  4828.1  931.44  4834.2  930.25  4852.6  925.92  4868.1  921.75  4882.5  918.09
    4888  916.54  4895.6  914.54  4913.9   909.8    4918  908.88  4925.4  907.64
  4928.2  906.94  4932.8  906.41  4940.7   904.9  4953.8  904.61  4966.8  904.76
  4982.6  903.64  4982.8  902.53  4992.5  898.72    4994  895.72    5006  895.72
  5007.5  898.72  5009.3  901.84  5017.9   905.9  5018.9   906.5  5024.4  909.27
  5038.3  916.62  5051.4  922.12  5061.5  925.17  5075.9  930.24  5076.3  930.32
#Mann= 3 ,-1 , 0
  4828.1     .14       0  4992.5     .05       0  5007.5     .14       0
Bank Sta=4992.5,5007.5
Exp/Cntr=0.3,0.1

Type RM Length L Ch R = 1 ,79669   ,354,354,354
BEGIN DESCRIPTION:
North Deep Creek 230.0
END DESCRIPTION:
XS GIS Cut Line= 3
      1494258.97       892857.54      1494324.62       892785.63
      1494465.31       892729.35
#Sta/Elev= 30
  4891.5  920.69  4904.8  918.36  4910.1  916.96  4917.4  915.39  4927.3  913.98
  4943.6  910.55  4944.9  910.24  4958.9  905.58  4960.7  904.87  4964.1  904.61
  4978.6  901.46  4988.7  900.56  4991.8  898.41  4992.1  897.67  4992.5  895.19
    4994  892.19    5006  892.19  5007.5  895.19  5018.9  898.97    5040  901.05
  5043.9   901.6  5046.4  902.42  5056.2  904.97  5069.2  909.85    5082  914.84
  5087.9  916.47  5102.7   918.8  5105.4  919.37  5115.8  920.53  5140.4  924.34
#Mann= 3 ,-1 , 0
  4891.5     .14       0  4992.5     .05       0  5007.5     .14       0
Bank Sta=4992.5,5007.5
Exp/Cntr=0.3,0.1

Type RM Length L Ch R = 1 ,79315   ,349,349,349
BEGIN DESCRIPTION:
North Deep Creek 228.0
END DESCRIPTION:
XS GIS Cut Line= 3
       1494607.5       893038.83      1494648.14       892851.27
      1494629.39        892718.5
#Sta/Elev= 30
  4852.8  929.08  4858.9  927.47  4861.5  926.07  4870.2  922.95    4879  920.22
  4887.1  917.96    4897  915.54  4907.6  912.36  4917.9  908.41  4929.8  905.94
  4962.3  900.05  4973.8  899.27  4987.3  899.09  4992.5  892.97    4994  889.97
    5006  889.97  5007.5  892.97  5013.3  899.16  5032.7  898.86  5035.7  899.51
  5044.7  900.34  5057.3  901.03  5091.1  906.83  5103.9  910.13  5118.1  914.49
  5144.6  920.99  5152.7  922.67  5159.3  923.91  5165.2  924.67  5178.8  925.75
#Mann= 4 ,-1 , 0
  4852.8     .14       0  4992.5     .05       0  5007.5     .14       0
  5152.7      .1       0
Bank Sta=4992.5,5007.5
Exp/Cntr=0.3,0.1

Type RM Length L Ch R = 1 ,78966   ,378,378,378
BEGIN DESCRIPTION:
North Deep Creek 227.0
END DESCRIPTION:
XS GIS Cut Line= 4
      1495090.42        893143.5      1494993.53       892932.54
      1494901.32       892732.49       1494704.4       892666.85
#Sta/Elev= 30
  4718.4  923.74  4725.5  922.29  4738.1  919.11  4771.4  911.92  4794.3  908.28
  4823.8  904.56  4859.1   900.8  4876.4  899.46  4925.5   898.7  4961.5  897.51
  4972.1  897.82  4977.5  897.25    4985  895.65  4992.5  891.58    4994  888.58
    5006  888.58  5007.5  891.58    5022  896.73    5027  898.43  5029.6  898.53
    5044  897.59  5071.1  898.72  5093.6  898.44  5147.2  898.87  5225.4  902.36
  5246.3  904.24  5269.8  907.36  5283.4  908.81  5332.1  916.59  5378.4   922.4
#Mann= 4 ,-1 , 0
  4718.4     .08       0  4992.5     .05       0  5007.5     .08       0
    5022      .1       0
Bank Sta=4992.5,5007.5
Exp/Cntr=0.3,0.1

Type RM Length L Ch R = 1 ,78588   ,266,266,266
BEGIN DESCRIPTION:
North Deep Creek 226.0
END DESCRIPTION:
XS GIS Cut Line= 4
      1495412.38       892795.01      1495273.29       892693.42
      1495109.19       892515.25      1495099.81       892340.17
#Sta/Elev= 30
  4848.5  918.99  4886.6  913.01  4896.4  910.38  4919.8  905.89  4942.5  900.11
  4955.3  896.16  4962.9  894.72  4975.1  893.52  4982.4  893.82  4992.5  888.69
    4994  885.69    5006  885.69  5007.5  888.69  5008.1  889.71  5020.7  892.16
  5031.9  894.84    5036  895.82  5061.2  895.58  5070.1  896.57  5124.5  895.65
  5154.6  896.68  5187.9  896.06  5216.7  898.05  5237.3  900.66    5256  900.85
  5286.1  902.38  5315.4  903.99  5348.3  906.52  5406.2  912.31  5438.3   917.3
#Mann= 4 ,-1 , 0
  4848.5     .14       0  4992.5     .05       0  5007.5     .14       0
  5031.9      .1       0
#XS Ineff= 2 , 0
       0                  5137.4       0  907.75
Permanent Ineff=
       F       F
Bank Sta=4992.5,5007.5
Exp/Cntr=0.3,0.1

Type RM Length L Ch R = 1 ,78322   ,265,265,265
BEGIN DESCRIPTION:
North Deep Creek 225.0
END DESCRIPTION:
XS GIS Cut Line= 4
      1495563.98        892733.1       1495487.3       892620.09
      1495455.01       892507.09      1495398.53       892406.23
#Sta/Elev= 30
  4733.7  924.48  4774.4   917.3  4789.7   914.1  4795.3  913.37  4816.9  908.73
  4849.9  900.57    4868  896.83  4876.9  895.46  4888.1  894.15  4897.2  893.84
  4923.6  893.27  4942.5  893.22  4956.3  893.68  4976.5  893.09  4988.4  888.46
  4992.2  888.42  4992.5  887.61    4994  884.61    5006  884.61  5007.5  887.61
  5025.3  892.82  5031.9  892.76  5043.9  894.09  5050.7  896.53    5063  898.89
  5066.8  899.24  5075.9  903.36  5079.8  904.54  5097.5  907.93  5103.4  909.42
#Mann= 3 ,-1 , 0
  4733.7     .14       0  4992.5     .05       0  5007.5     .14       0
Bank Sta=4992.5,5007.5
Exp/Cntr=0.3,0.1

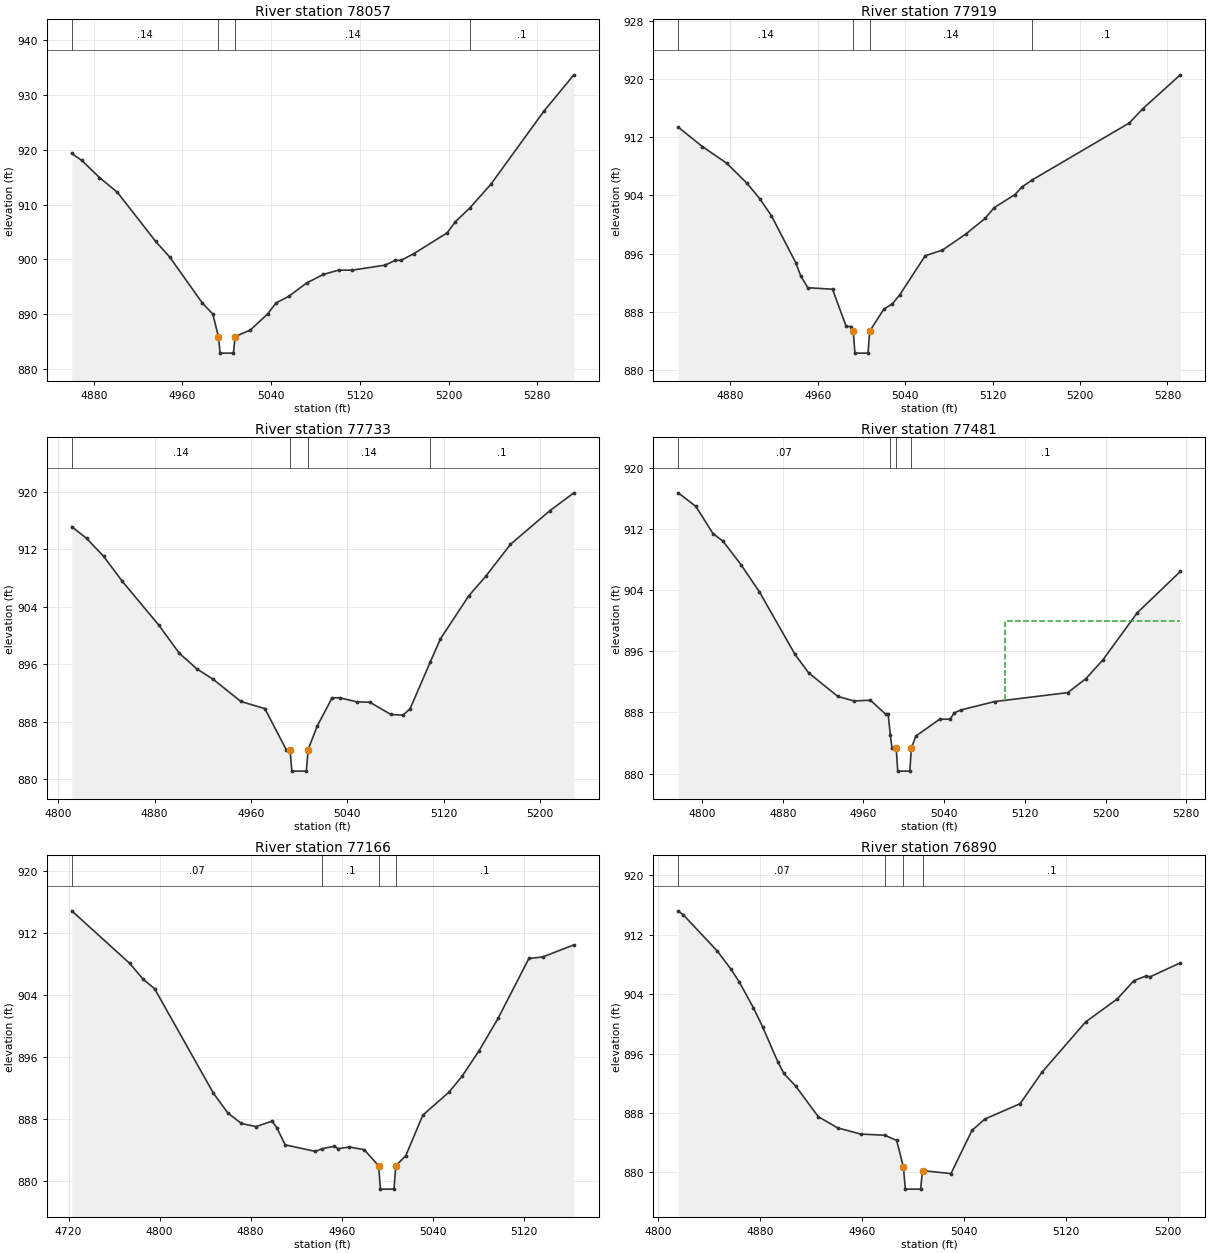
Type RM Length L Ch R = 1 ,78057   ,138,138,138
BEGIN DESCRIPTION:
North Deep Creek 224.0
END DESCRIPTION:
XS GIS Cut Line= 3
      1495689.08       892664.52      1495693.11       892446.56
      1495596.25       892232.66
#Sta/Elev= 30
  4860.2  919.34  4869.3  918.06  4885.2  914.95  4901.2  912.28  4935.9  903.29
  4948.7   900.4    4978  892.04  4987.4  890.03  4992.5  885.91    4994  882.91
    5006  882.91  5007.5  885.91  5021.3  887.14  5036.8  890.05  5044.3  892.05
  5055.9  893.28  5071.9  895.69  5086.9  897.26  5100.9  898.06  5112.7  898.04
  5142.6  898.96  5151.9  899.82  5157.1  899.85  5168.5  901.04  5198.7  904.85
  5206.1  906.89  5219.1  909.38    5238  913.68  5286.2  927.11    5313  933.69
#Mann= 4 ,-1 , 0
  4860.2     .14       0  4992.5     .05       0  5007.5     .14       0
  5219.1      .1       0
Bank Sta=4992.5,5007.5
Exp/Cntr=0.3,0.1

Type RM Length L Ch R = 1 ,77919   ,186,186,186
BEGIN DESCRIPTION:
North Deep Creek 223.0
END DESCRIPTION:
XS GIS Cut Line= 3
      1495882.78       892620.07      1495789.97       892438.49
      1495721.36        892192.3
#Sta/Elev= 30
  4832.3  913.39  4854.4  910.72  4876.5  908.45  4894.9  905.73  4906.8  903.58
  4917.5  901.23  4939.8  894.78  4944.4  892.94  4950.9  891.32  4973.5  891.11
    4986  886.01  4990.7  885.98  4992.5  885.33    4994  882.33    5006  882.33
  5007.5  885.33  5020.5  888.39  5028.2  889.09  5034.9  890.32  5058.4  895.72
  5074.1  896.49  5095.4  898.69  5113.2  900.85  5121.3  902.31  5140.3  904.11
  5147.1  905.19  5156.2  906.13  5245.2  913.97  5257.2  915.89  5291.8  920.58
#Mann= 4 ,-1 , 0
  4832.3     .14       0  4992.5     .05       0  5007.5     .14       0
  5156.2      .1       0
Bank Sta=4992.5,5007.5
Exp/Cntr=0.3,0.1

Type RM Length L Ch R = 1 ,77733   ,252,252,252
BEGIN DESCRIPTION:
North Deep Creek 222.0
END DESCRIPTION:
XS GIS Cut Line= 4
      1495971.57       892628.18      1495987.71       892486.92
      1495987.71       892361.81      1495995.78       892212.52
#Sta/Elev= 30
  4811.3  915.12  4823.6   913.5  4837.7  911.01  4853.1  907.55  4883.5  901.43
  4900.6   897.5  4915.2  895.32  4928.5   893.9  4951.7  890.79  4971.6  889.79
  4989.3  884.09  4992.5  884.09    4994  881.09    5006  881.09  5007.5  884.09
  5015.1  887.38  5027.4  891.29  5033.6  891.31  5048.1  890.73  5058.7  890.69
  5076.2  888.98  5086.2  888.88  5092.1  889.76  5108.8  896.24  5117.4  899.53
  5140.9   905.5  5155.2  908.27  5175.5  912.67  5208.3  917.37  5228.1  919.84
#Mann= 4 ,-1 , 0
  4811.3     .14       0  4992.5     .05       0  5007.5     .14       0
  5108.8      .1       0
Bank Sta=4992.5,5007.5
Exp/Cntr=0.3,0.1

Type RM Length L Ch R = 1 ,77481   ,315,315,315
BEGIN DESCRIPTION:
North Deep Creek 221.0
END DESCRIPTION:
XS GIS Cut Line= 4
      1496149.12       892721.01      1496197.56       892563.59
      1496282.31       892349.71      1496354.95       892277.06
#Sta/Elev= 30
  4776.5   916.7    4794  914.92  4810.9  911.38    4821  910.36  4838.8  907.29
  4856.9  903.77  4892.2  895.59  4905.7  893.17  4934.7  890.09  4950.7   889.5
  4966.9   889.6    4982  887.78  4984.5  887.75  4986.6  885.11  4988.3  883.33
  4992.5  883.33    4994  880.33    5006  880.33  5007.5  883.33  5011.9  884.91
  5035.5  887.11  5045.9  887.12    5050  887.94  5056.7  888.33    5090  889.42
  5162.5  890.59  5180.5  892.42  5197.4  894.89  5231.2  901.01    5274  906.42
#Mann= 4 ,-1 , 0
  4776.5     .07       0  4986.6      .1       0  4992.5     .05       0
  5007.5      .1       0
#XS Ineff= 2 , 0
       0                    5100       0     900
Permanent Ineff=
       F       F
Bank Sta=4992.5,5007.5
Exp/Cntr=0.3,0.1

Type RM Length L Ch R = 1 ,77166   ,276,276,276
BEGIN DESCRIPTION:
North Deep Creek 220.0
END DESCRIPTION:
XS GIS Cut Line= 4
      1496225.85       892765.35      1496328.72       892696.77
      1496494.18       892636.23      1496631.34       892601.94
#Sta/Elev= 30
  4722.8  914.83  4773.7  908.06  4785.3  906.05  4795.6  904.79  4847.3  891.32
  4859.9  888.78  4871.9  887.42  4884.7  887.02  4898.8  887.72  4903.1  886.85
  4910.3  884.67  4936.9  883.82  4942.9  884.17  4953.3  884.48    4957  884.17
  4966.8  884.39  4979.8  884.04  4992.5  881.96    4994  878.96    5006  878.96
  5007.5  881.96  5016.3  883.27  5031.3   888.5  5054.2  891.45  5065.7  893.49
  5080.8  896.82  5097.4  900.97  5124.5  908.69  5136.5  908.88    5164  910.44
#Mann= 4 ,-1 , 0
  4722.8     .07       0  4942.9      .1       0  4992.5     .05       0
  5007.5      .1       0
Bank Sta=4992.5,5007.5
Exp/Cntr=0.3,0.1

Type RM Length L Ch R = 1 ,76890   ,198,198,198
BEGIN DESCRIPTION:
North Deep Creek 219.0
END DESCRIPTION:
XS GIS Cut Line= 4
      1496231.89       892900.56      1496324.68       892892.49
      1496447.77       892910.65      1496623.27        892892.5
#Sta/Elev= 30
  4815.8   915.2  4819.9  914.64  4846.4   909.8    4857  907.39  4863.6  905.65
  4874.7  902.19    4882  899.59    4894  894.86  4898.7  893.31  4907.9  891.63
  4925.7   887.5  4940.8     886  4958.9  885.16  4977.9     885  4987.2   884.3
  4992.5  880.75    4994  877.75    5006  877.75  5007.5  880.24  5029.8  879.84
  5046.3  885.65  5056.4  887.18  5084.1  889.25  5101.1  893.45  5135.5  900.25
  5160.3  903.34  5173.3  905.79  5182.9  906.44  5186.1  906.32  5209.8   908.2
#Mann= 4 ,-1 , 0
  4815.8     .07       0  4977.9      .1       0  4992.5     .05       0
  5007.5      .1       0
Bank Sta=4992.5,5007.5
Exp/Cntr=0.3,0.1

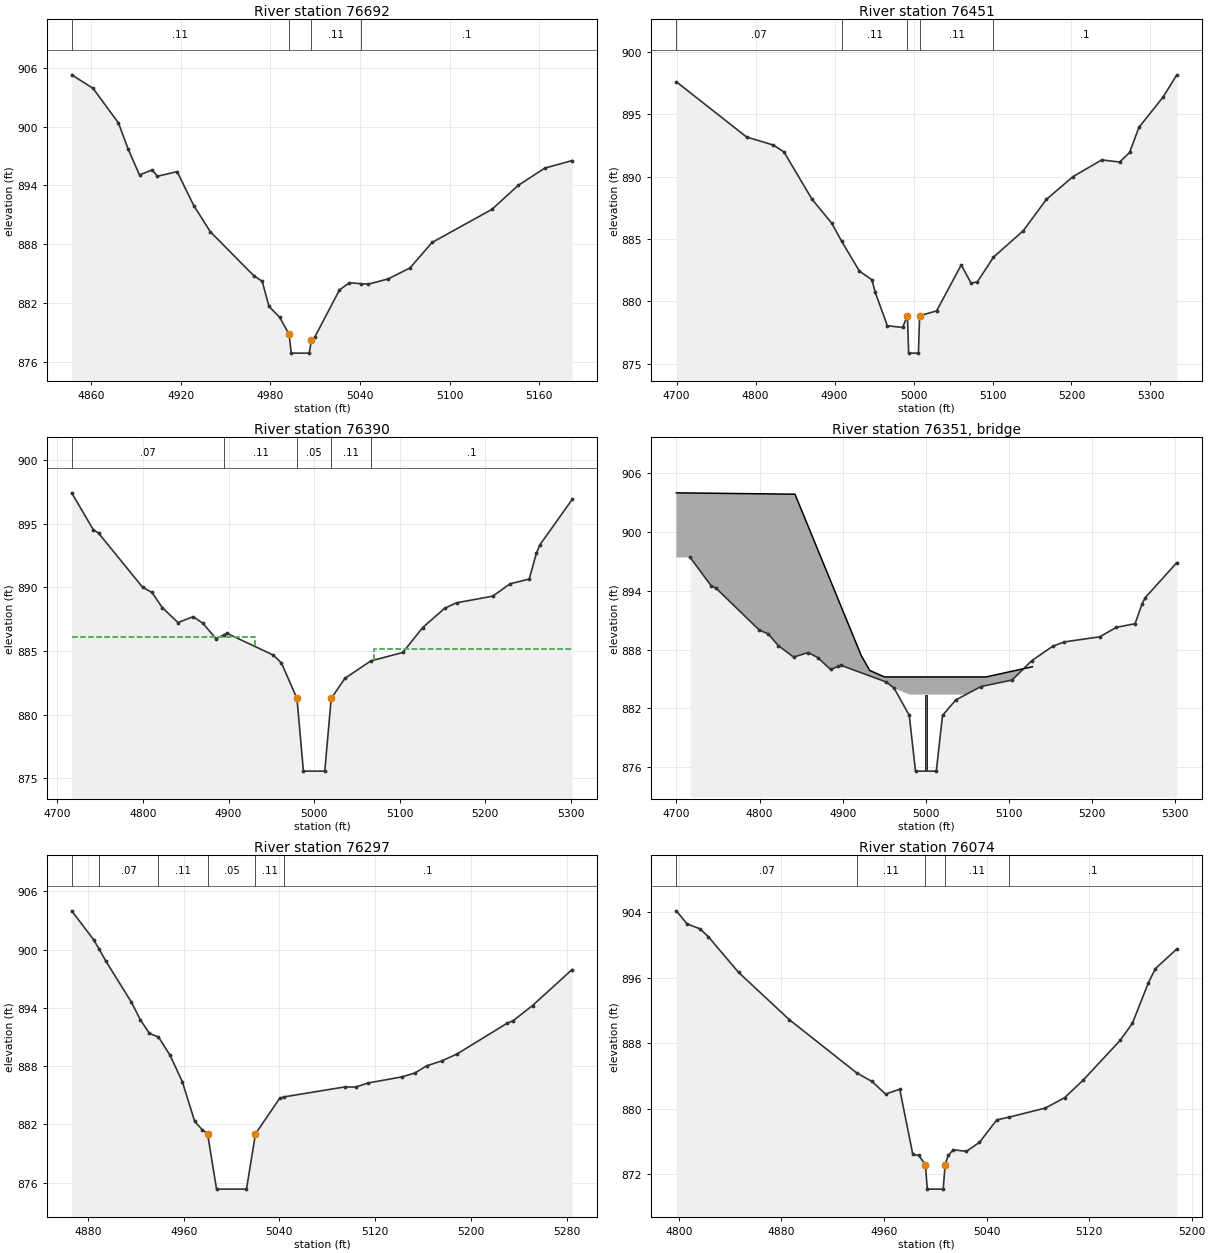
Type RM Length L Ch R = 1 ,76692   ,241,241,241
BEGIN DESCRIPTION:
North Deep Creek 218.0
END DESCRIPTION:
XS GIS Cut Line= 3
      1496274.24        893142.7       1496439.7       893094.27
       1496568.8       892995.43
#Sta/Elev= 30
    4847  905.29  4861.3  903.91  4878.3  900.38  4884.9  897.67  4892.4  895.07
  4900.8  895.59  4904.4  894.94  4917.6  895.41  4928.7  891.95  4939.8  889.28
  4968.9  884.79  4974.5  884.23  4979.1  881.65  4986.2  880.55  4992.5  878.82
    4994  876.89    5006  876.89  5007.5  878.23  5009.7  878.52  5026.2  883.33
  5032.9  884.08  5040.8  883.97  5045.6  883.93  5058.8  884.46  5073.5  885.59
  5088.2  888.18  5128.3  891.56  5145.9  894.01  5163.7  895.77    5182  896.54
#Mann= 4 ,-1 , 0
    4847     .11       0  4992.5     .05       0  5007.5     .11       0
  5040.8      .1       0
Bank Sta=4992.5,5007.5
Exp/Cntr=0.3,0.1

Type RM Length L Ch R = 1 ,76451   ,61,61,61
BEGIN DESCRIPTION:
North Deep Creek 217.0
END DESCRIPTION:
XS GIS Cut Line= 4
      1496435.66       893596.73      1496492.16       893354.57
      1496540.59       893294.04      1496595.06       892991.38
#Sta/Elev= 30
  4699.7  897.62  4788.6  893.19  4822.6  892.54  4835.9  891.99  4871.5  888.19
  4896.3  886.28  4908.9  884.83  4931.4  882.43  4947.4  881.72  4951.3  880.76
  4966.8  878.04  4986.1   877.9  4992.3  878.84  4993.8  875.84  5006.2  875.84
  5007.7  878.84  5029.2  879.23  5060.4  882.92  5072.9  881.45  5080.9  881.57
  5101.2  883.54    5139  885.67  5168.2  888.18  5201.7     890  5238.3  891.35
    5261  891.18  5273.6  891.95  5285.4  893.96  5315.8  896.38  5333.4  898.18
#Mann= 5 ,-1 , 0
  4699.7     .07       0  4908.9     .11       0  4992.3     .05       0
  5007.7     .11       0  5101.2      .1       0
Bank Sta=4992.3,5007.7
Exp/Cntr=0.5,0.3

Type RM Length L Ch R = 1 ,76390   ,93,93,93
BEGIN DESCRIPTION:
Hinshaw Rd (NDC) us
END DESCRIPTION:
XS GIS Cut Line= 5
      1496548.66       893580.55      1496584.98        893358.6
      1496576.91       893259.73      1496619.28       893072.08
      1496619.28       893003.45
#Sta/Elev= 30
  4716.6  897.41  4741.7  894.53  4748.1  894.24  4799.5     890  4810.5  889.59
  4822.4  888.41  4840.9  887.23  4858.6  887.69  4869.9  887.18  4885.4  885.96
  4894.9  886.28  4898.2  886.38    4952  884.69  4961.8  884.06    4980  881.27
  4987.5  875.57  5012.5  875.57    5020  881.27    5036  882.85  5066.3  884.22
  5103.7  884.88    5127  886.84  5152.7  888.35  5166.5  888.78  5208.9   889.3
  5229.1  890.27  5251.5  890.64  5259.9  892.67  5263.8  893.31  5301.7  896.89
#Mann= 5 ,-1 , 0
  4716.6     .07       0  4894.9     .11       0    4980     .05       0
    5020     .11       0  5066.3      .1       0
#XS Ineff= 2 , 0
       0  4930.5  886.11  5069.5       0  885.16
Permanent Ineff=
       F       F
Bank Sta=4980,5020
Exp/Cntr=0.5,0.3

Type RM Length L Ch R = 3 ,76351   ,,,
BEGIN DESCRIPTION:
Hinshaw Rd (NDC) tor
Structure ID: LDS_NDC_16
Approximate Survey Structure
END DESCRIPTION:
Bridge Culvert--1,0,-1,-1, 0
Deck Dist Width WeirC Skew NumUp NumDn MinLoCord MaxHiCord MaxSubmerge Is_Ogee
23.5,31,3,0, 11, 11, , , 0.95, 0, 1,1,,
    4700  4842.6  4922.3  4932.4    4950    4954    4954    5046    5046  5072.4
  5128.1
  904.02  903.88  887.38  885.87   885.2   885.2   885.2   885.2   885.2   885.2
  886.24
  855.57  855.57  855.57  855.57  855.57  855.57   883.4   883.4  855.57  855.57
  855.57
    4700  4842.6  4922.3  4932.4    4950    4954    4954    5046    5046  5072.4
  5128.1
  904.02  903.88  887.38  885.87   885.2   885.2   885.2   885.2   885.2   885.2
  886.24
  855.57  855.57  855.57  855.57  855.57  855.57   883.4   883.4  855.57  855.57
  855.57
Pier Skew, UpSta & Num, DnSta & Num=  ,5000, 2 ,5000, 2 , 0 , 0 , 0 ,0,0
       3       3
     850   883.4
       3       3
     850   883.4
Abutment Skew #Up #Dn= , 2 , 2
    4954    4965
   883.4  883.53
    4954    4965
   883.4  883.98
Abutment Skew #Up #Dn= , 2 , 2
    5035    5046
  882.62   883.4
    5035    5046
  883.73   883.4
BR Coef= 1 , 1 , 0 ,1.25, 0 ,,,0.8,0,2,0,
WSPro=,,,, 1 ,,,, 0 ,,,, 0 ,,,,-1 ,-1 ,-1 , 0 , 0 , 0 , 0 , 0
BC Design=,, 0 ,, 0 ,,,,,,
BC HTab HWMax=897.41

Type RM Length L Ch R = 1 ,76297   ,223,223,223
BEGIN DESCRIPTION:
Hinshaw Rd (NDC) ds
END DESCRIPTION:
XS GIS Cut Line= 4
      1496738.36       893355.61      1496645.51        893233.5
      1496649.55        893074.1       1496687.9        892976.2
#Sta/Elev= 30
  4866.5     904  4884.8  901.03  4889.4  900.06  4895.1  898.81  4916.4  894.58
  4923.8  892.79  4931.4  891.37    4939  890.99  4948.6  889.13  4958.9   886.4
  4969.2  882.31  4975.6  881.43    4980  881.02  4987.5  875.32  5012.5  875.32
    5020  881.02  5040.3  884.69    5044  884.83  5094.5  885.85  5103.8  885.84
  5114.1  886.26  5142.5  886.89  5153.2  887.29    5163  888.03  5175.7  888.54
  5188.4  889.25  5230.5  892.44  5235.4  892.69  5251.4  894.24  5284.5  897.95
#Mann= 6 ,-1 , 0
  4866.5     .11       0  4889.4     .07       0    4939     .11       0
    4980     .05       0    5020     .11       0    5044      .1       0
#XS Ineff= 2 , 0
       0  4915.5  889.27  5084.5       0  885.39
Permanent Ineff=
       F       F
Bank Sta=4980,5020
Exp/Cntr=0.5,0.3

Type RM Length L Ch R = 1 ,76074   ,340,340,340
BEGIN DESCRIPTION:
North Deep Creek 216.0
END DESCRIPTION:
XS GIS Cut Line= 3
      1496952.19       893263.73      1496748.42       893005.49
      1496704.04       892963.13
#Sta/Elev= 30
  4798.1  904.19  4806.5  902.58  4816.4     902    4823  901.03  4846.6  896.66
  4886.2  890.87  4938.9  884.34  4950.7  883.31  4961.2  881.77  4972.3  882.36
  4982.5  874.38  4987.1  874.27  4992.3  873.14  4993.8  870.14  5006.2  870.14
  5007.7  873.14  5010.1  874.27  5014.1  874.96  5024.3  874.76  5034.5  875.87
    5048  878.61  5057.6  878.95  5085.9  880.06  5100.8  881.32  5115.2  883.45
  5144.2  888.34  5153.7  890.42  5166.3  895.42  5171.7  897.12  5188.4  899.53
#Mann= 5 ,-1 , 0
  4798.1     .07       0  4938.9     .11       0  4992.3     .05       0
  5007.7     .11       0  5057.6      .1       0
Bank Sta=4992.3,5007.7
Exp/Cntr=0.3,0.1

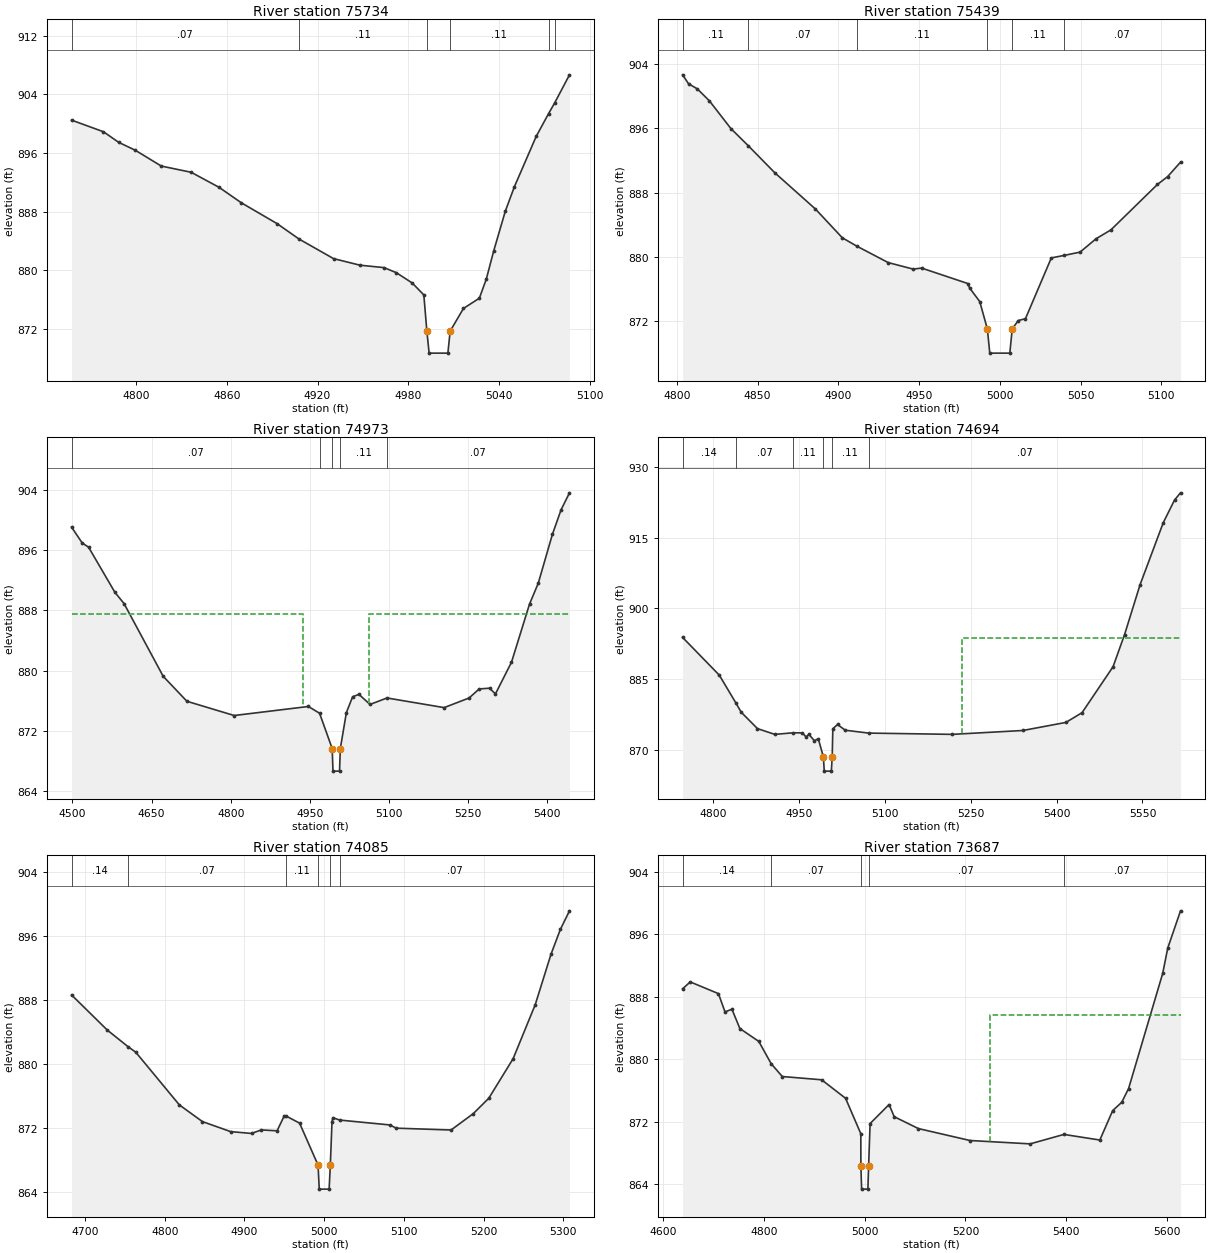
Type RM Length L Ch R = 1 ,75734   ,295,295,295
BEGIN DESCRIPTION:
North Deep Creek 215.0
END DESCRIPTION:
XS GIS Cut Line= 3
      1497194.34       893104.34      1497107.59       892953.03
      1497049.06       892809.73
#Sta/Elev= 30
  4757.4  900.49  4778.5   898.9  4788.6  897.45  4799.6  896.37  4816.7  894.22
  4836.5  893.37  4854.9  891.32  4869.7   889.2  4893.3  886.36  4907.8  884.26
  4930.6  881.59  4948.1  880.69    4964  880.36  4972.2  879.66  4982.7  878.25
  4990.3  876.63  4992.3  871.69  4993.8  868.69  5006.2  868.69  5007.7  871.69
  5016.5  874.79    5027  876.18  5031.6  878.79  5036.5  882.64  5044.2  888.08
  5050.2  891.41  5064.6  898.27  5072.8  901.39  5076.7   902.8  5086.6  906.67
#Mann= 6 ,-1 , 0
  4757.4     .07       0  4907.8     .11       0  4992.3     .05       0
  5007.7     .11       0  5072.8      .1       0  5076.7     .07       0
Bank Sta=4992.3,5007.7
Exp/Cntr=0.3,0.1

Type RM Length L Ch R = 1 ,75439   ,466,466,466
BEGIN DESCRIPTION:
North Deep Creek 214.0
END DESCRIPTION:
XS GIS Cut Line= 3
      1497386.13        893035.7      1497386.13       892879.59
      1497319.19       892742.92
#Sta/Elev= 30
  4803.6  902.62  4807.3  901.51  4812.7  900.88  4820.2  899.39  4833.5  895.95
  4844.4  893.79  4860.7  890.46  4885.8  885.97  4902.5  882.39  4911.3  881.37
  4930.9  879.31  4946.4   878.5  4951.6  878.63  4980.2  876.71  4981.3  876.16
  4987.6  874.47  4992.3  871.07  4993.8  868.07  5006.2  868.07  5007.7  871.07
  5011.4  872.11  5015.9  872.35  5031.9  879.89  5039.8   880.2  5049.7  880.61
  5059.6  882.27  5068.8  883.37  5097.6  889.01  5103.9  889.98  5111.9  891.78
#Mann= 6 ,-1 , 0
  4803.6     .11       0  4844.4     .07       0  4911.3     .11       0
  4992.3     .05       0  5007.7     .11       0  5039.8     .07       0
Bank Sta=4992.3,5007.7
Exp/Cntr=0.3,0.1

Type RM Length L Ch R = 1 ,74973   ,279,279,279
BEGIN DESCRIPTION:
North Deep Creek 213.0
END DESCRIPTION:
XS GIS Cut Line= 5
      1497996.78       893085.89      1497941.02       892890.74
      1497659.39       892561.71       1497514.4       892503.16
      1497363.85         892492.
#Sta/Elev= 30
  4498.5  899.07  4518.7  896.95  4530.7   896.4  4580.6   890.4    4598   888.9
  4672.1  879.24  4717.1  875.92  4806.6  874.03  4947.2  875.23  4968.4  874.33
  4992.3  869.64  4993.8  866.64  5006.2  866.64  5007.7  869.64  5019.2  874.42
    5031  876.52    5043  876.84    5064   875.5  5096.1  876.36  5204.4  875.08
  5251.7  876.36  5270.8  877.56  5290.4  877.66  5301.6   876.9    5332  881.11
  5366.2  888.84  5382.7   891.6  5409.6  898.12    5426  901.37  5441.9  903.62
#Mann= 5 ,-1 , 0
  4498.5     .07       0  4968.4     .11       0  4992.3     .05       0
  5007.7     .11       0  5096.1     .07       0
#XS Ineff= 2 , 0
       0  4937.5  887.52  5062.5       0  887.52
Permanent Ineff=
       F       F
Bank Sta=4992.3,5007.7
Exp/Cntr=0.3,0.1

Type RM Length L Ch R = 1 ,74694   ,609,609,609
BEGIN DESCRIPTION:
North Deep Creek 212.0
END DESCRIPTION:
XS GIS Cut Line= 5
      1498164.13       892572.88      1498030.25       892500.37
      1497896.41       892455.75      1497567.38       892232.68
      1497439.11        892107.2
#Sta/Elev= 30
  4746.2  893.88  4810.4  885.89  4839.1  880.06  4848.7  878.04  4877.1  874.58
  4907.3  873.36  4939.4  873.69  4955.7  873.68  4961.9  872.83  4967.1  873.36
  4976.4  872.02  4983.4  872.42  4992.3  868.58  4993.8  865.58  5006.2  865.58
  5007.7  868.58  5008.8  874.54    5017  875.45  5030.4  874.24  5071.4  873.63
  5217.6  873.36  5340.9  874.18  5416.2  875.89  5444.4  877.95  5498.6  887.68
  5518.7  894.48  5545.9  905.07  5586.3  918.15  5606.1  922.97  5616.5  924.48
#Mann= 6 ,-1 , 0
  4746.2     .14       0  4839.1     .07       0  4939.4     .11       0
  4992.3     .05       0  5007.7     .11       0  5071.4     .07       0
#XS Ineff= 2 , 0
       0                  5234.2       0  893.69
Permanent Ineff=
       F       F
Bank Sta=4992.3,5007.7
Exp/Cntr=0.3,0.1

Type RM Length L Ch R = 1 ,74085   ,398,398,398
BEGIN DESCRIPTION:
North Deep Creek 210.0
END DESCRIPTION:
XS GIS Cut Line= 5
      1498350.94       892034.72      1498241.82       891946.87
      1498107.33       891891.98      1497885.01       891820.61
      1497799.91       891757.48
#Sta/Elev= 30
    4683  888.61    4728  884.21  4754.3  882.12  4763.5  881.47  4818.2  874.89
  4847.2   872.8  4882.6  871.55  4908.8  871.32  4921.1  871.76  4940.9  871.65
  4949.6  873.46  4951.9  873.51  4969.1  872.61  4992.3  867.37  4993.8  864.37
  5006.2  864.37  5007.7  867.37  5009.8  872.78  5010.8  873.29  5019.5  872.99
  5082.7  872.38  5090.2  871.98  5159.2  871.75    5187  873.79  5206.5  875.71
  5237.1  880.66  5264.8  887.39  5284.6  893.69  5296.3  896.78  5307.8  899.11
#Mann= 6 ,-1 , 0
    4683     .14       0  4754.3     .07       0  4951.9     .11       0
  4992.3     .05       0  5007.7     .11       0  5019.5     .07       0
Bank Sta=4992.3,5007.7
Exp/Cntr=0.3,0.1

Type RM Length L Ch R = 1 ,73687   ,551,551,551
BEGIN DESCRIPTION:
North Deep Creek 209.0
END DESCRIPTION:
XS GIS Cut Line= 4
      1498359.28        892062.6      1498406.69       891767.01
      1498409.48       891242.79      1498395.53       891078.27
#Sta/Elev= 30
  4638.3  889.03  4653.5  889.91  4709.5  888.41  4722.5  886.07  4736.3  886.41
    4752  883.94  4789.6  882.29  4814.1  879.44  4836.2  877.79  4914.4  877.37
  4961.9     875  4992.2  870.46  4992.3  866.36  4993.8  863.36  5006.2  863.36
  5007.7  866.36  5010.6  871.76  5048.3   874.2  5058.5  872.64  5106.5  871.12
    5209  869.59  5328.5  869.16  5395.5  870.37  5466.8  869.65  5492.3  873.42
  5510.3  874.49  5523.9  876.25  5591.6     891  5601.7  894.26    5627  899.02
#Mann= 5 ,-1 , 0
  4638.3     .14       0  4814.1     .07       0  4992.3     .05       0
  5007.7     .07       0  5395.5     .07       0
#XS Ineff= 2 , 0
       0                  5249.4       0  885.61
Permanent Ineff=
       F       F
Bank Sta=4992.3,5007.7
Exp/Cntr=0.3,0.1

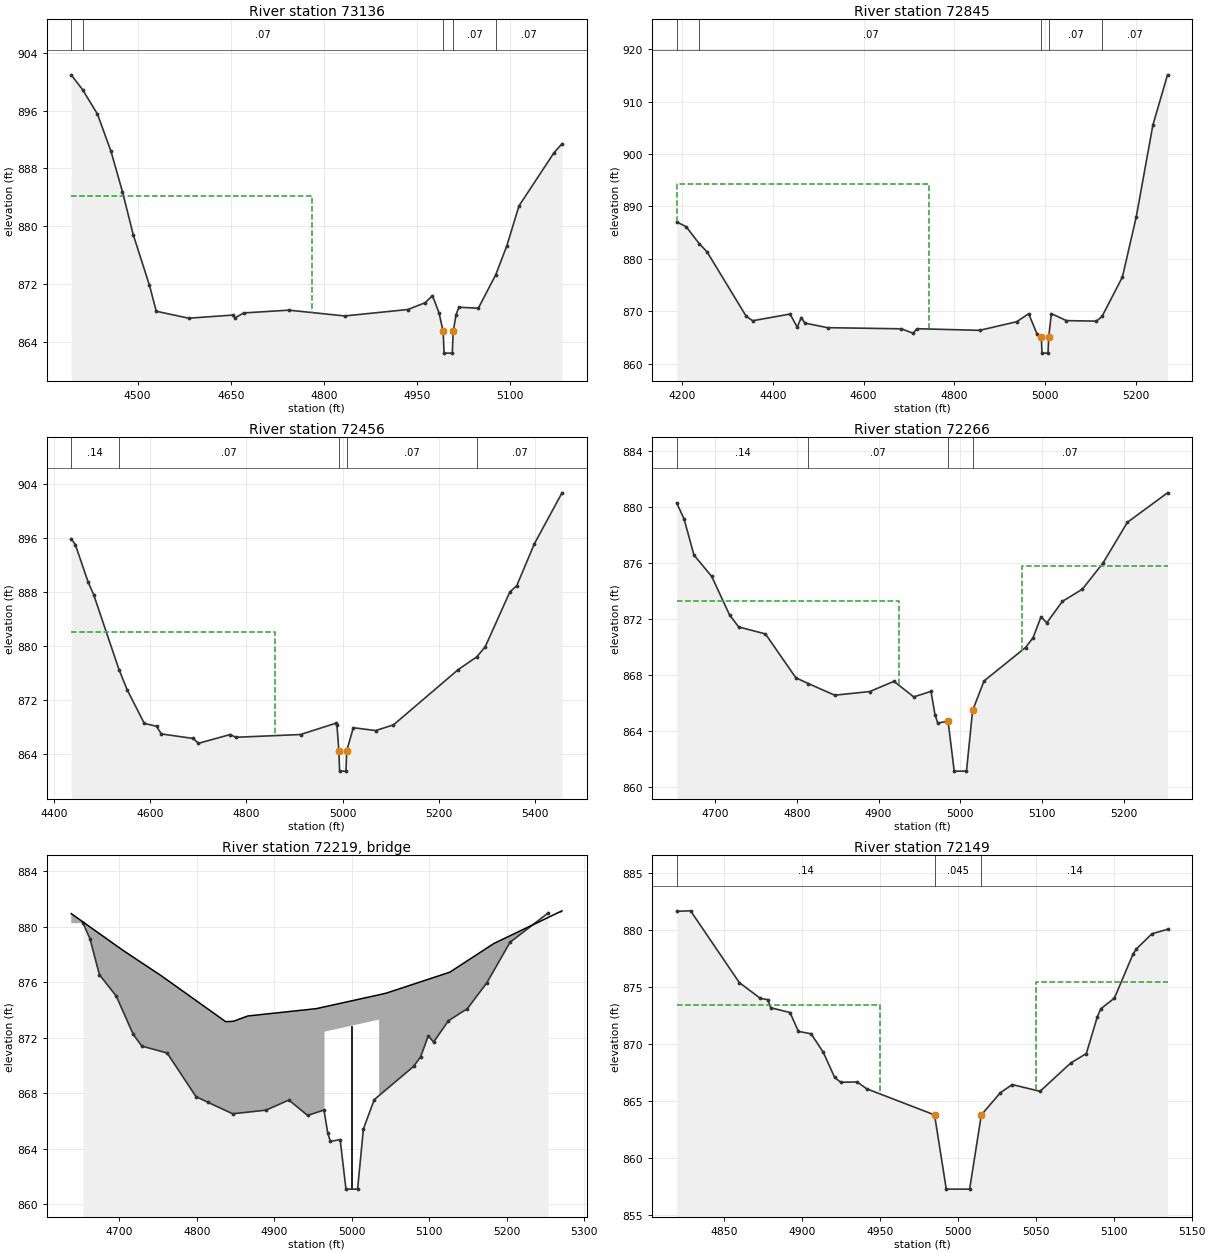
Type RM Length L Ch R = 1 ,73136   ,291,291,291
BEGIN DESCRIPTION:
North Deep Creek 208.0
END DESCRIPTION:
XS GIS Cut Line= 5
      1498705.05       892436.23       1498763.6       892316.33
      1498919.76       891912.01      1498922.54       891819.99
      1498975.52       891700.09
#Sta/Elev= 30
  4393.2  900.94  4411.4   898.9  4435.4  895.52  4457.2  890.37  4475.7  884.78
  4493.2  878.79  4519.2  871.83  4530.1  868.25  4582.2  867.29  4653.2  867.72
  4656.7  867.33    4671  868.02  4743.6   868.4  4833.4   867.6  4935.1  868.49
  4963.1  869.44  4974.7  870.41  4985.3  868.01  4991.9  865.46  4993.4  862.46
  5006.6  862.46  5008.1  865.46  5012.7  867.79  5017.3  868.81  5048.5  868.67
  5076.5  873.29  5094.5  877.32  5113.9  882.81  5170.5  890.19  5183.2  891.41
#Mann= 5 ,-1 , 0
  4393.2     .14       0  4411.4     .07       0  4991.9     .05       0
  5008.1     .07       0  5076.5     .07       0
#XS Ineff= 2 , 0
       0  4781.5  884.19               0
Permanent Ineff=
       F       F
Bank Sta=4991.9,5008.1
Exp/Cntr=0.3,0.1

Type RM Length L Ch R = 1 ,72845   ,389,389,389
BEGIN DESCRIPTION:
North Deep Creek 207.0
END DESCRIPTION:
XS GIS Cut Line= 4
      1499326.87       892653.76      1499229.27       892388.83
      1499206.96       891753.07      1499156.77       891596.92
#Sta/Elev= 30
  4187.7  887.05  4208.5  886.14  4237.5  882.89  4254.6  881.34  4340.9  869.05
  4355.2  868.19  4437.7  869.47  4453.5  866.96  4462.3   868.8  4470.3  867.75
  4520.3  866.87  4683.3  866.65  4708.8  865.81  4717.6  866.67  4855.7  866.36
  4937.4     868    4964  869.53  4982.6  865.62  4991.9  865.01  4993.4  862.01
  5006.6  862.01  5008.1  865.01    5014  869.55  5047.3  868.21  5113.5  868.12
  5125.7     869  5170.7  876.53  5201.2     888    5238  905.56  5270.2  915.12
#Mann= 5 ,-1 , 0
  4187.7     .14       0  4237.5     .07       0  4991.9     .05       0
  5008.1     .07       0  5125.7     .07       0
#XS Ineff= 2 , 0
       0  4743.6  894.22               0
Permanent Ineff=
       F       F
Bank Sta=4991.9,5008.1
Exp/Cntr=0.3,0.1

Type RM Length L Ch R = 1 ,72456   ,190,190,190
BEGIN DESCRIPTION:
North Deep Creek 206.0
END DESCRIPTION:
XS GIS Cut Line= 5
      1499689.33       892514.27      1499597.34       892386.04
      1499549.94       892017.97      1499580.61       891861.82
      1499544.36       891532.77
#Sta/Elev= 30
  4436.1  895.93  4444.7  895.06  4471.1  889.52  4482.7  887.64  4535.3   876.5
  4552.3  873.49  4587.8   868.5  4613.4  868.06  4623.2  866.93  4689.7  866.25
  4700.2  865.53  4766.3  866.84  4777.8  866.43  4912.3  866.84  4985.2  868.51
  4987.8  868.32  4991.9   864.4  4993.4   861.4  5006.6   861.4  5008.1   864.4
  5021.9  867.85  5068.3  867.43  5105.2  868.27  5239.7  876.49    5278  878.37
  5295.7  879.87  5346.9  888.03  5361.2  888.96  5397.8  895.18  5455.2  902.76
#Mann= 5 ,-1 , 0
  4436.1     .14       0  4535.3     .07       0  4991.9     .05       0
  5008.1     .07       0    5278     .07       0
#XS Ineff= 2 , 0
       0  4858.6  882.08               0
Permanent Ineff=
       F       F
Bank Sta=4991.9,5008.1
Exp/Cntr=0.5,0.3

Type RM Length L Ch R = 1 ,72266   ,117,117,117
BEGIN DESCRIPTION:
Patterson Mill Rd (NDC) us
END DESCRIPTION:
XS GIS Cut Line= 5
        1499826.       892347.05      1499753.49       892061.19
        1499727.       891952.44      1499708.88       891849.27
      1499720.03       891761.47
#Sta/Elev= 30
  4653.2  880.27  4662.1  879.15  4674.3  876.55    4696  875.02  4717.9  872.26
    4729  871.41  4761.7  870.91  4798.9  867.77  4814.2  867.36  4846.3  866.53
  4889.2  866.79  4918.8  867.52    4943  866.41  4964.1   866.8    4969  865.14
  4972.4  864.54    4985  864.67  4992.5   861.1  5007.5   861.1    5015  865.44
    5029  867.55  5079.7  869.94  5088.8  870.63  5098.7  872.14  5105.6   871.7
  5124.8  873.24  5149.2  874.11  5174.4  875.98  5204.2  878.89  5253.3     881
#Mann= 4 ,-1 , 0
  4653.2     .14       0  4814.2     .07       0    4985    .045       0
    5015     .07       0
#XS Ineff= 2 , 0
       0    4925  873.23    5075       0  875.76
Permanent Ineff=
       F       F
Bank Sta=4985,5015
Exp/Cntr=0.5,0.3

Type RM Length L Ch R = 3 ,72219   ,,,
BEGIN DESCRIPTION:
Patterson Mill Rd (NDC) tor
Structure ID: LDS_NDC_15
Approximate Survey Structure
END DESCRIPTION:
Bridge Culvert--1,0,-1,-1, 0
Deck Dist Width WeirC Skew NumUp NumDn MinLoCord MaxHiCord MaxSubmerge Is_Ogee
33.5,27,3,0, 15, 15, , , 0.95, 0, 1,1,,
  4637.9  4704.5  4754.4  4837.3  4847.3  4865.7  4954.3  4964.8  4964.8  5035.3
  5035.3  5044.7  5126.6  5183.2  5271.3
  880.96  878.32  876.47  873.17   873.2  873.58  874.11  874.24  874.24  875.11
  875.11  875.23  876.74   878.8  881.16
   841.1   841.1   841.1   841.1   841.1   841.1   841.1   841.1  872.45  873.32
   841.1   841.1   841.1   841.1   841.1
  4637.9  4704.5  4754.4  4837.3  4847.3  4865.7  4954.3  4964.8  4964.8  5035.3
  5035.3  5044.7  5126.6  5183.2  5271.3
  880.96  878.32  876.47  873.17   873.2  873.58  874.11  874.24  874.24  875.11
  875.11  875.23  876.74   878.8  881.16
   841.1   841.1   841.1   841.1   841.1   841.1   841.1   841.1  872.45  873.32
   841.1   841.1   841.1   841.1   841.1
Pier Skew, UpSta & Num, DnSta & Num=  ,5000, 2 ,5000, 2 , 0 , 0 , 0 ,0,0
       1       1
     850     873
       1       1
     850     873
Abutment Skew #Up #Dn= , 2 , 2
  4964.8    4975
  872.45  864.62
  4964.8    4975
  872.45  866.41
Abutment Skew #Up #Dn= , 2 , 2
    5025  5035.3
  867.03  873.32
    5025  5035.3
     866  873.32
BR Coef= 1 , 1 , 0 ,1.25, 0 ,,,0.8,-1,2,0,
WSPro=,,,, 1 ,,,, 0 ,,,, 0 ,,,,-1 ,-1 ,-1 , 0 , 0 , 0 , 0 , 0
BC Design=,, 0 ,, 0 ,,,,,,
BC HTab HWMax=881

Type RM Length L Ch R = 1 ,72149   ,22,22,22
BEGIN DESCRIPTION:
Patterson Mill Rd (NDC) ds
END DESCRIPTION:
XS GIS Cut Line= 4
      1499874.78       892136.44      1499844.81        891962.2
      1499828.78       891906.44      1499827.38       891826.27
#Sta/Elev= 30
  4819.5  881.63  4828.4  881.67  4859.7  875.38  4873.2     874  4877.9  873.89
  4879.8  873.18  4892.2  872.76  4897.6  871.11  4905.7   870.9  4913.5   869.3
  4920.8  867.09  4924.8  866.65  4935.3  866.68  4941.4  866.08    4985  863.79
  4992.5  857.29  5007.5  857.29    5015  863.79  5027.1  865.72  5034.8  866.45
  5052.7  865.86  5072.4  868.34  5082.4  869.17  5089.5  872.41  5091.7  873.09
  5100.4  874.02  5112.3  877.86  5114.5  878.33  5124.5  879.66  5134.5  880.05
#Mann= 3 ,-1 , 0
  4819.5     .14       0    4985    .045       0    5015     .14       0
#XS Ineff= 2 , 0
       0    4950  873.45    5050       0  875.46
Permanent Ineff=
       F       F
Bank Sta=4985,5015
Exp/Cntr=0.5,0.3