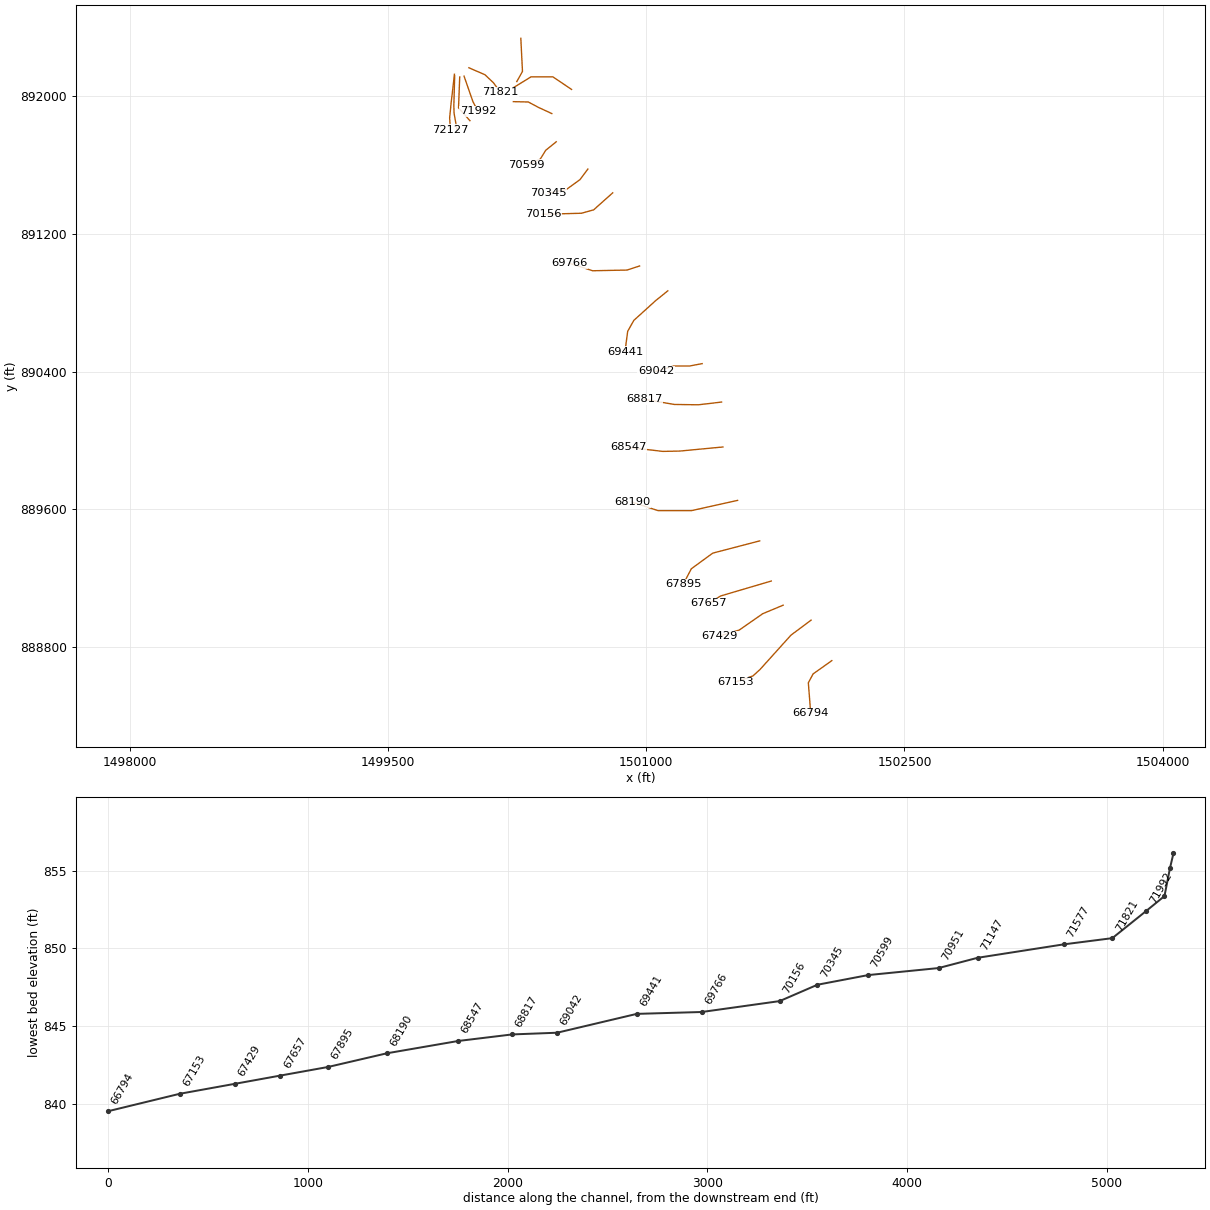
HEC-RAS study North Deep Creek.prj: North Deep Creek Limited Detail Study

--- North Deep Creek.g01 (geometry) --- (continued)

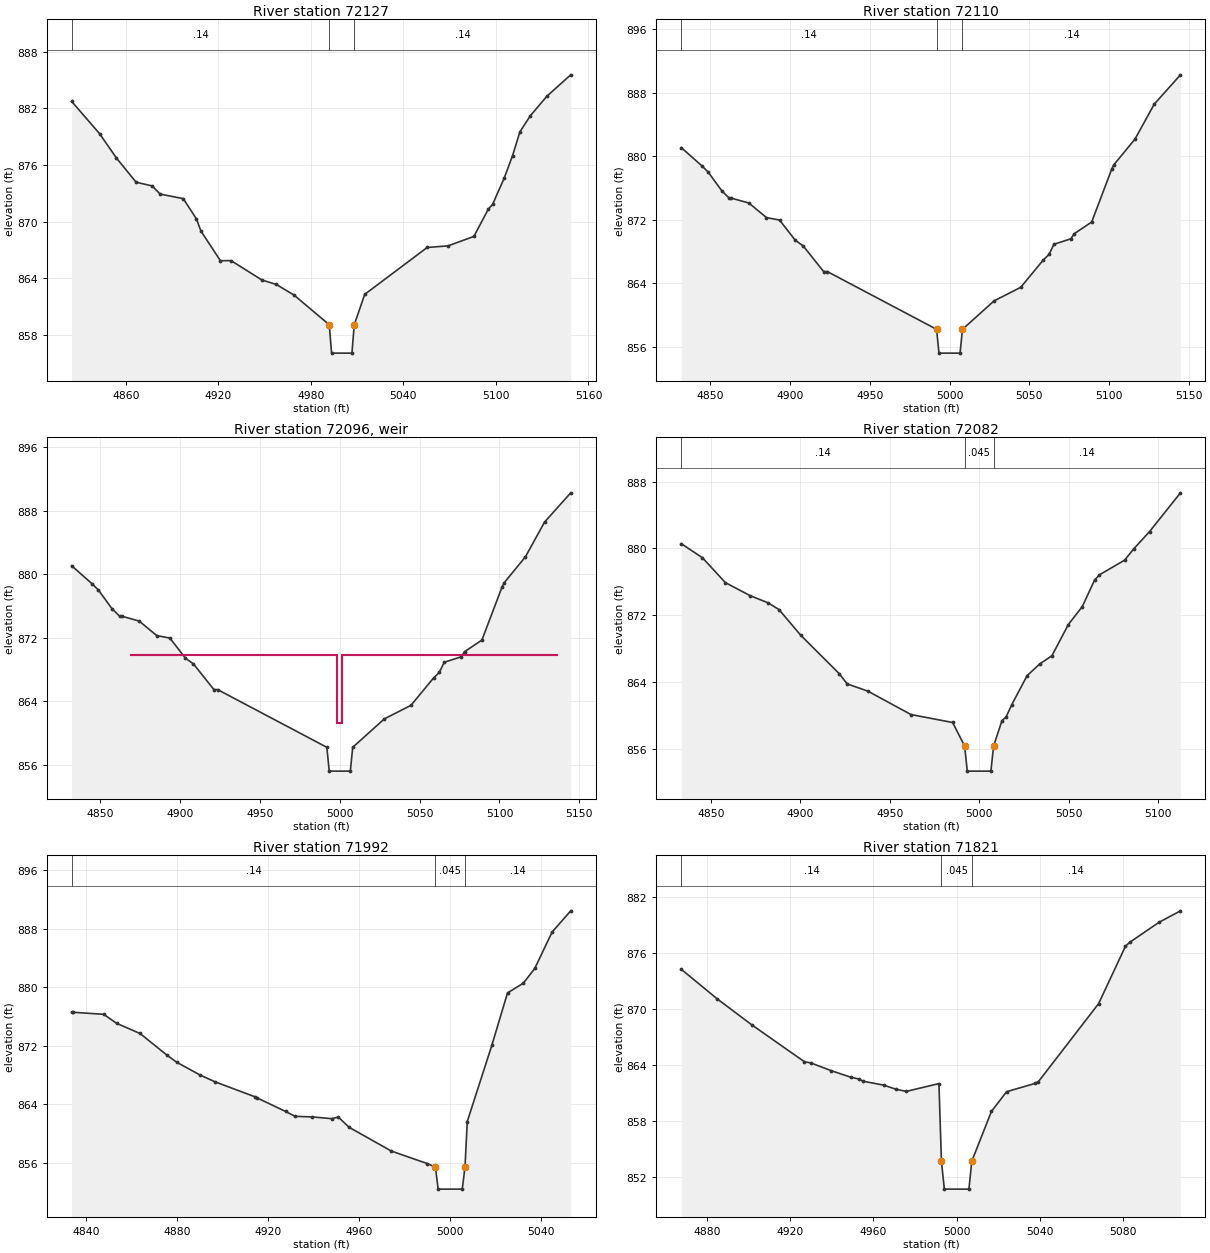
Type RM Length L Ch R = 1 ,72127   ,17,17,17
BEGIN DESCRIPTION:
North Deep Creek 205.0
END DESCRIPTION:
XS GIS Cut Line= 4
      1499885.94       892128.07      1499866.42       891958.02
      1499858.06       891874.37      1499862.24       891806.03
#Sta/Elev= 30
  4824.8  882.74  4842.9  879.33  4853.9  876.74  4866.6  874.19  4877.1  873.79
  4882.2  872.93  4897.2  872.45  4905.7  870.32  4908.7  869.01  4921.3  865.88
  4928.2  865.89  4948.2  863.84  4957.5  863.37  4969.1  862.24  4991.9   859.1
  4993.4   856.1  5006.6   856.1  5008.1   859.1  5014.9  862.32  5055.4  867.28
  5068.9  867.45  5085.7  868.45  5095.1  871.35  5097.8  871.83  5105.3   874.6
  5110.8  877.01  5115.5   879.5  5122.3  881.22    5133  883.28  5148.5  885.55
#Mann= 3 ,-1 , 0
  4824.8     .14       0  4991.9    .045       0  5008.1     .14       0
Bank Sta=4991.9,5008.1
Exp/Cntr=0.5,0.3

Type RM Length L Ch R = 1 ,72110   ,28,28,28
BEGIN DESCRIPTION:
Private Dr 1 (NDC) us
END DESCRIPTION:
XS GIS Cut Line= 4
      1499887.34       892118.39      1499882.45       891946.17
      1499883.85       891900.86      1499900.58       891807.46
#Sta/Elev= 30
  4832.1  881.05    4845  878.76  4848.9  877.98  4857.4  875.63  4862.1   874.7
  4863.4   874.7  4874.4  874.08  4885.4  872.25  4893.6  871.94  4903.4   869.4
  4908.4  868.68  4921.2  865.45  4923.5  865.45  4991.9  858.18  4993.4  855.18
  5006.6  855.18  5008.1  858.18  5027.9  861.76  5044.6  863.47  5058.7  866.91
  5062.3  867.61  5065.4  868.89    5076  869.58  5078.1  870.22    5089  871.69
  5101.6  878.37  5102.9   878.9  5116.2  882.16  5128.2  886.54  5144.6  890.23
#Mann= 3 ,-1 , 0
  4832.1     .14       0  4991.9    .045       0  5008.1     .14       0
Bank Sta=4991.9,5008.1
Exp/Cntr=0.5,0.3

Type RM Length L Ch R = 5 ,72096   ,,,
BEGIN DESCRIPTION:
Private Dr 1 (NDC) tor
Structure ID: LDS_NDC_14A
Approximate Survey Structure
END DESCRIPTION:
IW Pilot Flow=0
#Inline Weir SE= 6
  4869.1   869.8  4998.5   869.8  4998.5   861.3  5001.5   861.3  5001.5   869.8
  5135.7   869.8
IW Dist,WD,Coef,Skew,MaxSub,Min_El,Is_Ogee,SpillHt,DesHd
12,4,3,0,0.95,, 0 ,,,1,1,

Type RM Length L Ch R = 1 ,72082   ,90,90,90
BEGIN DESCRIPTION:
Private Dr 1 (NDC) ds
END DESCRIPTION:
XS GIS Cut Line= 3
      1499916.61       892112.12      1499909.64       891932.93
      1499975.88       891858.32
#Sta/Elev= 30
  4833.5  880.57  4845.3  878.89  4858.1  875.92    4872  874.35  4882.1  873.49
  4888.1  872.69  4900.3  869.61  4921.8  865.02  4926.2   863.8  4937.8  862.93
  4961.9  860.13  4985.2  859.18  4991.9  856.36  4993.4  853.36  5006.6  853.36
  5008.1  856.36  5012.8  859.41  5015.1  859.84  5018.2  861.29  5026.8  864.77
  5033.8  866.17  5040.7  867.16  5049.9   870.9  5057.7  873.05  5064.6  876.23
  5067.3  876.85  5081.4  878.61  5086.4  879.94  5095.3  882.02  5112.6  886.66
#Mann= 3 ,-1 , 0
  4833.5     .14       0  4991.9    .045       0  5008.1     .14       0
Bank Sta=4991.9,5008.1
Exp/Cntr=0.5,0.3

Type RM Length L Ch R = 1 ,71992   ,171,171,171
BEGIN DESCRIPTION:
North Deep Creek 204.0
END DESCRIPTION:
XS GIS Cut Line= 3
       1499941.7       892116.98      1499993.29       891969.17
      1500022.56       891913.44
#Sta/Elev= 30
  4833.5  876.59    4834  876.57  4847.6  876.29  4853.3  875.06  4863.6  873.67
  4875.6  870.67  4879.7  869.75  4889.8  868.03  4896.5  867.08  4914.3  865.01
    4915  864.89  4927.6  863.02  4931.8  862.36  4939.4  862.28  4947.9  862.04
  4950.8  862.26  4955.5  860.87  4974.1  857.62    4990   855.9  4993.5  855.42
  4994.7  852.42  5005.3  852.42  5006.5  855.42  5007.5  861.65  5018.3  872.05
  5025.2  879.21  5032.2  880.55  5037.2  882.56  5044.8  887.52    5053  890.42
#Mann= 3 ,-1 , 0
  4833.5     .14       0  4993.5    .045       0  5006.5     .14       0
Bank Sta=4993.5,5006.5
Exp/Cntr=0.3,0.1

Type RM Length L Ch R = 1 ,71821   ,244,244,244
BEGIN DESCRIPTION:
North Deep Creek 203.0
END DESCRIPTION:
XS GIS Cut Line= 4
      1499969.57       892165.77        1500063.       892125.33
       1500113.2       892077.92      1500153.61       892022.18
#Sta/Elev= 26
  4867.8  874.21    4885  871.05  4901.7  868.25  4926.9  864.31  4929.9  864.19
  4939.8  863.35  4949.3  862.64  4952.9  862.47  4955.2  862.22    4965   861.8
  4970.8  861.37  4975.8  861.13  4991.5  861.97  4992.7  853.66  4994.1  850.66
  5005.9  850.66  5007.3  853.66  5016.7  858.98    5024   861.1  5037.6  861.98
  5039.3  862.18  5068.2  870.54  5081.1  876.69  5083.1   877.1  5097.2  879.25
  5107.5  880.48
#Mann= 3 ,-1 , 0
  4867.8     .14       0  4992.7    .045       0  5007.3     .14       0
Bank Sta=4992.7,5007.3
Exp/Cntr=0.3,0.1

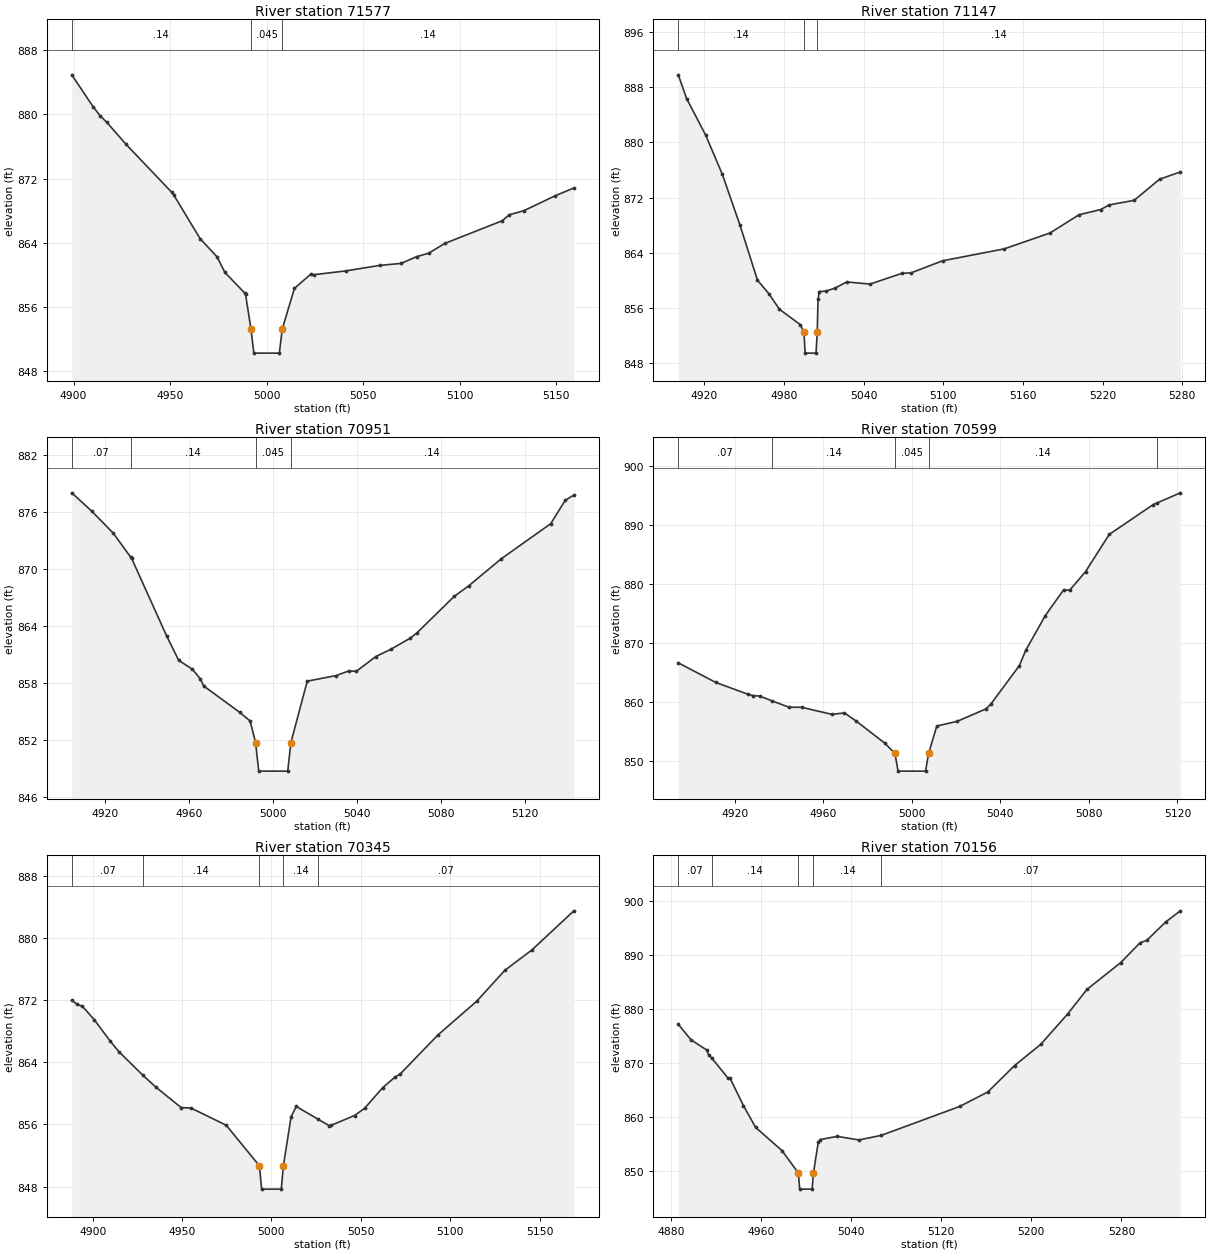
Type RM Length L Ch R = 1 ,71577   ,430,430,430
BEGIN DESCRIPTION:
North Deep Creek 202.0
END DESCRIPTION:
XS GIS Cut Line= 3
      1500271.53       892336.65      1500281.14       892144.49
      1500248.19       892085.47
#Sta/Elev= 30
  4899.1  884.91  4910.3  880.89  4913.7  879.84  4917.3  878.98  4927.2  876.26
  4950.8   870.3  4951.9  869.96  4965.5  864.53  4974.3  862.26  4978.4  860.31
  4988.6  857.76  4989.1  857.57  4991.9  853.26  4993.4  850.26  5006.6  850.26
  5008.1  853.26  5014.4  858.32  5022.9   860.1  5024.4  860.02  5041.1   860.5
  5058.5  861.18  5069.6  861.43  5077.7  862.27  5083.9   862.7  5092.3  863.92
    5122  866.74  5125.7  867.49  5133.2  867.99  5149.4  869.85  5159.1  870.82
#Mann= 3 ,-1 , 0
  4899.1     .14       0  4991.9    .045       0  5008.1     .14       0
Bank Sta=4991.9,5008.1
Exp/Cntr=0.3,0.1

Type RM Length L Ch R = 1 ,71147   ,196,196,196
BEGIN DESCRIPTION:
North Deep Creek 200.0
END DESCRIPTION:
XS GIS Cut Line= 4
      1500566.23       892039.95       1500457.5       892113.09
      1500331.02       892113.09      1500228.25       892049.85
#Sta/Elev= 30
  4900.3  889.82  4906.6  886.38  4920.9  881.09  4933.4  875.43  4946.8  867.99
    4960  859.99  4968.7     858  4976.5  855.77  4992.3  853.53    4995   852.4
  4995.9   849.4  5004.1   849.4    5005   852.4  5005.6   857.2  5006.6  858.35
  5011.4   858.4  5018.5  858.85  5027.2  859.74  5044.8  859.43    5069     861
  5075.6  861.05  5099.4  862.81  5145.8  864.54  5180.4  866.85  5202.2   869.5
  5218.5  870.25  5224.9  870.93  5243.7  871.59  5262.9  874.66  5278.5  875.71
#Mann= 3 ,-1 , 0
  4900.3     .14       0    4995    .045       0    5005     .14       0
Bank Sta=4995,5005
Exp/Cntr=0.3,0.1

Type RM Length L Ch R = 1 ,70951   ,352,352,352
BEGIN DESCRIPTION:
North Deep Creek 199.0
END DESCRIPTION:
XS GIS Cut Line= 4
      1500451.56       891899.66       1500374.5       891935.23
      1500315.21       891966.85       1500228.3       891968.82
#Sta/Elev= 30
  4904.1  878.06  4913.5  876.15  4923.9   873.8  4932.2  871.26  4932.6  871.15
  4949.2  863.01    4955  860.41  4961.5  859.48  4965.3  858.46  4966.9  857.71
    4984  854.94    4989  854.02  4991.6  851.74  4993.1  848.74  5006.9  848.74
  5008.4  851.74  5016.2  858.22    5030  858.81  5035.9  859.29  5039.6  859.26
  5048.8  860.81  5056.2   861.6  5065.2  862.75  5068.2  863.26  5086.1  867.14
  5093.1  868.27  5108.6  871.12  5132.1  874.81    5139  877.27  5143.1  877.82
#Mann= 4 ,-1 , 0
  4904.1     .07       0  4932.2     .14       0  4991.6    .045       0
  5008.4     .14       0
Bank Sta=4991.6,5008.4
Exp/Cntr=0.3,0.1

Type RM Length L Ch R = 1 ,70599   ,254,254,254
BEGIN DESCRIPTION:
North Deep Creek 197.0
END DESCRIPTION:
XS GIS Cut Line= 4
       1500477.3       891735.64        1500416.       891686.21
      1500384.38       891634.82      1500303.35       891601.23
#Sta/Elev= 30
  4894.5  866.62  4911.5  863.29  4925.8  861.33  4928.1  861.08  4931.3  860.99
  4936.9  860.18  4944.5  859.11  4950.3  859.09  4963.9   857.9  4969.6  858.14
  4974.9  856.76  4987.9  852.99  4992.4  851.29  4993.8  848.29  5006.2  848.29
  5007.6  851.29  5011.3  855.92  5020.6  856.73  5033.6  858.84  5035.8  859.68
  5048.6  866.15  5051.5  868.75  5060.3  874.61  5068.6  878.97  5071.3   878.9
  5078.5  882.06  5089.2  888.35  5109.1  893.41  5110.8  893.68  5121.3  895.39
#Mann= 5 ,-1 , 0
  4894.5     .07       0  4936.9     .14       0  4992.4    .045       0
  5007.6     .14       0  5110.8     .07       0
Bank Sta=4992.4,5007.6
Exp/Cntr=0.3,0.1

Type RM Length L Ch R = 1 ,70345   ,189,189,189
BEGIN DESCRIPTION:
North Deep Creek 196.0
END DESCRIPTION:
XS GIS Cut Line= 4
      1500661.06        891577.5      1500615.61       891516.24
      1500536.56       891458.93      1500431.81       891437.19
#Sta/Elev= 30
  4888.3  871.95  4891.3  871.46  4894.3  871.18  4900.9  869.46  4909.8  866.71
  4914.7  865.34  4928.2  862.29  4935.3   860.8  4949.5  858.16    4955   858.1
  4974.7  855.89  4993.3  850.67  4994.5  847.67  5005.5  847.67  5006.7  850.67
    5011  856.98  5013.9   858.3  5026.3  856.64  5032.4  855.82  5033.2  855.86
  5046.5  857.14  5052.1  858.06  5062.2  860.71  5069.1  862.07  5072.1  862.49
  5093.1  867.49  5114.9  871.85  5130.6  875.82  5145.6  878.41  5169.2  883.47
#Mann= 5 ,-1 , 0
  4888.3     .07       0  4928.2     .14       0  4993.3    .045       0
  5006.7     .14       0  5026.3     .07       0
Bank Sta=4993.3,5006.7
Exp/Cntr=0.3,0.1

Type RM Length L Ch R = 1 ,70156   ,390,390,390
BEGIN DESCRIPTION:
North Deep Creek 195.0
END DESCRIPTION:
XS GIS Cut Line= 4
       1500805.3       891439.14      1500694.66       891340.35
      1500623.51       891320.59      1500400.16       891314.66
#Sta/Elev= 30
  4886.7  877.19  4898.1  874.28    4912   872.4  4913.9   871.4  4916.4  870.93
  4930.7  867.24  4932.8  867.13  4944.6  862.08  4955.4  858.06  4978.8  853.76
  4993.3  849.62  4994.5  846.62  5005.5  846.62  5006.7  849.62    5011  855.35
  5012.8   855.8  5027.8   856.4    5047  855.73    5067  856.59  5136.7  861.96
  5161.4  864.62  5185.2  869.52  5208.3  873.43  5232.3  879.08  5249.5  883.65
  5279.3  888.58  5296.6  892.28  5302.6  892.74  5319.3  896.13  5332.3   898.2
#Mann= 5 ,-1 , 0
  4886.7     .07       0  4916.4     .14       0  4993.3    .045       0
  5006.7     .14       0    5067     .07       0
Bank Sta=4993.3,5006.7
Exp/Cntr=0.3,0.1

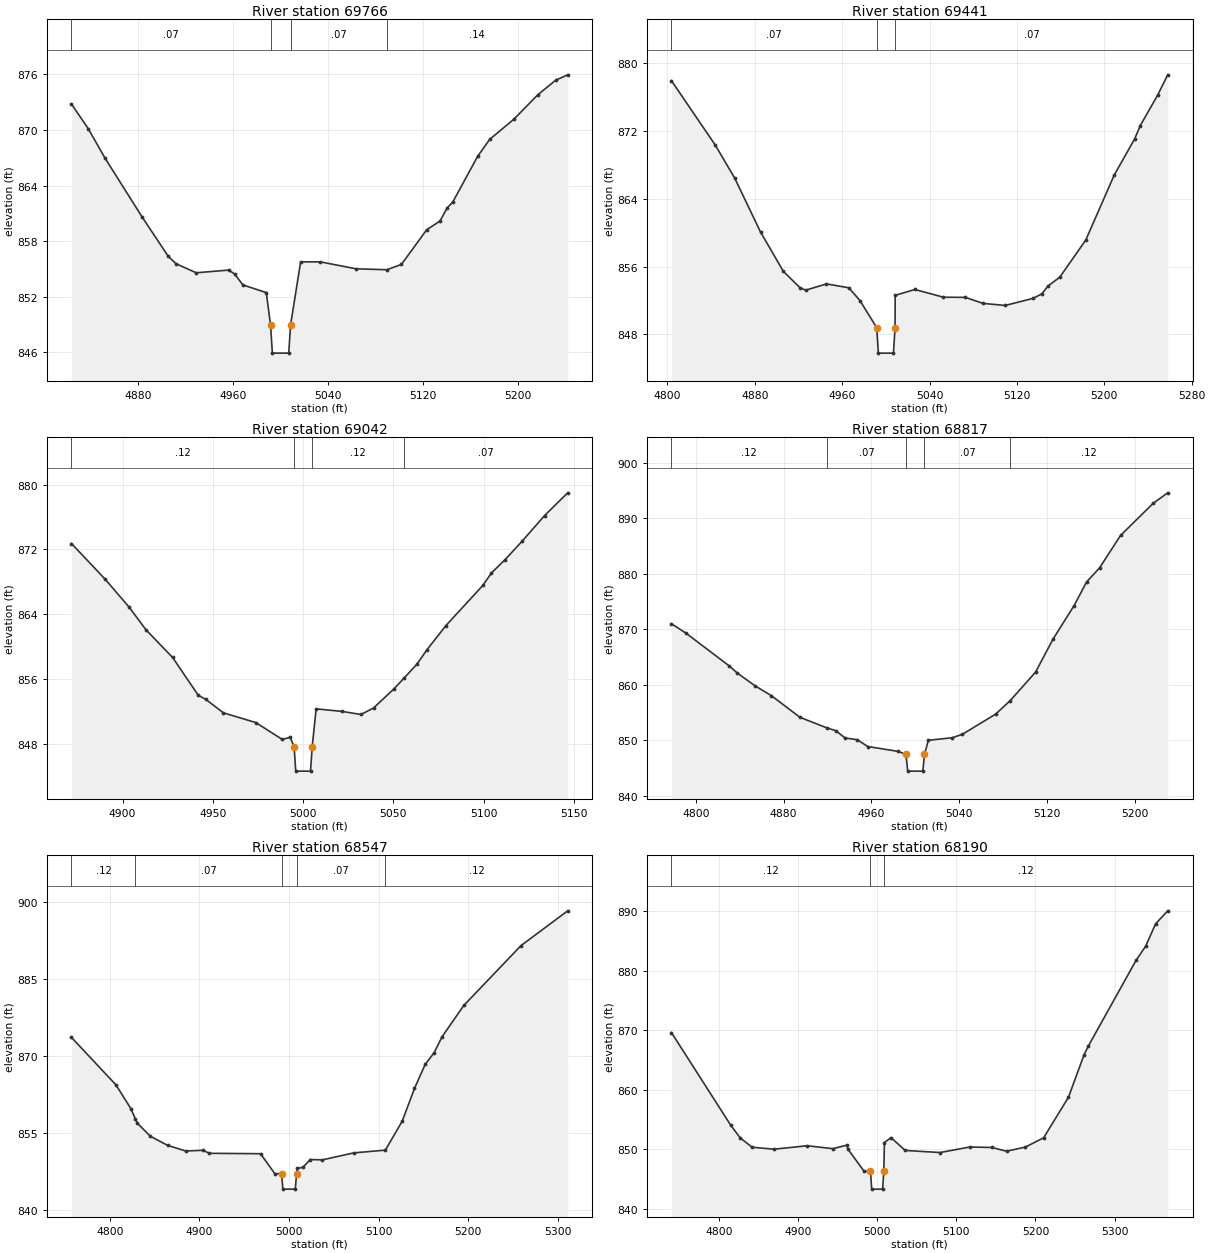
Type RM Length L Ch R = 1 ,69766   ,325,325,325
BEGIN DESCRIPTION:
North Deep Creek 193.0
END DESCRIPTION:
XS GIS Cut Line= 4
      1500961.43       891014.25      1500888.34       890990.54
      1500688.73       890986.59      1500554.37       891030.06
#Sta/Elev= 30
    4824   872.8  4838.1  870.14  4852.2  866.97  4883.3  860.64  4905.4  856.38
    4912  855.57    4929  854.59  4956.3  854.88  4961.3  854.46  4968.3  853.28
    4988  852.45  4991.6  848.92  4993.1  845.92  5006.9  845.92  5008.4  848.92
  5016.9  855.77  5033.4  855.77  5063.5  855.02  5089.6  854.92  5101.8   855.5
    5123  859.23  5134.2  860.17  5140.2  861.58  5144.9  862.21  5165.9  867.15
    5176  868.98  5196.5  871.17  5216.5  873.79  5231.6  875.37  5241.7  875.95
#Mann= 4 ,-1 , 0
    4824     .07       0  4991.6    .045       0  5008.4     .07       0
  5089.6     .14       0
Bank Sta=4991.6,5008.4
Exp/Cntr=0.3,0.1

Type RM Length L Ch R = 1 ,69441   ,399,399,399
BEGIN DESCRIPTION:
North Deep Creek 191.0
END DESCRIPTION:
XS GIS Cut Line= 5
      1501125.54       890870.02      1501054.35       890812.67
      1500927.87       890698.05      1500892.29       890634.81
      1500876.48       890516.22
#Sta/Elev= 30
  4803.7   877.9  4843.8  870.32  4861.6  866.42  4885.2  860.08  4906.1  855.44
  4921.2  853.53  4926.6  853.22  4945.6  853.96  4966.1   853.5  4976.2     852
  4991.6   848.8  4993.1   845.8  5006.9   845.8  5008.4   848.8  5008.5  852.61
  5026.5   853.3  5052.7  852.39  5072.7  852.37    5089  851.66  5109.3  851.42
  5134.9  852.26  5142.9   852.8  5148.4  853.71  5159.2  854.75    5183  859.13
  5209.1   866.8  5227.8  871.06  5232.9  872.62  5248.7  876.18    5258   878.6
#Mann= 3 ,-1 , 0
  4803.7     .07       0  4991.6    .045       0  5008.4     .07       0
Bank Sta=4991.6,5008.4
Exp/Cntr=0.3,0.1

Type RM Length L Ch R = 1 ,69042   ,225,225,225
BEGIN DESCRIPTION:
North Deep Creek 189.0
END DESCRIPTION:
XS GIS Cut Line= 4
      1501325.09       890447.05      1501251.99       890433.22
       1501159.1       890433.22      1501056.34        890401.6
#Sta/Elev= 30
  4871.7  872.72  4890.4   868.3  4903.5  864.89    4913  862.05  4927.7  858.64
  4941.9  853.97  4946.1  853.46  4955.8   851.8  4973.8  850.59  4988.5   848.5
  4992.8  848.78    4995  847.59  4995.9  844.59  5004.1  844.59    5005  847.59
  5007.2  852.29  5021.6  851.97    5032  851.59    5039   852.4  5050.3  854.76
  5055.8  856.07    5063  857.81  5068.5  859.57  5079.1  862.59  5099.5  867.54
  5104.3  869.09  5111.6  870.68  5121.2  872.99  5133.7  876.18  5146.5  878.99
#Mann= 4 ,-1 , 0
  4871.7     .12       0    4995    .045       0    5005     .12       0
  5055.8     .07       0
Bank Sta=4995,5005
Exp/Cntr=0.3,0.1

Type RM Length L Ch R = 1 ,68817   ,270,270,270
BEGIN DESCRIPTION:
North Deep Creek 188.0
END DESCRIPTION:
XS GIS Cut Line= 4
      1501437.79       890223.73      1501303.37       890207.92
      1501163.05        890209.9      1500989.14       890239.54
#Sta/Elev= 30
  4777.9     871  4790.9  869.34  4830.7  863.39  4837.7  862.16  4853.9  859.85
    4869  858.05    4895  854.16  4919.5  852.26  4927.8  851.74    4936  850.45
  4947.1  850.14  4956.7  848.91  4984.5  848.03  4991.6  847.48  4993.1  844.48
  5006.9  844.48  5008.4  847.48  5011.9  850.03  5033.4  850.48  5042.9   851.1
  5073.3  854.75  5086.5  857.17  5109.6   862.3  5125.5  868.23  5144.7  874.27
  5156.1  878.53    5168  881.08    5187  886.89  5216.6  892.65    5230  894.57
#Mann= 5 ,-1 , 0
  4777.9     .12       0  4919.5     .07       0  4991.6    .045       0
  5008.4     .07       0  5086.5     .12       0
Bank Sta=4991.6,5008.4
Exp/Cntr=0.3,0.1

Type RM Length L Ch R = 1 ,68547   ,357,357,357
BEGIN DESCRIPTION:
North Deep Creek 187.0
END DESCRIPTION:
XS GIS Cut Line= 4
      1501445.64       889962.85      1501194.67       889939.14
      1501095.86       889937.16      1500894.27       889960.88
#Sta/Elev= 30
  4757.1  873.66  4806.9  864.37  4823.3  859.79  4828.5  857.73  4830.5  856.94
  4845.2  854.37  4864.4   852.6  4884.6   851.5  4903.9  851.64    4911  851.05
  4968.1  850.97  4984.1  847.08  4991.6  847.06  4993.1  844.06  5006.9  844.06
  5008.4  847.06  5009.2   848.1  5015.5  848.33  5023.7  849.83  5037.2  849.77
  5072.1  851.13  5107.5  851.67  5126.4  857.36    5140  863.71  5151.9  868.39
  5161.9  870.67  5170.8   873.8  5195.1  879.91  5258.8  891.56    5311  898.36
#Mann= 5 ,-1 , 0
  4757.1     .12       0  4828.5     .07       0  4991.6    .045       0
  5008.4     .07       0  5107.5     .12       0
Bank Sta=4991.6,5008.4
Exp/Cntr=0.3,0.1

Type RM Length L Ch R = 1 ,68190   ,295,295,295
BEGIN DESCRIPTION:
North Deep Creek 186.0
END DESCRIPTION:
XS GIS Cut Line= 4
      1501530.65       889652.57      1501263.84       889593.28
      1501068.19       889593.28      1500917.97        889642.7
#Sta/Elev= 30
  4740.1  869.61  4814.8  854.06    4827  851.88  4842.1  850.32  4869.5  849.99
  4911.8  850.57    4944  850.08  4961.9  850.68    4963  850.02  4983.5  846.27
  4991.6  846.27  4993.1  843.27  5006.9  843.27  5008.4  846.27  5009.2  851.11
  5017.6  851.94  5035.4  849.78  5079.5  849.43  5117.2  850.36  5145.1  850.28
  5163.5  849.65  5187.4  850.35  5210.4  851.91  5241.8  858.74  5261.3  865.81
  5266.8  867.33  5327.5  881.84  5339.2  884.12  5351.9  887.92  5367.2  890.11
#Mann= 3 ,-1 , 0
  4740.1     .12       0  4991.6    .045       0  5008.4     .12       0
Bank Sta=4991.6,5008.4
Exp/Cntr=0.3,0.1

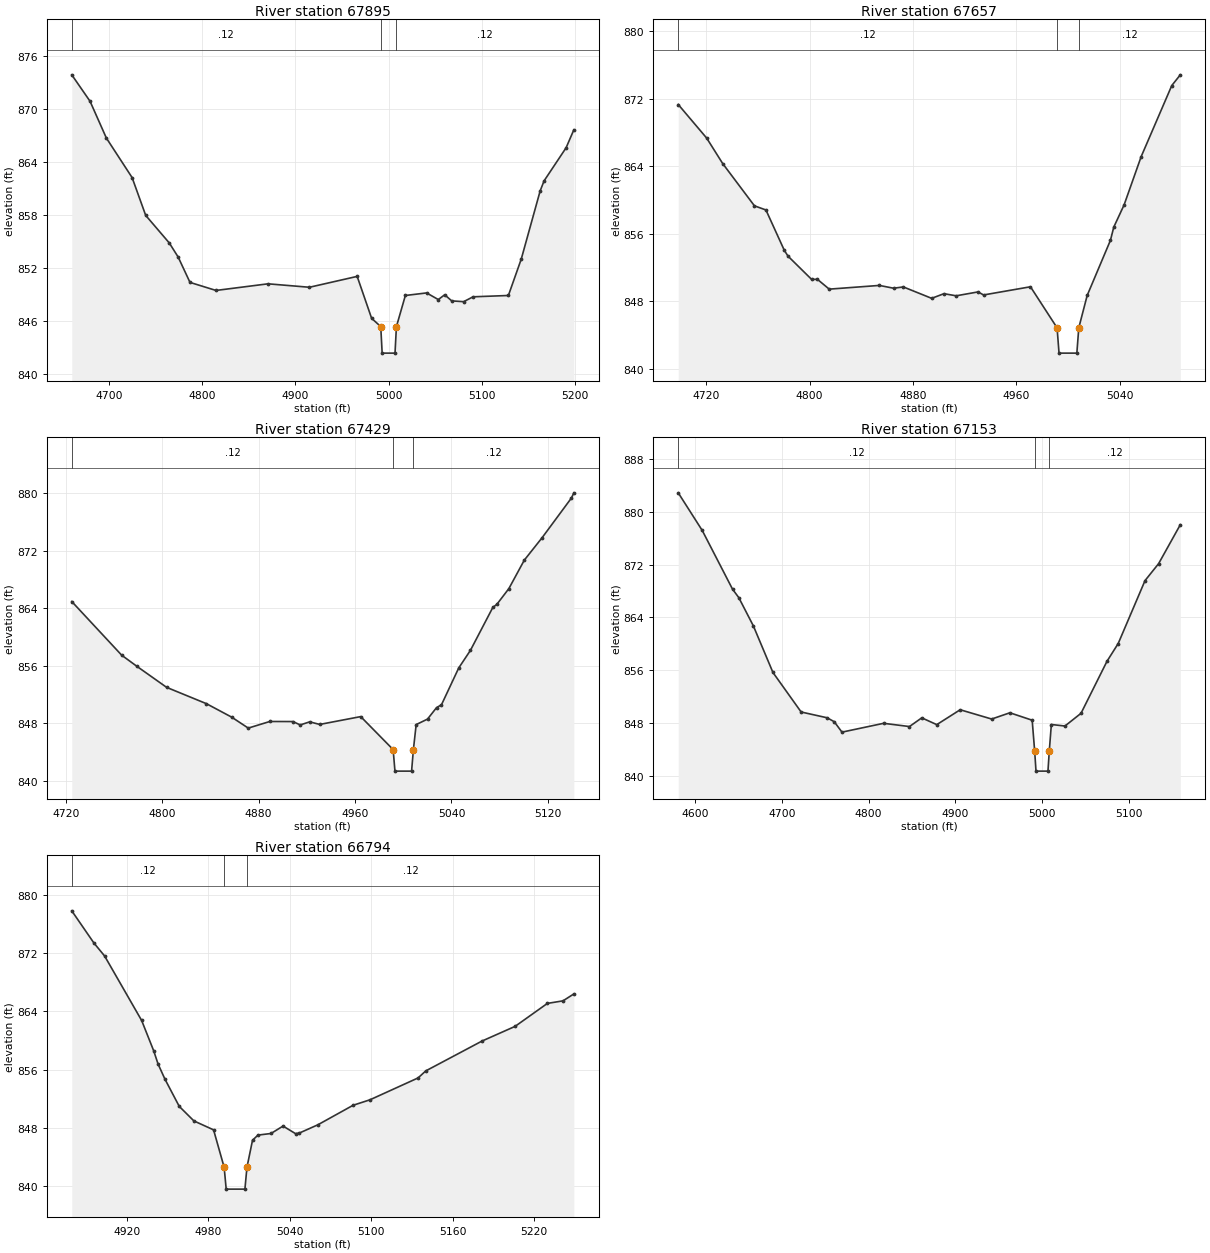
Type RM Length L Ch R = 1 ,67895   ,238,238,238
BEGIN DESCRIPTION:
North Deep Creek 185.0
END DESCRIPTION:
XS GIS Cut Line= 4
      1501659.06       889417.38      1501386.38       889346.24
      1501261.87       889255.33      1501214.44       889164.44
#Sta/Elev= 30
  4660.2  873.87  4679.8  870.88  4697.3  866.72  4724.9  862.25  4739.5  857.97
  4764.8  854.85  4774.3  853.26    4787  850.39  4814.9  849.48  4870.7  850.23
  4915.1  849.84  4966.3  851.07  4981.8  846.33  4991.6  845.39  4993.1  842.39
  5006.9  842.39  5008.4  845.39    5018  848.91  5040.8   849.2  5053.3  848.45
  5060.2  848.99  5067.7   848.3  5080.5  848.21  5090.6  848.76  5128.5  848.91
  5142.3  853.03  5162.6  860.75  5166.8  861.88  5190.4  865.62  5198.7  867.65
#Mann= 3 ,-1 , 0
  4660.2     .12       0  4991.6    .045       0  5008.4     .12       0
Bank Sta=4991.6,5008.4
Exp/Cntr=0.3,0.1

Type RM Length L Ch R = 1 ,67657   ,228,228,228
BEGIN DESCRIPTION:
North Deep Creek 184.0
END DESCRIPTION:
XS GIS Cut Line= 3
      1501726.28       889184.18      1501431.83       889097.23
      1501362.67       889053.76
#Sta/Elev= 30
  4698.3  871.33  4720.3  867.35  4732.7  864.33  4757.3  859.31  4766.2  858.82
  4780.4  854.04  4783.3  853.34  4801.6  850.58    4806   850.6  4815.2  849.43
    4854  849.87    4865  849.54  4872.6  849.69  4894.5  848.34    4904  848.89
  4913.5  848.64  4930.4   849.1  4934.7  848.74    4971  849.71  4991.6  844.84
  4993.1  841.84  5006.9  841.84  5008.4  844.84  5014.9  848.68  5032.9  855.22
  5035.5  856.79  5043.5  859.43  5056.7  865.15  5080.4  873.58    5087  874.85
#Mann= 3 ,-1 , 0
  4698.3     .12       0  4991.6    .045       0  5008.4     .12       0
Bank Sta=4991.6,5008.4
Exp/Cntr=0.3,0.1

Type RM Length L Ch R = 1 ,67429   ,276,276,276
BEGIN DESCRIPTION:
North Deep Creek 183.0
END DESCRIPTION:
XS GIS Cut Line= 4
      1501795.45       889043.86      1501676.89       888994.46
      1501540.53       888899.59      1501423.89       888864.01
#Sta/Elev= 30
    4725  864.92  4766.4  857.45  4779.1  855.89  4803.7  852.97  4836.7   850.7
  4857.7  848.82  4871.4   847.3  4889.3  848.22  4908.5  848.21  4914.5  847.74
  4922.4  848.17  4930.7  847.81  4964.7   848.9  4991.6  844.31  4993.1  841.31
  5006.9  841.31  5008.4  844.31  5010.7  847.79  5020.1  848.55  5027.6  850.15
  5031.7  850.55    5046  855.67  5055.7  858.12  5074.3   864.1  5077.6  864.52
  5087.6  866.72  5100.4  870.68  5115.2  873.81  5139.5  879.33  5141.5  880.05
#Mann= 3 ,-1 , 0
    4725     .12       0  4991.6    .045       0  5008.4     .12       0
Bank Sta=4991.6,5008.4
Exp/Cntr=0.3,0.1

Type RM Length L Ch R = 1 ,67153   ,359,359,359
BEGIN DESCRIPTION:
North Deep Creek 182.0
END DESCRIPTION:
XS GIS Cut Line= 5
      1501957.57       888956.94      1501840.93       888869.95
      1501661.08       888670.34      1501619.58       888632.79
      1501516.82       888597.22
#Sta/Elev= 30
  4580.6  882.93  4608.3  877.21  4643.2   868.3  4650.4  867.02  4667.2  862.73
  4689.8  855.65  4722.3  849.65  4752.3  848.77  4760.5  848.17  4769.4  846.59
  4817.4  847.93  4847.2  847.44  4861.4  848.76  4878.7  847.73  4905.7  849.99
    4942  848.58    4963  849.53  4988.7   848.4  4991.6  843.67  4993.1  840.67
  5006.9  840.67  5008.4  843.67  5010.8  847.75  5026.5  847.52    5045  849.45
    5075  857.36  5087.9  860.05  5118.8   869.6  5134.5  872.18  5159.5  878.09
#Mann= 3 ,-1 , 0
  4580.6     .12       0  4991.6    .045       0  5008.4     .12       0
Bank Sta=4991.6,5008.4
Exp/Cntr=0.3,0.1

Type RM Length L Ch R = 1 ,66794   ,230,230,230
BEGIN DESCRIPTION:
North Deep Creek 181.0
END DESCRIPTION:
XS GIS Cut Line= 4
      1502078.07       888721.71      1501969.39       888644.65
      1501941.72       888593.26      1501955.56       888415.39
#Sta/Elev= 30
  4879.3  877.82  4895.6   873.4  4903.5  871.61  4930.8  862.74  4939.7  858.56
  4942.9  856.75    4948  854.66  4958.5  850.93  4969.3  848.93  4983.8   847.7
  4991.6  842.55  4993.1  839.55  5006.9  839.55  5008.4  842.55  5012.5  846.27
  5016.5  846.98  5026.1   847.2    5035  848.22  5044.2  847.18  5047.1  847.27
  5060.7   848.4  5086.6  851.08    5099  851.83  5134.5  854.84  5140.2  855.81
  5181.6  859.91    5206  861.93  5229.8  865.09  5241.3  865.44  5249.3  866.39
#Mann= 3 ,-1 , 0
  4879.3     .12       0  4991.6    .045       0  5008.4     .12       0
Bank Sta=4991.6,5008.4
Exp/Cntr=0.3,0.1