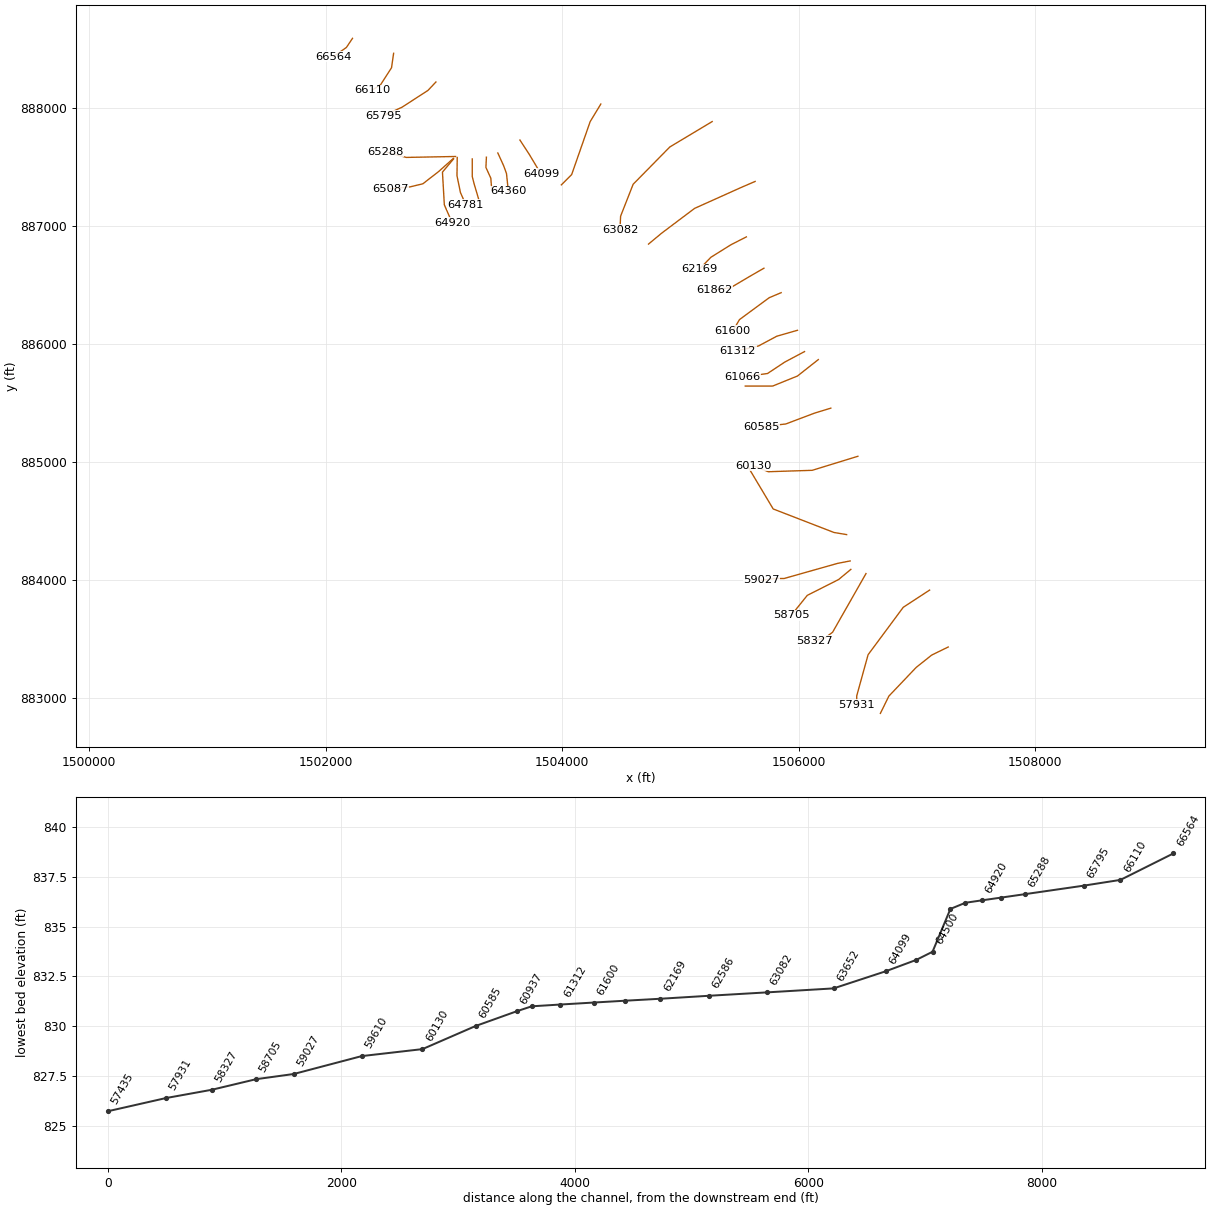
HEC-RAS study North Deep Creek.prj: North Deep Creek Limited Detail Study

--- North Deep Creek.g01 (geometry) --- (continued)

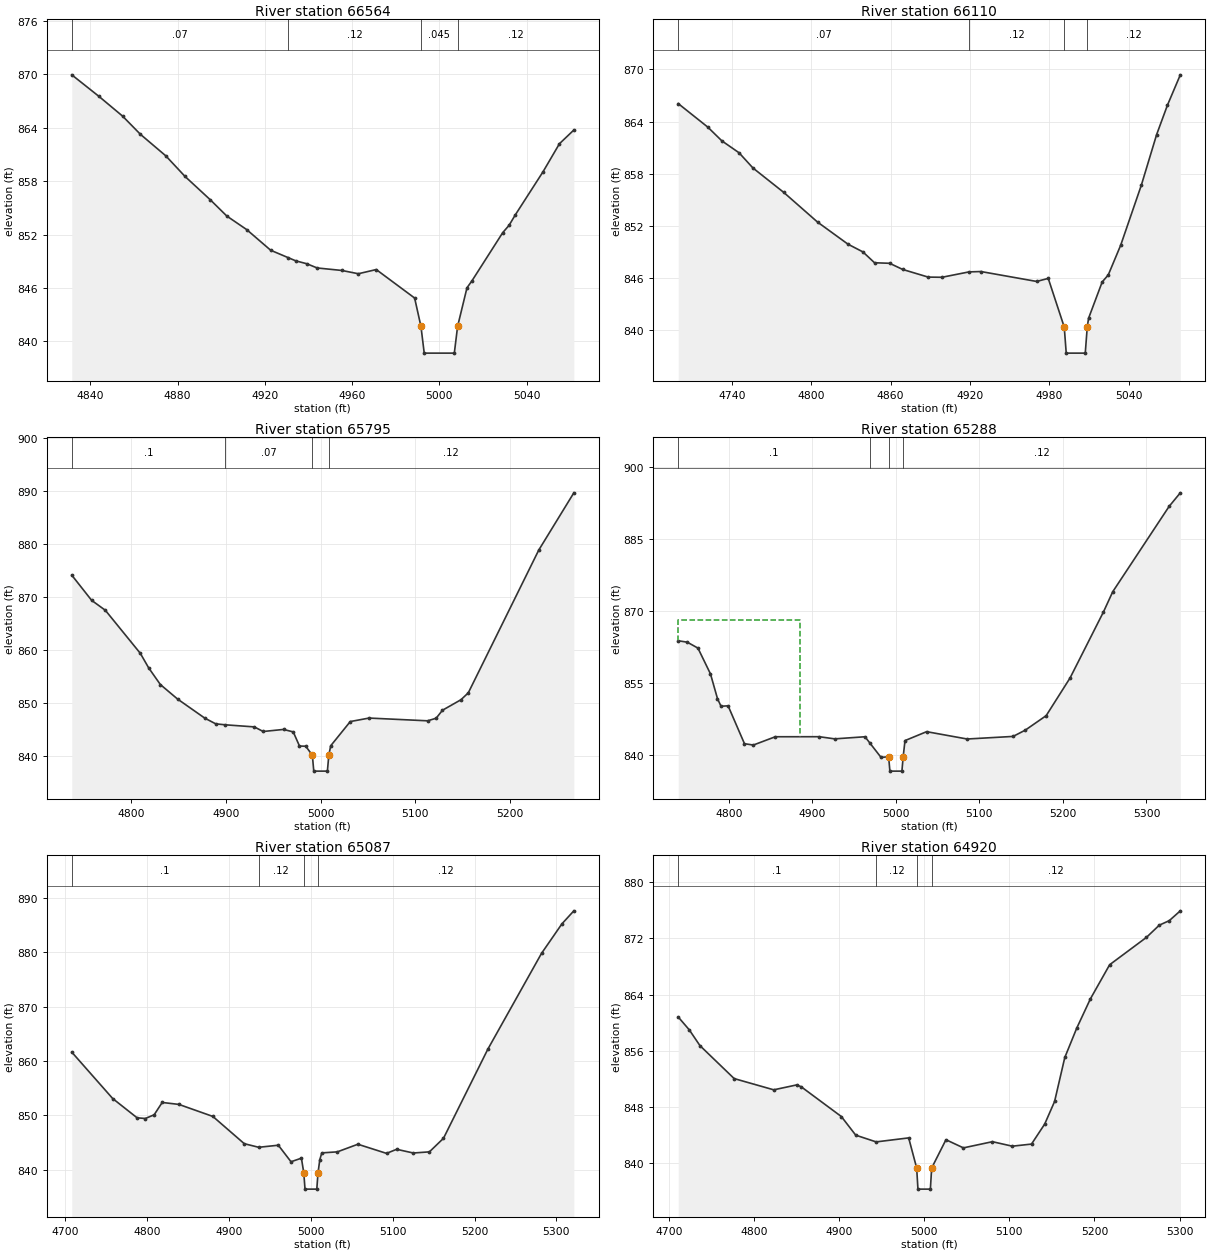
Type RM Length L Ch R = 1 ,66564   ,454,454,454
BEGIN DESCRIPTION:
North Deep Creek 180.0
END DESCRIPTION:
XS GIS Cut Line= 3
       1502226.3       888587.31      1502174.93       888510.26
       1502062.3       888431.22
#Sta/Elev= 30
  4831.5  869.95  4843.9  867.54  4854.8  865.31    4863  863.26  4874.6  860.85
  4883.4  858.54  4895.1  855.89  4902.6  854.08  4911.7  852.56  4922.7  850.24
  4930.8   849.4  4934.2  849.05  4939.3  848.72    4944  848.25  4955.3  847.97
  4962.9   847.6  4971.1  848.07  4988.7  844.87  4991.6  841.68  4993.1  838.68
  5006.9  838.68  5008.4  841.68  5012.7  846.02    5015  846.81  5029.1  852.22
    5032  853.04  5034.9  854.23  5047.6  859.07  5055.1  862.21  5061.7  863.75
#Mann= 4 ,-1 , 0
  4831.5     .07       0  4930.8     .12       0  4991.6    .045       0
  5008.4     .12       0
Bank Sta=4991.6,5008.4
Exp/Cntr=0.3,0.1

Type RM Length L Ch R = 1 ,66110   ,315,315,315
BEGIN DESCRIPTION:
North Deep Creek 179.0
END DESCRIPTION:
XS GIS Cut Line= 4
      1502574.14       888460.85      1502556.36       888338.32
      1502463.47       888194.05      1502392.35       888148.61
#Sta/Elev= 30
  4699.3  866.07  4721.6  863.37  4732.3  861.78  4745.3  860.41  4755.8  858.66
  4779.1  855.85  4804.7  852.43  4827.7  849.89    4839     849  4847.8  847.75
  4859.2  847.69  4869.1  846.98  4888.4   846.1  4898.8  846.08  4919.3   846.7
  4928.3  846.74  4970.4   845.6  4979.2  845.95  4991.3  840.35  4992.8  837.35
  5007.2  837.35  5008.7  840.35  5009.7  841.36    5020  845.54  5024.6  846.35
    5034  849.77  5049.6  856.67  5061.2  862.51  5069.4   865.9  5079.1  869.38
#Mann= 4 ,-1 , 0
  4699.3     .07       0  4919.3     .12       0  4991.3    .045       0
  5008.7     .12       0
Bank Sta=4991.3,5008.7
Exp/Cntr=0.3,0.1

Type RM Length L Ch R = 1 ,65795   ,507,507,507
BEGIN DESCRIPTION:
North Deep Creek 178.0
END DESCRIPTION:
XS GIS Cut Line= 4
      1502931.86       888217.76      1502864.66       888146.62
      1502645.29       888004.32      1502489.18       887933.18
#Sta/Elev= 30
  4736.9   874.1  4757.9  869.34  4772.4  867.46  4809.4  859.32  4818.2  856.58
  4830.6  853.42  4848.8  850.68  4877.6  847.07  4889.1     846  4898.8  845.82
  4929.9  845.42  4939.3  844.55  4960.8  844.94  4971.1  844.47  4977.7   841.8
  4984.3  841.77  4991.3  840.06  4992.8  837.06  5007.2  837.06  5008.7  840.06
  5010.7  841.85  5031.4  846.43  5051.3  847.09  5113.2  846.57  5122.2  847.06
  5128.9  848.57  5148.4  850.55  5156.2  851.86  5230.7  878.84  5267.8  889.66
#Mann= 4 ,-1 , 0
  4736.9      .1       0  4898.8     .07       0  4991.3    .045       0
  5008.7     .12       0
Bank Sta=4991.3,5008.7
Exp/Cntr=0.3,0.1

Type RM Length L Ch R = 1 ,65288   ,201,201,201
BEGIN DESCRIPTION:
North Deep Creek 177.0
END DESCRIPTION:
XS GIS Cut Line= 3
      1503097.85       887587.32      1502680.87       887579.41
      1502503.04       887626.83
#Sta/Elev= 30
  4739.4  863.82  4750.2  863.53    4763  862.29    4778  856.91  4786.4  851.74
  4790.6  850.17  4799.1  850.25  4818.7  842.35  4829.3  842.07  4855.6   843.8
  4908.2  843.81  4926.7  843.36    4963   843.8  4968.8   842.5  4982.2  839.49
  4991.3  839.63  4992.8  836.63  5007.2  836.63  5008.7  839.63  5010.9     843
  5036.8  844.86  5085.3  843.33  5140.3  843.87  5154.9  845.18  5179.9   848.2
  5208.5  856.06  5248.5  869.84  5259.6  874.05  5327.1  891.85  5340.5  894.68
#Mann= 4 ,-1 , 0
  4739.4      .1       0  4968.8     .12       0  4991.3    .045       0
  5008.7     .12       0
#XS Ineff= 2 , 0
       0  4884.8  868.19               0
Permanent Ineff=
       F       F
Bank Sta=4991.3,5008.7
Exp/Cntr=0.3,0.1

Type RM Length L Ch R = 1 ,65087   ,167,167,167
BEGIN DESCRIPTION:
North Deep Creek 176.0
END DESCRIPTION:
XS GIS Cut Line= 5
       1503080.1       887571.52       1502953.6       887458.86
      1502821.19       887356.09      1502714.46       887330.39
       1502548.5       887314.59
#Sta/Elev= 30
  4707.8  861.64  4757.8  853.11  4787.6  849.57  4797.7  849.44  4808.5  850.13
  4818.3  852.39  4838.7  852.03  4880.2  849.82  4918.6  844.81  4936.2  844.15
  4960.2  844.53  4975.7  841.49  4988.4  842.15  4991.3  839.46  4992.8  836.46
  5007.2  836.46  5008.7  839.46  5010.9  841.88  5013.3  843.12  5032.3  843.31
  5057.4  844.71  5092.4  843.03  5104.8  843.78  5125.1   843.1  5144.8  843.31
    5162   845.8  5216.2  862.18  5281.8  879.79  5306.7  885.21  5321.3  887.61
#Mann= 4 ,-1 , 0
  4707.8      .1       0  4936.2     .12       0  4991.3    .045       0
  5008.7     .12       0
Bank Sta=4991.3,5008.7
Exp/Cntr=0.3,0.1

Type RM Length L Ch R = 1 ,64920   ,139,139,139
BEGIN DESCRIPTION:
North Deep Creek 175.0
END DESCRIPTION:
XS GIS Cut Line= 4
      1503080.07       887565.55       1502987.2        887454.9
      1503003.01       887178.22      1503070.22       887024.03
#Sta/Elev= 30
  4711.1  860.81  4724.1  858.98  4736.6  856.74  4776.8  852.05  4823.3  850.45
  4850.3  851.15  4855.6  850.88  4902.7  846.65  4919.6     844  4943.6  843.04
  4981.8  843.61  4991.2  839.32  4992.7  836.32  5007.3  836.32  5008.8  839.32
  5025.6  843.35  5046.1  842.19  5080.2  843.07  5103.5  842.43  5126.1  842.73
  5141.6  845.58  5153.2  848.79  5165.2  855.05  5179.2  859.22  5195.3   863.4
  5217.9  868.25  5261.1  872.14  5276.2  873.88  5287.9  874.52  5300.9  875.92
#Mann= 4 ,-1 , 0
  4711.1      .1       0  4943.6     .12       0  4991.2    .045       0
  5008.8     .12       0
Bank Sta=4991.2,5008.8
Exp/Cntr=0.5,0.3

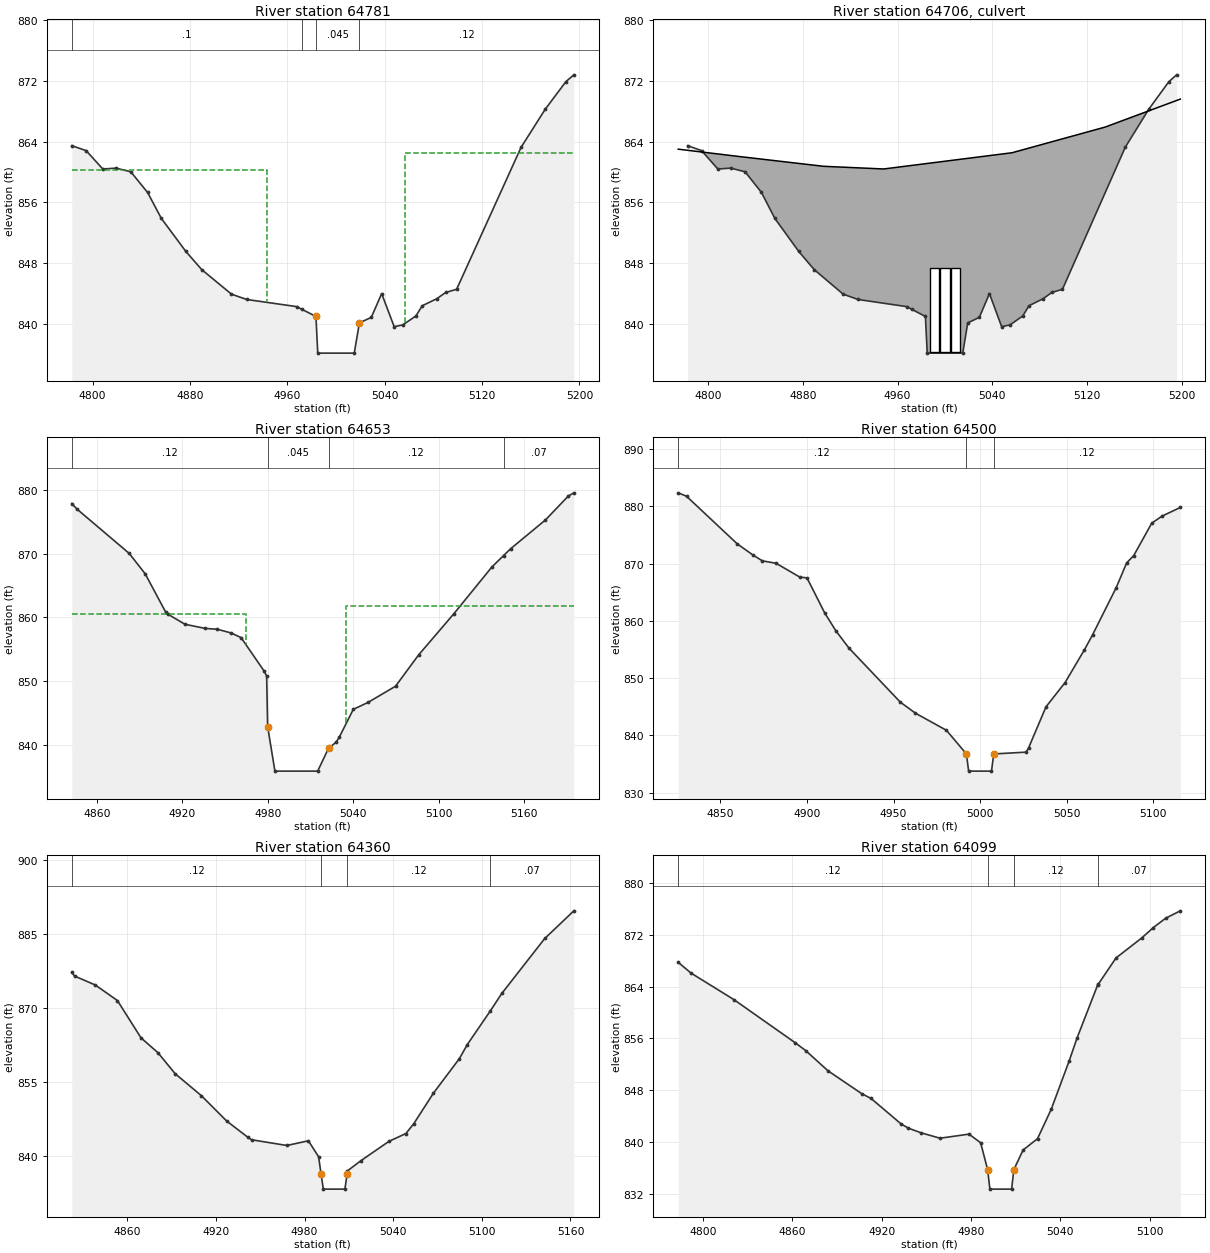
Type RM Length L Ch R = 1 ,64781   ,128,128,128
BEGIN DESCRIPTION:
US 601 (NDC) us
END DESCRIPTION:
XS GIS Cut Line= 4
      1503112.19       887578.75      1503109.93       887424.68
      1503139.39       887281.89      1503184.71       887178.79
#Sta/Elev= 30
  4782.9  863.46  4794.7  862.81  4808.4  860.39  4819.2  860.51  4831.4  860.03
  4845.2  857.31  4856.5   853.9  4876.6  849.57  4889.7  847.17  4914.1  843.95
  4926.6  843.25  4967.7  842.31  4971.9  841.96  4983.5  841.02    4985   836.2
    5015   836.2  5019.2  840.17    5029   840.9  5037.5  844.02  5047.8  839.67
  5054.9  839.91  5065.6  841.08  5070.9  842.43  5082.8  843.35  5090.1  844.17
  5099.1  844.59  5152.1  863.26  5171.9  868.25  5188.9  871.88  5195.4  872.77
#Mann= 4 ,-1 , 0
  4782.9      .1       0  4971.9     .12       0  4983.5    .045       0
  5019.2     .12       0
#XS Ineff= 2 , 0
       0    4943   860.3    5057       0  862.56
Permanent Ineff=
       F       F
Bank Sta=4983.5,5019.2
Exp/Cntr=0.5,0.3

Type RM Length L Ch R = 2 ,64706   ,,,
BEGIN DESCRIPTION:
US 601 (NDC) tor
Structure ID: LDS_NDC_14
Approximate Survey Structure
END DESCRIPTION:
Bridge Culvert--1,0,-1,-1, 0
Deck Dist Width WeirC Skew NumUp NumDn MinLoCord MaxHiCord MaxSubmerge Is_Ogee
44,62,3,0, 7, 7, , , 0.95, 0, 1,1,,
    4775  4827.3  4897.6  4948.3  5056.5  5135.2  5198.5
     863  862.02  860.75   860.4  862.53  865.91  869.58
   816.2   816.2   816.2   816.2   816.2   816.2   816.2
    4775  4827.3  4897.6  4948.3  5056.5  5135.2  5198.5
     863  862.02  860.75   860.4  862.53  865.91  869.58
  815.89  815.89  815.89  815.89  815.89  815.89  815.89
Culvert=2,11,8,62,0.012,0.4,1,8,1,836.4,4991,836.09,4991,Culvert #1  , 0 ,44
Culvert Bottom n=0.012
Culvert=2,11,8,62,0.012,0.4,1,8,1,836.4,5000,836.09,5000,Culvert #2  , 0 ,44
Culvert Bottom n=0.012
Culvert=2,11,8,62,0.012,0.4,1,8,1,836.4,5009,836.09,5009,Culvert #3  , 0 ,44
Culvert Bottom n=0.012
BC Design=,, 0 ,, 0 ,,,,,,
BC HTab HWMax=872.77

Type RM Length L Ch R = 1 ,64653   ,153,153,153
BEGIN DESCRIPTION:
US 601 (NDC) ds
END DESCRIPTION:
XS GIS Cut Line= 4
      1503239.11       887566.28      1503239.11       887417.88
      1503254.97       887355.55      1503294.64       887221.83
#Sta/Elev= 30
  4842.5  877.85  4846.2  876.97  4882.8  870.03    4894  866.83  4908.3  860.86
  4909.7  860.53  4921.9  858.92  4936.3  858.26  4944.6  858.14  4954.2  857.56
  4961.3  856.82  4977.4  851.59  4979.2  850.81  4979.9  842.88    4985  835.89
    5015  835.89  5022.6  839.47  5027.9  840.42  5030.1  841.19    5040  845.58
  5050.3  846.66  5069.6   849.2  5085.8  854.11  5110.5  860.56  5137.4  867.95
  5145.4  869.69  5150.4  870.77  5174.8  875.28  5190.8  879.02  5194.7  879.53
#Mann= 4 ,-1 , 0
  4842.5     .12       0  4979.9    .045       0  5022.6     .12       0
  5145.4     .07       0
#XS Ineff= 2 , 0
       0    4965  860.55    5035       0  861.79
Permanent Ineff=
       F       F
Bank Sta=4979.9,5022.6
Exp/Cntr=0.5,0.3

Type RM Length L Ch R = 1 ,64500   ,140,140,140
BEGIN DESCRIPTION:
North Deep Creek 174.0
END DESCRIPTION:
XS GIS Cut Line= 4
      1503358.75       887581.42      1503354.79       887494.43
      1503396.29       887403.52       1503404.2       887300.73
#Sta/Elev= 30
  4825.6  882.38  4830.4  881.78  4859.7  873.46  4868.6  871.55  4874.2  870.49
  4882.1  870.07  4895.8  867.66    4900  867.51  4910.2  861.41  4916.6   858.3
  4924.2  855.26  4953.9   845.8  4962.6  843.88  4980.6  840.87  4992.1  836.74
  4993.4  833.74  5006.6  833.74  5007.9  836.74  5026.6  837.06  5028.1  837.85
  5038.1  844.98  5049.1  849.21  5060.2   854.9    5065  857.56  5078.7  865.83
  5084.7  870.13  5088.8  871.42  5099.2  877.08  5105.2  878.32  5115.7  879.82
#Mann= 3 ,-1 , 0
  4825.6     .12       0  4992.1    .045       0  5007.9     .12       0
Bank Sta=4992.1,5007.9
Exp/Cntr=0.3,0.1

Type RM Length L Ch R = 1 ,64360   ,261,261,261
BEGIN DESCRIPTION:
North Deep Creek 173.0
END DESCRIPTION:
XS GIS Cut Line= 4
      1503455.57         887617.      1503504.99       887508.26
      1503528.71       887443.04      1503544.52       887292.81
#Sta/Elev= 30
  4822.4  877.25  4824.3  876.53  4838.4   874.7  4853.3  871.56  4869.3  863.99
  4880.7     861  4892.4  856.73  4910.2  852.26  4927.3  847.13  4941.8   843.8
  4944.1  843.34    4968  842.18  4982.6  843.13  4989.5  839.89  4991.2  836.33
  4992.7  833.33  5007.3  833.33  5008.8  836.33  5008.9     837  5018.2  839.11
  5037.1  843.01  5048.6   844.6  5053.9  846.58  5067.2  852.77  5084.8  859.78
  5090.2  862.65  5105.7  869.43  5113.5  872.99  5142.6  884.14  5162.3  889.75
#Mann= 4 ,-1 , 0
  4822.4     .12       0  4991.2    .045       0  5008.8     .12       0
  5105.7     .07       0
Bank Sta=4991.2,5008.8
Exp/Cntr=0.3,0.1

Type RM Length L Ch R = 1 ,64099   ,447,447,447
BEGIN DESCRIPTION:
North Deep Creek 172.0
END DESCRIPTION:
XS GIS Cut Line= 3
      1503642.46       887726.31      1503722.04       887604.28
      1503820.19       887439.82
#Sta/Elev= 30
  4783.4  867.73    4792  866.07  4820.8  861.98  4861.9  855.34  4869.1   854.1
    4884     851  4906.7  847.47  4912.9  846.74  4933.2  842.79    4938  842.16
  4946.4  841.45  4959.2  840.61  4978.7  841.24  4986.5  839.91  4991.2  835.76
  4992.7  832.76  5007.3  832.76  5008.8  835.76    5015  838.79  5024.7  840.54
  5033.9  845.07  5045.9  852.49  5051.2  856.03    5065  864.18  5065.4  864.32
  5077.4   868.4  5094.6  871.47  5102.5  873.09  5110.7  874.52  5120.6  875.67
#Mann= 4 ,-1 , 0
  4783.4     .12       0  4991.2    .045       0  5008.8     .12       0
  5065.4     .07       0
Bank Sta=4991.2,5008.8
Exp/Cntr=0.3,0.1

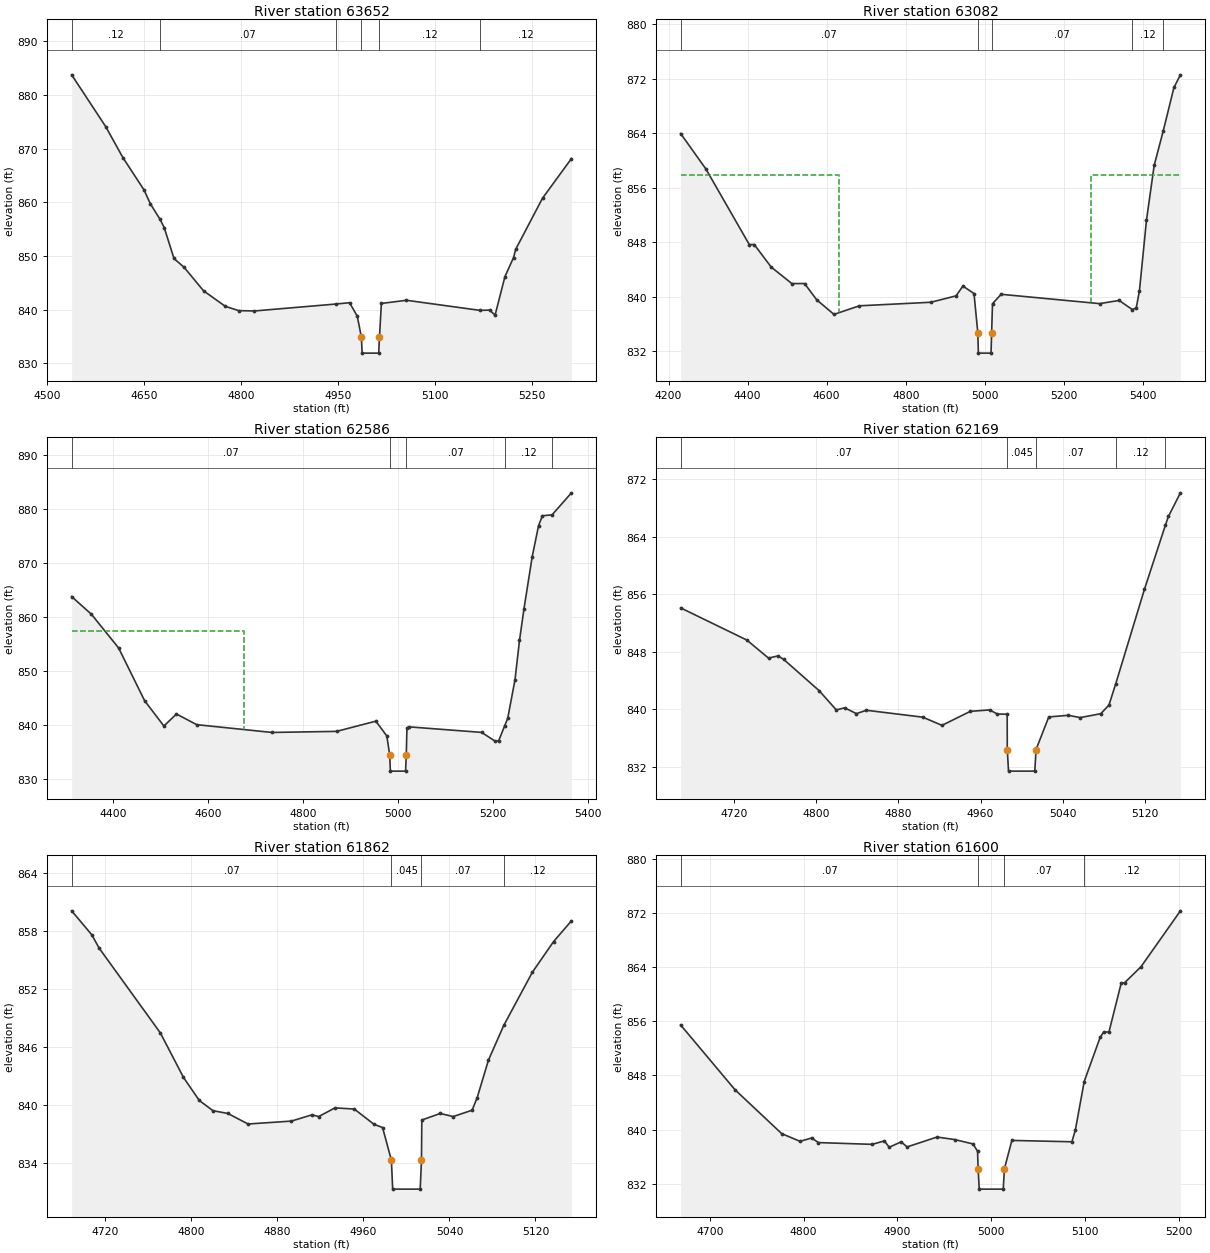
Type RM Length L Ch R = 1 ,63652   ,570,570,570
BEGIN DESCRIPTION:
North Deep Creek 171.0
END DESCRIPTION:
XS GIS Cut Line= 4
      1504326.72       888031.24      1504236.56       887882.75
      1504080.09       887434.54      1503992.59       887347.04
#Sta/Elev= 30
  4538.4  883.72    4591  874.08  4617.5  868.32  4650.1  862.31  4660.1  859.68
  4674.8  856.85  4681.4  855.28  4696.5  849.52  4712.1  847.88  4742.2   843.5
  4775.9  840.61  4796.6  839.81  4820.7  839.75  4946.5  841.04  4967.8  841.29
  4979.7  838.77    4986   834.9  4987.2   831.9  5012.8   831.9    5014   834.9
  5016.9  841.15  5055.7  841.74  5169.4  839.86  5184.1  839.91  5192.6  838.98
  5207.8  846.14  5221.1  849.69  5224.6  851.27  5265.9  860.75  5310.6  868.13
#Mann= 6 ,-1 , 0
  4538.4     .12       0  4674.8     .07       0  4946.5     .12       0
    4986    .045       0    5014     .12       0  5169.4     .12       0
Bank Sta=4986,5014
Exp/Cntr=0.3,0.1

Type RM Length L Ch R = 1 ,63082   ,496,496,496
BEGIN DESCRIPTION:
North Deep Creek 170.0
END DESCRIPTION:
XS GIS Cut Line= 5
      1505268.29       887882.77      1504910.21       887667.93
      1504599.91       887352.32      1504493.82        887081.8
      1504488.52       886967.79
#Sta/Elev= 30
  4230.4  863.95  4294.4  858.74  4404.2  847.64  4416.7  847.65  4459.6  844.34
    4512  841.91  4544.1  841.92  4574.9  839.52  4618.5  837.39  4682.9  838.65
  4863.6  839.17  4927.5  840.11  4944.8  841.55  4972.9  840.45  4982.5   834.7
    4984   831.7    5016   831.7  5017.5   834.7  5019.7  838.96  5041.6  840.34
  5290.7  838.97  5340.2  839.44  5373.5   838.1  5383.5  838.35  5391.5  840.82
  5409.4  851.23  5428.9  859.28  5451.9  864.35  5478.9  870.71  5495.3  872.57
#Mann= 5 ,-1 , 0
  4230.4     .07       0  4982.5    .045       0  5017.5     .07       0
  5373.5     .12       0  5451.9     .07       0
#XS Ineff= 2 , 0
       0  4632.4  857.79  5268.3       0  857.79
Permanent Ineff=
       F       F
Bank Sta=4982.5,5017.5
Exp/Cntr=0.3,0.1

Type RM Length L Ch R = 1 ,62586   ,417,417,417
BEGIN DESCRIPTION:
North Deep Creek 169.0
END DESCRIPTION:
XS GIS Cut Line= 5
      1505631.64       887376.21       1505514.9        887325.8
      1505119.73        887148.1      1504841.25       886938.58
      1504729.89       886845.78
#Sta/Elev= 30
  4311.9   863.8  4353.6  860.53  4410.9   854.3  4465.8  844.54  4506.4  839.87
  4532.9  842.09  4575.6  840.12  4734.2  838.68  4870.7  838.88  4953.3  840.77
  4976.5  838.03  4982.5  834.53    4984  831.53    5016  831.53  5017.5  834.53
  5018.9  839.53  5023.7  839.71  5176.5  838.69  5205.5  837.03  5212.5  837.18
    5225  839.92  5231.3  841.26  5246.7  848.39  5256.2  855.68  5265.7  861.55
    5283  871.15  5296.4   876.9  5304.5  878.74  5324.9  878.91  5365.8  882.98
#Mann= 5 ,-1 , 0
  4311.9     .07       0  4982.5    .045       0  5017.5     .07       0
    5225     .12       0  5324.9     .07       0
#XS Ineff= 2 , 0
       0  4674.8  857.44               0
Permanent Ineff=
       F       F
Bank Sta=4982.5,5017.5
Exp/Cntr=0.3,0.1

Type RM Length L Ch R = 1 ,62169   ,307,307,307
BEGIN DESCRIPTION:
North Deep Creek 168.0
END DESCRIPTION:
XS GIS Cut Line= 4
      1505557.36       886906.77      1505427.38       886840.45
      1505257.64       886734.37      1505159.55       886633.62
#Sta/Elev= 30
  4667.9   854.1  4732.4  849.62  4753.5  847.11  4762.6  847.41  4768.2  846.94
  4802.7  842.59  4819.5   839.9  4827.7  840.19  4839.1  839.38  4848.8  839.85
  4903.7  838.89  4922.4  837.75    4950   839.7  4968.9   839.9  4976.2  839.33
  4985.9   839.3    4986  834.38  4987.2  831.38  5012.8  831.38    5014  834.38
  5026.4  838.92  5045.4  839.15    5057  838.83    5077  839.37    5085  840.57
  5091.4  843.44  5119.6   856.7    5140  865.62  5142.9  866.82  5154.6  870.11
#Mann= 5 ,-1 , 0
  4667.9     .07       0    4986    .045       0    5014     .07       0
  5091.4     .12       0    5140     .07       0
Bank Sta=4986,5014
Exp/Cntr=0.3,0.1

Type RM Length L Ch R = 1 ,61862   ,262,262,262
BEGIN DESCRIPTION:
North Deep Creek 167.0
END DESCRIPTION:
XS GIS Cut Line= 4
      1505705.87       886641.55      1505599.77       886580.54
      1505424.73       886477.11      1505286.78       886458.54
#Sta/Elev= 30
  4688.6  860.12  4707.3  857.64  4714.2  856.25  4771.1  847.47  4792.6  842.86
  4807.3  840.47    4820  839.41  4833.9  839.12  4852.7  838.03    4893  838.33
  4912.1  838.98  4918.4   838.8  4933.5   839.7  4951.5  839.58  4969.8     838
  4977.8  837.66    4986  834.28  4987.2  831.28  5012.8  831.28    5014  834.28
  5014.3  838.44  5031.4  839.12  5043.5   838.8  5061.1  839.46  5065.8  840.76
  5076.3  844.65  5090.5  848.24  5117.1  853.75  5136.9  856.94  5153.5  859.08
#Mann= 4 ,-1 , 0
  4688.6     .07       0    4986    .045       0    5014     .07       0
  5090.5     .12       0
Bank Sta=4986,5014
Exp/Cntr=0.3,0.1

Type RM Length L Ch R = 1 ,61600   ,288,288,288
BEGIN DESCRIPTION:
North Deep Creek 166.0
END DESCRIPTION:
XS GIS Cut Line= 4
      1505851.73       886434.68      1505750.95       886392.24
      1505498.99       886206.59      1505443.27       886111.08
#Sta/Elev= 30
  4668.8  855.46  4726.8  845.88  4776.6  839.39  4796.1  838.26  4808.6  838.75
  4815.7  838.07    4873  837.81  4886.1  838.32  4891.2  837.38  4903.9  838.18
  4910.3  837.43  4942.2  838.89    4961  838.52  4980.5  837.87  4985.4   836.8
    4986  834.19  4987.2  831.19  5012.8  831.19    5014  834.19    5022  838.39
    5086  838.19  5089.7  839.94  5099.1   847.1  5116.1  853.62  5119.8  854.41
  5125.5  854.42  5138.6  861.66  5142.1  861.69  5159.7  864.07  5201.7  872.33
#Mann= 4 ,-1 , 0
  4668.8     .07       0    4986    .045       0    5014     .07       0
  5099.1     .12       0
Bank Sta=4986,5014
Exp/Cntr=0.3,0.1

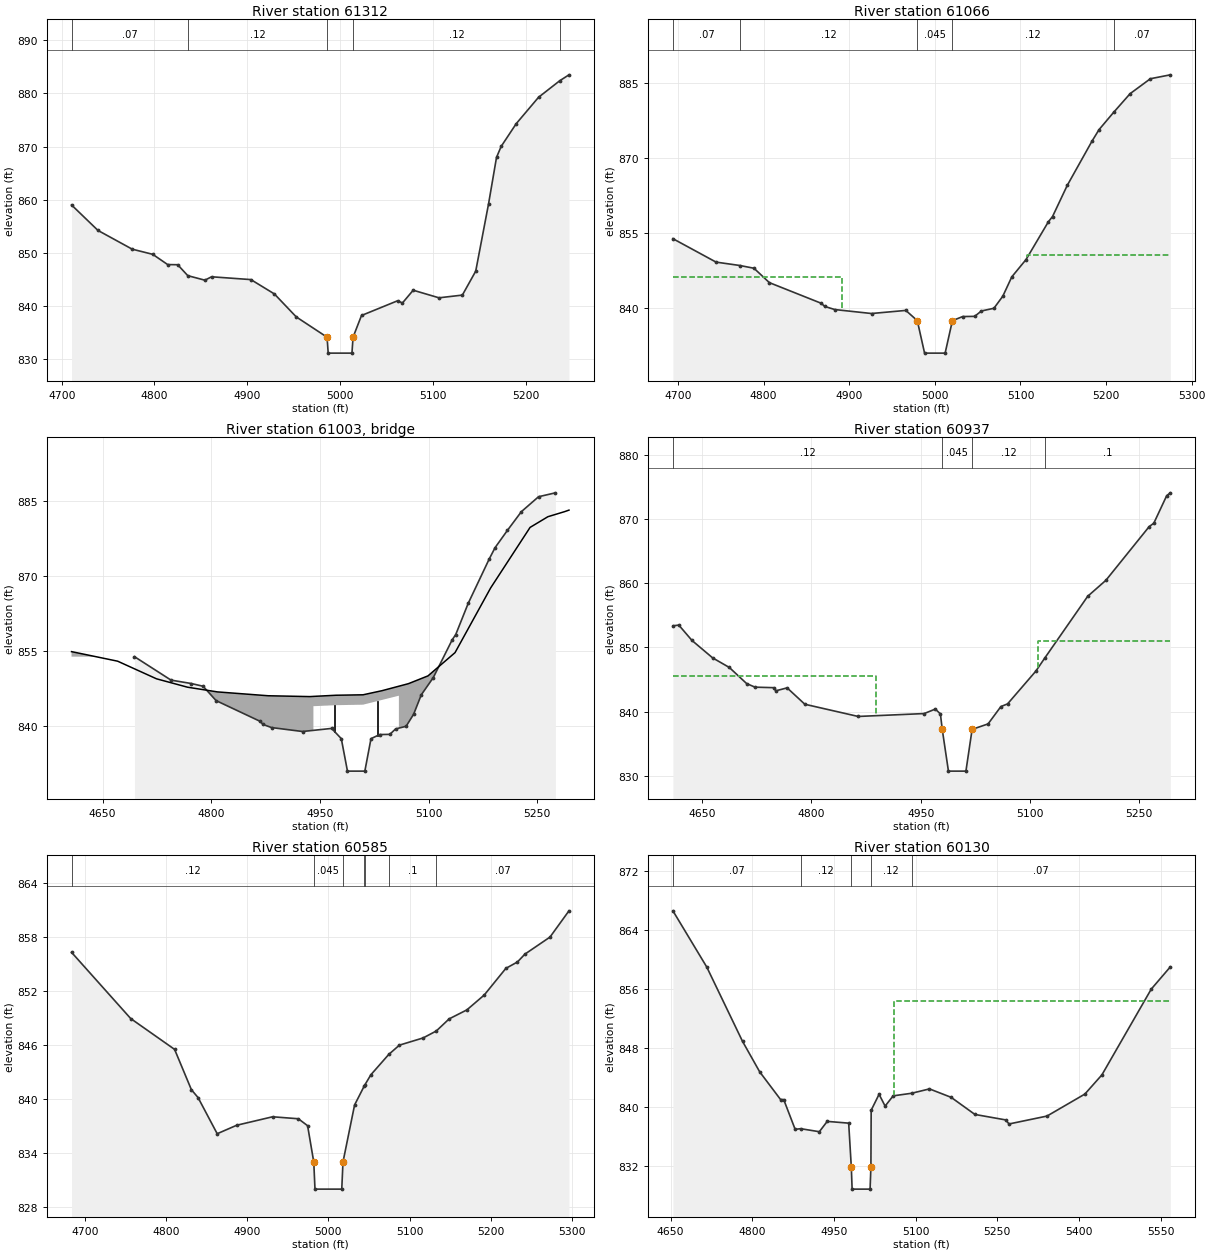
Type RM Length L Ch R = 1 ,61312   ,246,246,246
BEGIN DESCRIPTION:
North Deep Creek 165.0
END DESCRIPTION:
XS GIS Cut Line= 4
      1505989.67       886116.42       1505814.6       886066.02
      1505660.77       885983.81      1505485.73       885944.03
#Sta/Elev= 30
  4710.6     859  4739.1   854.2    4776  850.67  4798.1   849.7  4814.2  847.77
    4825  847.74  4835.9  845.68  4854.3  844.83  4861.5  845.47  4903.9  844.94
  4929.2  842.24  4952.8  837.91    4986  834.09  4987.2  831.09  5012.8  831.09
    5014  834.09  5023.1  838.18  5062.1  840.96  5067.2  840.53  5078.8  842.94
  5106.6  841.51  5131.8  842.02  5146.2  846.53    5160  859.18  5168.6  867.95
  5173.6  870.02  5189.8   874.3  5213.9  879.28  5236.7  882.39  5246.7  883.51
#Mann= 5 ,-1 , 0
  4710.6     .07       0  4835.9     .12       0    4986    .045       0
    5014     .12       0  5236.7     .07       0
Bank Sta=4986,5014
Exp/Cntr=0.5,0.3

Type RM Length L Ch R = 1 ,61066   ,129,129,129
BEGIN DESCRIPTION:
Shore Rd (NDC) us
END DESCRIPTION:
XS GIS Cut Line= 4
      1506049.31       885936.07      1505882.23       885847.22
      1505736.36       885750.42      1505521.54       885721.24
#Sta/Elev= 30
    4694  853.91  4744.4  849.22  4772.3  848.54  4788.7  847.99  4806.7  845.11
  4867.4  840.97  4871.4  840.34  4883.2  839.72    4926  838.93  4966.1  839.55
  4979.5   837.5    4988     831    5012     831  5020.5   837.5  5032.5  838.32
  5046.5  838.36  5054.4  839.44    5069  839.98  5079.4   842.4  5089.9  846.27
  5106.5  849.73  5132.6  857.29  5137.5  858.35  5154.7  864.59  5183.6  873.44
  5191.8  875.74  5208.7  879.17  5228.1  882.94  5251.8  885.93  5275.1  886.71
#Mann= 5 ,-1 , 0
    4694     .07       0  4772.3     .12       0  4979.5    .045       0
  5020.5     .12       0  5208.7     .07       0
#XS Ineff= 2 , 0
       0    4892   846.3    5108       0  850.74
Permanent Ineff=
       F       F
Bank Sta=4979.5,5020.5
Exp/Cntr=0.5,0.3

Type RM Length L Ch R = 3 ,61003   ,,,
BEGIN DESCRIPTION:
Shore Rd (NDC) tor
Structure ID: LDS_NDC_13
Approximate Survey Structure
END DESCRIPTION:
Bridge Culvert--1,0,-1,-1, 0
Deck Dist Width WeirC Skew NumUp NumDn MinLoCord MaxHiCord MaxSubmerge Is_Ogee
49,28,3,0, 22, 22, , , 0.95, 0, 1,1,,
  4607.1  4670.7  4724.4  4767.2  4808.5  4878.5  4936.1    4941    4941  4972.1
  5009.5  5035.6    5059    5059  5072.2  5099.2  5136.5  5185.7  5240.1  5264.7
  5287.9  5293.8
  854.92  853.01  849.48   847.8  846.86  846.09  845.92  845.96  845.96  846.19
  846.28   847.1     848     848  848.51  850.07  854.72  867.68  879.79  881.93
  882.95  883.25
     811     811     811     811     811     811     811     811     844   844.2
   844.3  845.25   846.1     811     811     811     811     811     811     811
     811     811
  4607.1  4670.7  4724.4  4767.2  4808.5  4878.5  4936.1    4941    4941  4972.1
  5009.5  5035.6    5059    5059  5072.2  5099.2  5136.5  5185.7  5240.1  5264.7
  5287.9  5293.8
  854.92  853.01  849.48   847.8  846.86  846.09  845.92  845.96  845.96  846.19
  846.28   847.1     848     848  848.51  850.07  854.72  867.68  879.79  881.93
  882.95  883.25
     811     811     811     811     811     811     811     811     844   844.2
   844.3  845.25   846.1     811     811     811     811     811     811     811
     811     811
Pier Skew, UpSta & Num, DnSta & Num=  ,4970.5, 2 ,4970.5, 2 , 0 , 0 , 0 ,0,0
       1       1
     830   845.4
       1       1
     830   845.4
Pier Skew, UpSta & Num, DnSta & Num=  ,5029.5, 2 ,5029.5, 2 , 0 , 0 , 0 ,0,0
       1       1
     830   845.4
       1       1
     830   845.4
Abutment Skew #Up #Dn= , 2 , 2
    4941  4959.3
     844  839.19
    4941  4959.3
     844  839.93
Abutment Skew #Up #Dn= , 2 , 2
  5040.8    5059
  838.34   846.1
  5040.8    5059
  838.04   846.1
BR Coef= 1 , 1 , 0 ,1.25, 0 ,,,0.8,-1,2,0,
WSPro=,,,, 1 ,,,, 0 ,,,, 0 ,,,,-1 ,-1 ,-1 , 0 , 0 , 0 , 0 , 0
BC Design=,, 0 ,, 0 ,,,,,,
BC HTab HWMax=886.76

Type RM Length L Ch R = 1 ,60937   ,352,352,352
BEGIN DESCRIPTION:
Shore Rd (NDC) ds
END DESCRIPTION:
XS GIS Cut Line= 4
      1506165.99       885868.42      1505989.64        885729.2
      1505780.12       885644.33      1505548.06       885644.33
#Sta/Elev= 30
  4609.8  853.37  4617.9  853.48    4636  851.09  4664.3  848.38  4687.2  846.89
    4711  844.38  4722.5  843.82    4748  843.74    4751  843.25  4766.6  843.71
  4790.9  841.16  4864.1  839.26  4954.7  839.71    4970  840.41    4977  839.65
  4979.5  837.25    4988  830.75    5012  830.75  5020.5  837.25  5042.4   838.1
    5060   840.8  5069.2  841.22    5108  846.32  5120.4  848.38  5179.2  857.97
  5204.1  860.45  5263.6  868.82  5269.9  869.34  5287.6  873.63  5292.6  874.07
#Mann= 4 ,-1 , 0
  4609.8     .12       0  4979.5    .045       0  5020.5     .12       0
  5120.4      .1       0
#XS Ineff= 2 , 0
       0    4889  845.62    5111       0     851
Permanent Ineff=
       F       F
Bank Sta=4979.5,5020.5
Exp/Cntr=0.5,0.3

Type RM Length L Ch R = 1 ,60585   ,455,455,455
BEGIN DESCRIPTION:
North Deep Creek 164.0
END DESCRIPTION:
XS GIS Cut Line= 4
      1506271.86       885457.28      1506135.12       885415.66
      1505891.36       885323.51      1505683.24       885299.72
#Sta/Elev= 30
  4683.5  856.26  4756.4  848.92  4810.5   845.5  4831.2  841.03  4839.4  840.16
    4863  836.15    4887  837.09  4931.3  838.03    4963  837.81  4974.4  837.04
    4982  833.01  4983.5  830.01  5016.5  830.01    5018  833.01  5032.3  839.34
  5044.2  841.44  5044.6  841.51  5052.4  842.69  5074.4  844.94  5087.5  845.97
  5116.8  846.77    5133  847.54  5148.8  848.88  5170.7  849.88  5192.1  851.53
  5218.7  854.48    5233  855.19  5242.2  856.06  5273.1  857.95  5296.5  860.86
#Mann= 7 ,-1 , 0
  4683.5     .12       0    4982    .045       0    5018     .12       0
  5044.2      .1       0  5044.6     .12       0  5074.4      .1       0
    5133     .07       0
Bank Sta=4982,5018
Exp/Cntr=0.3,0.1

Type RM Length L Ch R = 1 ,60130   ,520,520,520
BEGIN DESCRIPTION:
North Deep Creek 163.0
END DESCRIPTION:
XS GIS Cut Line= 4
      1506500.73         885050.      1506114.31       884931.11
      1505742.72       884919.22      1505614.92       884969.74
#Sta/Elev= 30
  4654.4  866.56  4716.6  858.94  4782.2  848.88  4813.8  844.74  4852.1  840.99
  4857.9  840.98  4878.9  836.95    4889  837.04  4923.3  836.63  4937.8  838.03
  4977.2  837.79    4982  831.85  4983.5  828.85  5016.5  828.85    5018  831.85
  5018.5  839.54    5033   841.7  5044.1   840.1  5058.9  841.49  5092.8  841.84
  5125.6  842.43  5165.3  841.29    5209  838.97  5265.4  838.23  5271.7  837.68
  5341.4  838.75  5410.9  841.73  5442.2  844.33  5532.8  855.95  5567.9  858.97
#Mann= 5 ,-1 , 0
  4654.4     .07       0    4889     .12       0    4982    .045       0
    5018     .12       0  5092.8     .07       0
#XS Ineff= 2 , 0
       0                  5060.8       0  854.36
Permanent Ineff=
       F       F
Bank Sta=4982,5018
Exp/Cntr=0.3,0.1

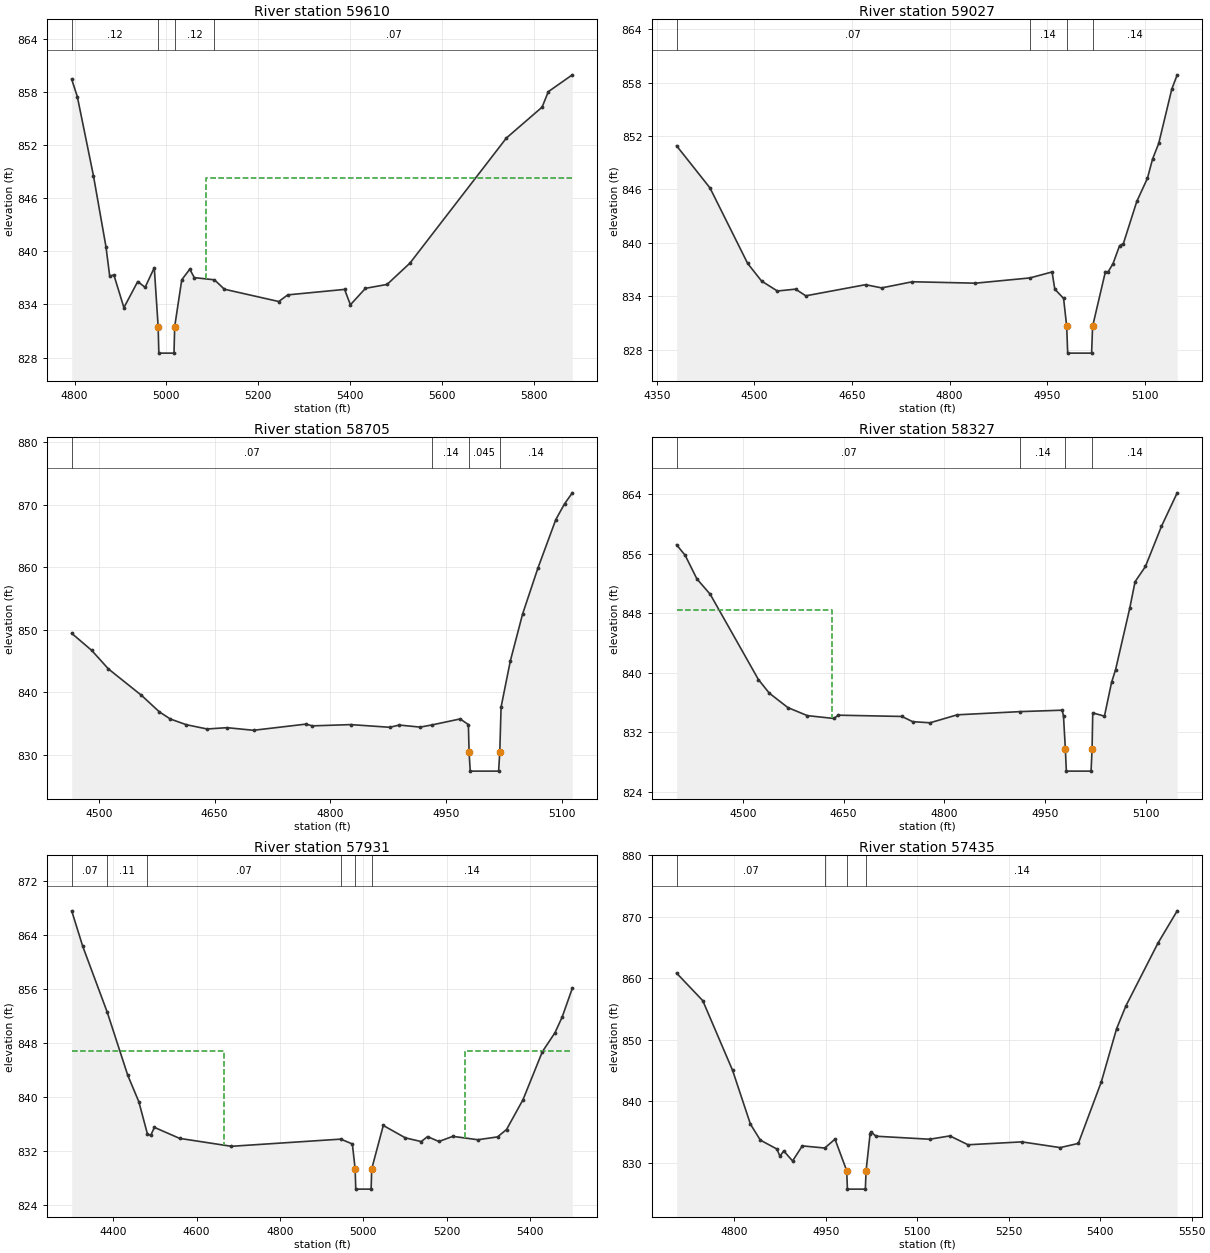
Type RM Length L Ch R = 1 ,59610   ,583,583,583
BEGIN DESCRIPTION:
North Deep Creek 162.0
END DESCRIPTION:
XS GIS Cut Line= 4
      1506405.68       884387.09      1506298.62       884404.94
      1505784.34       884604.11      1505564.36       884972.72
#Sta/Elev= 30
  4793.9  859.44  4806.2  857.46  4841.3  848.52  4868.4  840.54  4876.6   837.2
  4885.7  837.33  4907.5  833.64  4937.6  836.59  4953.6  835.93  4973.6  838.15
    4982   831.5  4983.5   828.5  5016.5   828.5    5018   831.5  5033.4  836.79
  5050.8  837.98  5060.7  837.03  5104.6  836.78  5126.1  835.72  5244.5  834.33
    5264  835.08  5387.7   835.7  5400.3  833.96  5433.1  835.82  5480.1  836.26
  5529.9  838.67  5739.9  852.81  5817.4  856.29    5831  858.04  5883.2  859.94
#Mann= 4 ,-1 , 0
  4793.9     .12       0    4982    .045       0    5018     .12       0
  5104.6     .07       0
#XS Ineff= 2 , 0
       0                  5086.8       0  848.34
Permanent Ineff=
       F       F
Bank Sta=4982,5018
Exp/Cntr=0.3,0.1

Type RM Length L Ch R = 1 ,59027   ,322,322,322
BEGIN DESCRIPTION:
North Deep Creek 161.0
END DESCRIPTION:
XS GIS Cut Line= 5
      1506435.33       884164.14      1506328.35       884143.34
       1505876.5       884015.51      1505802.18       884015.51
      1505686.21       884000.64
#Sta/Elev= 30
  4380.2   850.9  4431.6  846.16  4489.5  837.68  4510.9   835.7  4535.2  834.58
  4563.2  834.79  4578.9  834.04  4670.8  835.29  4695.6  834.93  4742.8  835.62
  4839.8  835.46  4923.6  836.05  4957.6  836.72  4961.8  834.79  4975.3  833.75
  4980.1   830.6  4981.6   827.6  5018.4   827.6  5019.9   830.6  5039.6  836.75
  5043.8  836.74  5051.3  837.65  5061.4  839.68  5067.2   839.9  5087.9  844.65
  5104.2  847.24  5112.1   849.4  5121.6  851.17  5141.7  857.27    5150  858.87
#Mann= 4 ,-1 , 0
  4380.2     .07       0  4923.6     .14       0  4980.1    .045       0
  5019.9     .14       0
Bank Sta=4980.1,5019.9
Exp/Cntr=0.3,0.1

Type RM Length L Ch R = 1 ,58705   ,378,378,378
BEGIN DESCRIPTION:
North Deep Creek 160.0
END DESCRIPTION:
XS GIS Cut Line= 5
      1506441.29       884092.78      1506337.27       884006.59
      1506072.69       883872.82       1505962.7       883736.07
      1505935.95       883703.38
#Sta/Elev= 30
  4464.7  849.41  4490.8  846.66  4512.3  843.71  4555.2  839.48  4578.4  836.83
  4592.6  835.69  4613.2  834.78  4640.3  834.09  4666.2   834.3  4700.5  833.88
  4768.5  834.87    4777  834.59  4826.7  834.79  4877.4  834.36  4889.4  834.72
  4916.7  834.39  4931.6  834.73  4968.6   835.7  4979.2  834.79  4980.1  830.34
  4981.6  827.34  5018.4  827.34  5019.9  830.34  5021.6   837.6  5033.6  844.99
  5049.5   852.5  5069.3  859.83  5092.6  867.63  5103.9  870.15    5114  871.91
#Mann= 4 ,-1 , 0
  4464.7     .07       0  4931.6     .14       0  4980.1    .045       0
  5019.9     .14       0
Bank Sta=4980.1,5019.9
Exp/Cntr=0.3,0.1

Type RM Length L Ch R = 1 ,58327   ,396,396,396
BEGIN DESCRIPTION:
North Deep Creek 159.0
END DESCRIPTION:
XS GIS Cut Line= 4
      1506569.15       884057.16      1506286.73       883560.68
      1506227.28       883516.09      1506132.11       883486.36
#Sta/Elev= 30
  4401.4   857.2  4414.2  855.78  4431.7  852.61  4451.5  850.55  4523.2  839.11
  4539.4  837.28  4567.1  835.34  4596.1  834.26  4635.4  833.88  4642.3  834.32
  4736.8  834.15  4752.8  833.45  4778.7   833.3  4819.2  834.37    4913   834.8
  4975.5  834.99  4977.4  834.15  4980.1  829.81  4981.6  826.81  5018.4  826.81
  5019.9  829.81  5020.9  834.63  5038.3  834.19  5048.9  838.72  5054.9  840.44
  5075.9  848.65  5083.9  852.24  5099.3  854.28  5123.2  859.68  5146.6  864.17
#Mann= 4 ,-1 , 0
  4401.4     .07       0    4913     .14       0  4980.1    .045       0
  5019.9     .14       0
#XS Ineff= 2 , 0
       0  4633.2  848.43               0
Permanent Ineff=
       F       F
Bank Sta=4980.1,5019.9
Exp/Cntr=0.3,0.1

Type RM Length L Ch R = 1 ,57931   ,496,496,496
BEGIN DESCRIPTION:
North Deep Creek 158.0
END DESCRIPTION:
XS GIS Cut Line= 5
       1507107.2       883917.41      1506884.25       883771.75
      1506586.97       883370.43      1506490.76       883022.21
      1506490.76       882948.53
#Sta/Elev= 30
  4300.3  867.52  4326.7  862.29  4385.7  852.51  4434.8  843.21  4461.4  839.29
  4481.8  834.57  4489.7  834.32  4498.6  835.52  4559.1  833.89  4683.3  832.72
  4945.5  833.78  4973.4  833.07  4980.1  829.39  4981.6  826.39  5018.4  826.39
  5019.9  829.39  5047.6   835.8  5100.8  833.96  5138.6  833.42  5153.7  834.15
    5181  833.43  5214.4  834.19  5274.4  833.69  5321.7  834.11  5343.2   835.2
  5382.7  839.61  5429.2  846.71  5459.4   849.5  5476.7  851.84    5501  856.08
#Mann= 6 ,-1 , 0
  4300.3     .07       0  4385.7     .11       0  4481.8     .07       0
  4945.5     .14       0  4980.1    .045       0  5019.9     .14       0
#XS Ineff= 2 , 0
       0  4665.7  846.74    5243       0  846.74
Permanent Ineff=
       F       F
Bank Sta=4980.1,5019.9
Exp/Cntr=0.3,0.1

Type RM Length L Ch R = 1 ,57435   ,233,233,233
BEGIN DESCRIPTION:
North Deep Creek 157.0
END DESCRIPTION:
XS GIS Cut Line= 5
      1507264.71       883435.81      1507125.04       883367.46
      1506994.24       883263.41      1506762.36       883019.65
        1506691.       882873.95
#Sta/Elev= 30
    4705  860.84    4748  856.36  4796.9  845.03  4826.2  836.29  4842.4   833.7
  4869.5  832.25  4874.6  831.08  4880.8  831.94  4895.3  830.31  4911.3  832.76
  4948.1  832.41  4964.9  833.85  4984.1  828.73  4985.3  825.73  5014.7  825.73
  5015.9  828.73  5022.5  834.73  5023.7  835.05  5032.2  834.33  5120.2  833.84
  5153.4  834.38  5183.2  832.94  5271.4  833.41  5334.4  832.48  5364.1  833.16
  5401.9  843.19  5426.9  851.81    5442  855.48  5494.5  865.67  5526.3  870.96
#Mann= 4 ,-1 , 0
    4705     .07       0  4948.1     .14       0  4984.1    .045       0
  5015.9     .14       0
Bank Sta=4984.1,5015.9
Exp/Cntr=0.3,0.1