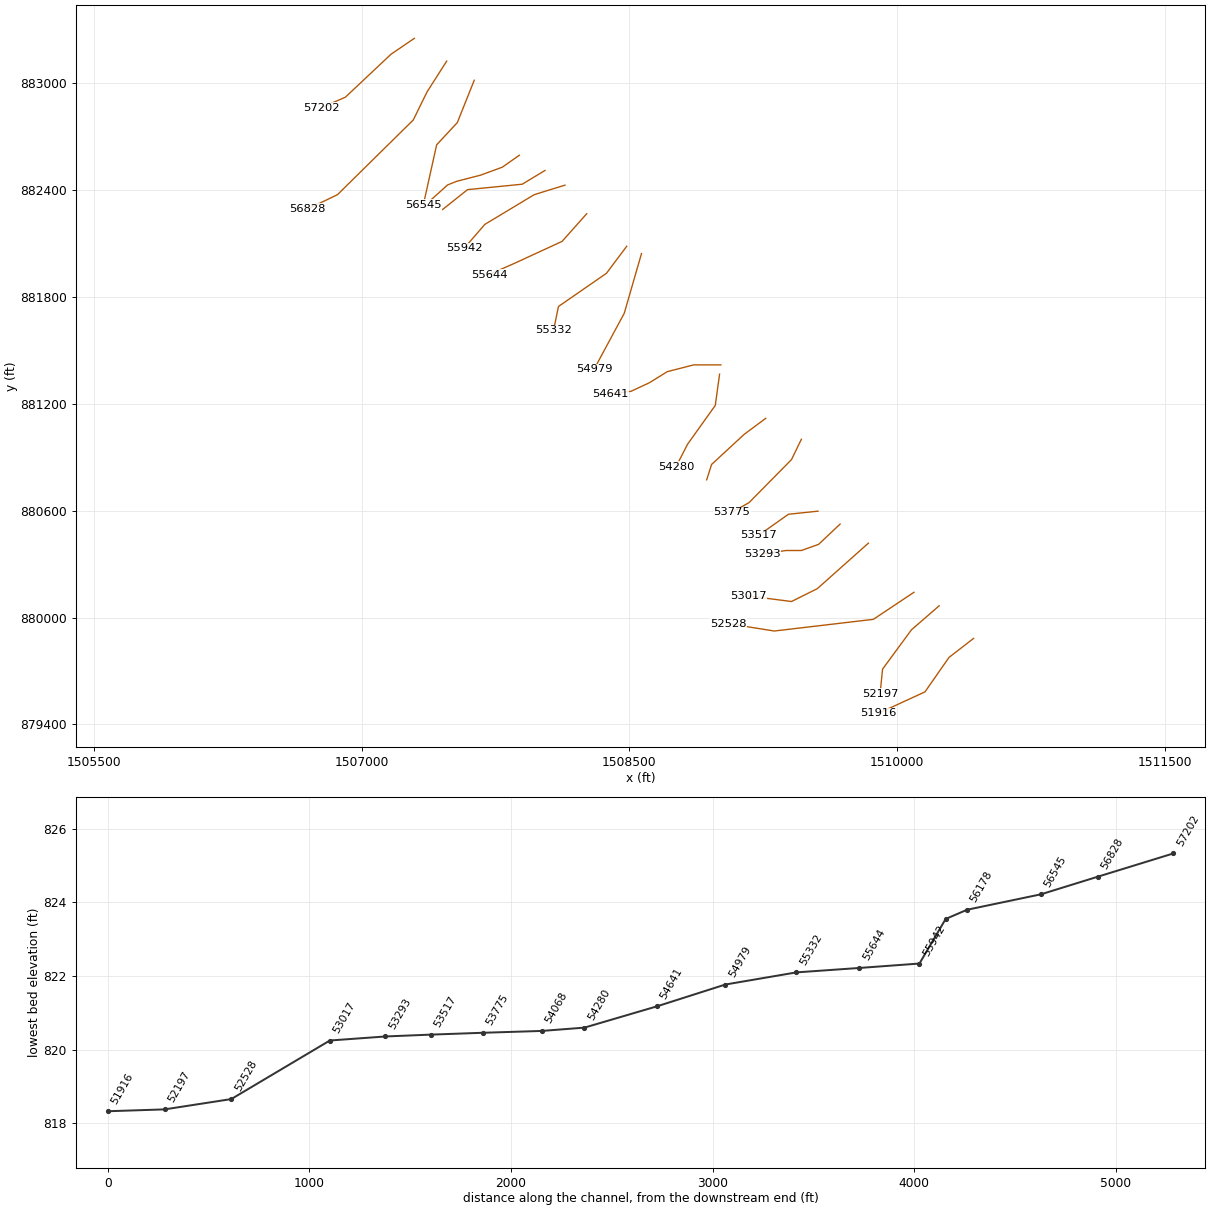
HEC-RAS study North Deep Creek.prj: North Deep Creek Limited Detail Study

--- North Deep Creek.g01 (geometry) --- (continued)

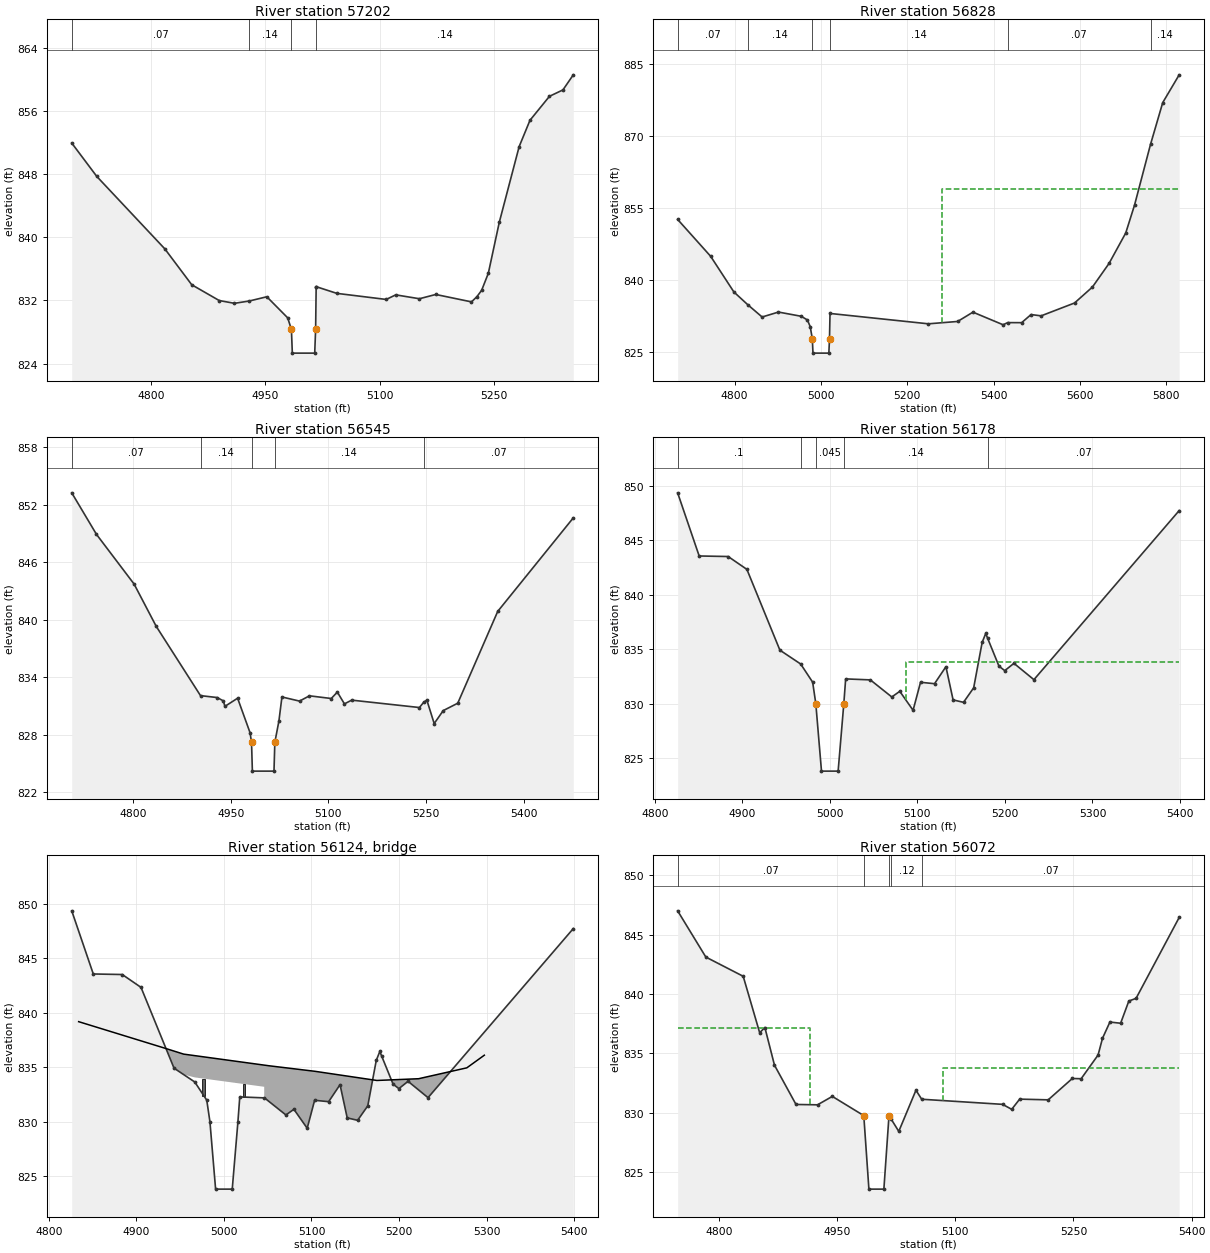
Type RM Length L Ch R = 1 ,57202   ,374,374,374
BEGIN DESCRIPTION:
North Deep Creek 156.0
END DESCRIPTION:
XS GIS Cut Line= 4
      1507294.51       883248.57      1507163.68       883159.37
      1506908.03       882918.58      1506771.24       882859.11
#Sta/Elev= 30
  4695.6  851.94  4728.5  847.71  4817.9  838.53  4853.2  833.99  4889.3  831.99
  4909.3  831.64  4928.7  831.93  4951.8  832.47  4979.2   829.8  4984.1  828.33
  4985.3  825.33  5014.7  825.33  5015.9  828.33  5016.6  833.68  5016.9  833.74
  5043.7   832.9  5108.6  832.13  5121.1  832.71  5152.2  832.22  5173.7  832.76
  5220.6  831.82  5227.7  832.48  5233.9  833.28  5242.7  835.44  5257.1   841.9
  5283.2  851.49  5297.4  854.82    5323  857.86  5340.7  858.67  5354.3  860.58
#Mann= 4 ,-1 , 0
  4695.6     .07       0  4928.7     .14       0  4984.1    .045       0
  5015.9     .14       0
Bank Sta=4984.1,5015.9
Exp/Cntr=0.3,0.1

Type RM Length L Ch R = 1 ,56828   ,283,283,283
BEGIN DESCRIPTION:
North Deep Creek 155.0
END DESCRIPTION:
XS GIS Cut Line= 5
      1507475.83       883120.74      1507365.83        882948.3
      1507288.54       882790.75      1506863.44        882371.6
      1506696.99       882291.35
#Sta/Elev= 30
  4668.1  852.57  4744.6  844.88  4798.4  837.45  4830.7  834.78  4863.8  832.23
  4901.7  833.26  4954.4  832.38  4968.7  831.61  4975.2  830.23  4980.1   827.7
  4981.6   824.7  5018.4   824.7  5019.9   827.7  5021.1  832.97    5249  830.81
  5316.7   831.3  5352.2  833.24  5422.1  830.61  5432.6  831.06    5465  831.05
  5486.8  832.74  5510.1  832.47  5587.5  835.15  5628.9  838.47  5667.4  843.39
  5706.1  849.74  5726.5  855.56  5763.5  868.21  5791.8  876.92  5829.9  882.71
#Mann= 6 ,-1 , 0
  4668.1     .07       0  4830.7     .14       0  4980.1    .045       0
  5019.9     .14       0  5432.6     .07       0  5763.5     .14       0
#XS Ineff= 2 , 0
       0                  5280.4       0  858.87
Permanent Ineff=
       F       F
Bank Sta=4980.1,5019.9
Exp/Cntr=0.3,0.1

Type RM Length L Ch R = 1 ,56545   ,367,367,367
BEGIN DESCRIPTION:
North Deep Creek 154.0
END DESCRIPTION:
XS GIS Cut Line= 4
      1507630.38       883013.66      1507535.27       882775.89
      1507419.34       882651.03      1507345.02       882315.13
#Sta/Elev= 30
  4705.9  853.23  4743.9   848.9  4801.7  843.72  4835.7  839.31  4903.7  832.09
  4929.4  831.89  4938.8  831.54  4941.2  830.97  4960.7  831.82  4979.8  828.23
  4982.1  827.22  4983.4  824.22  5016.6  824.22  5017.9  827.22  5024.2  829.46
  5028.8  831.95  5055.8  831.52  5071.1  832.07  5104.6  831.79  5113.9  832.46
  5124.8  831.23    5136  831.62    5240  830.85  5246.4  831.38  5251.4  831.63
  5262.7  829.18  5276.6  830.53  5298.9   831.3  5360.3  840.87  5476.4  850.62
#Mann= 5 ,-1 , 0
  4705.9     .07       0  4903.7     .14       0  4982.1    .045       0
  5017.9     .14       0  5246.4     .07       0
Bank Sta=4982.1,5017.9
Exp/Cntr=0.5,0.3

Type RM Length L Ch R = 1 ,56178   ,106,106,106
BEGIN DESCRIPTION:
Steelman Rd (NDC) us
END DESCRIPTION:
XS GIS Cut Line= 6
      1507882.85       882592.72       1507787.5       882525.77
      1507665.72       882481.12      1507531.77       882446.61
      1507481.03       882426.32      1507381.62       882337.05
#Sta/Elev= 30
  4826.2  849.36  4850.8  843.56  4883.9  843.51  4905.3  842.33    4943  834.91
  4966.7  833.64  4980.4  831.97    4984     830  4990.5   823.8  5009.5   823.8
    5016     830  5018.1  832.27  5046.3  832.18  5070.8  830.61  5079.9  831.13
  5095.1  829.39  5103.6  831.96  5119.6  831.83  5132.6  833.39  5140.8  830.34
  5152.7  830.12  5164.3  831.45    5174  835.63  5178.1  836.45  5180.1  836.03
  5193.2  833.44  5199.8  833.03  5210.3   833.7  5233.1   832.2    5399  847.73
#Mann= 5 ,-1 , 0
  4826.2      .1       0  4966.7     .14       0    4984    .045       0
    5016     .14       0  5180.1     .07       0
#XS Ineff= 2 , 0
       0  4913.5  837.19  5086.5       0  833.78
Permanent Ineff=
       F       F
Bank Sta=4984,5016
Exp/Cntr=0.5,0.3

Type RM Length L Ch R = 3 ,56124   ,,,
BEGIN DESCRIPTION:
Steelman Rd (NDC) tor
Structure ID: LDS_NDC_11
Approximate Survey Structure
END DESCRIPTION:
Bridge Culvert--1,0,-1,-1, 0
Deck Dist Width WeirC Skew NumUp NumDn MinLoCord MaxHiCord MaxSubmerge Is_Ogee
40.5,27,3,0, 12, 12, , , 0.95, 0, 1,1,,
  4834.1  4933.5    4954    4954    5046    5046  5051.5  5104.1  5174.7  5222.3
  5277.4  5297.4
  839.18  836.72   836.2   836.2  835.19  835.19  835.13  834.62  833.78  833.94
  834.94   836.1
   803.8   803.8   803.8   834.2   833.2   803.8   803.8   803.8   803.8   803.8
   803.8   803.8
  4834.1  4933.5    4954    4954    5046    5046  5051.5  5104.1  5174.7  5222.3
  5277.4  5297.4
  839.18  836.72   836.2   836.2  835.19  835.19  835.13  834.62  833.78  833.94
  834.94   836.1
   803.8   803.8   803.8   834.2   833.2   803.8   803.8   803.8   803.8   803.8
   803.8   803.8
Pier Skew, UpSta & Num, DnSta & Num=  ,4977, 2 ,4977, 2 , 0 , 0 , 0 ,0,0
       3       3
     800   834.2
       3       3
     825   834.2
Pier Skew, UpSta & Num, DnSta & Num=  ,5023, 2 ,5023, 2 , 0 , 0 , 0 ,0,0
       3       3
     800   834.2
       3       3
     829   834.2
Abutment Skew #Up #Dn= , 2 , 2
    4954    4977
   834.2  832.43
    4954    4977
   834.2  830.01
Abutment Skew #Up #Dn= , 2 , 2
    5023    5046
  832.27   833.2
    5023    5046
     829   833.2
BR Coef= 1 , 1 , 0 ,1.25, 0 ,,,0.8,-1,2,0,
WSPro=,,,, 1 ,,,, 0 ,,,, 0 ,,,,-1 ,-1 ,-1 , 0 , 0 , 0 , 0 , 0
BC Design=,, 0 ,, 0 ,,,,,,
BC HTab HWMax=849.36

Type RM Length L Ch R = 1 ,56072   ,130,130,130
BEGIN DESCRIPTION:
Steelman Rd (NDC) ds
END DESCRIPTION:
XS GIS Cut Line= 4
      1508026.96       882507.49      1507899.12       882430.38
      1507592.66       882399.93      1507452.58       882288.28
#Sta/Elev= 30
  4747.8  847.02  4783.6  843.12    4831   841.5  4851.9  836.74  4858.5  837.18
  4870.7     834    4898  830.69  4925.3  830.66  4944.1  831.37    4984  829.75
  4990.5  823.55  5009.5  823.55    5016  829.75  5018.6  829.47  5028.4  828.42
  5050.2  831.89  5057.5  831.13  5160.1   830.7  5171.7  830.28  5181.8  831.14
    5218  831.08  5248.6  832.88  5259.8  832.86  5281.3  834.86  5286.9  836.27
  5296.3  837.64  5309.9  837.54  5320.3  839.41  5329.5  839.64  5384.2  846.46
#Mann= 5 ,-1 , 0
  4747.8     .07       0    4984    .045       0    5016     .07       0
  5018.6     .12       0  5057.5     .07       0
#XS Ineff= 2 , 0
       0  4915.5  837.12  5084.5       0  833.77
Permanent Ineff=
       F       F
Bank Sta=4984,5016
Exp/Cntr=0.5,0.3

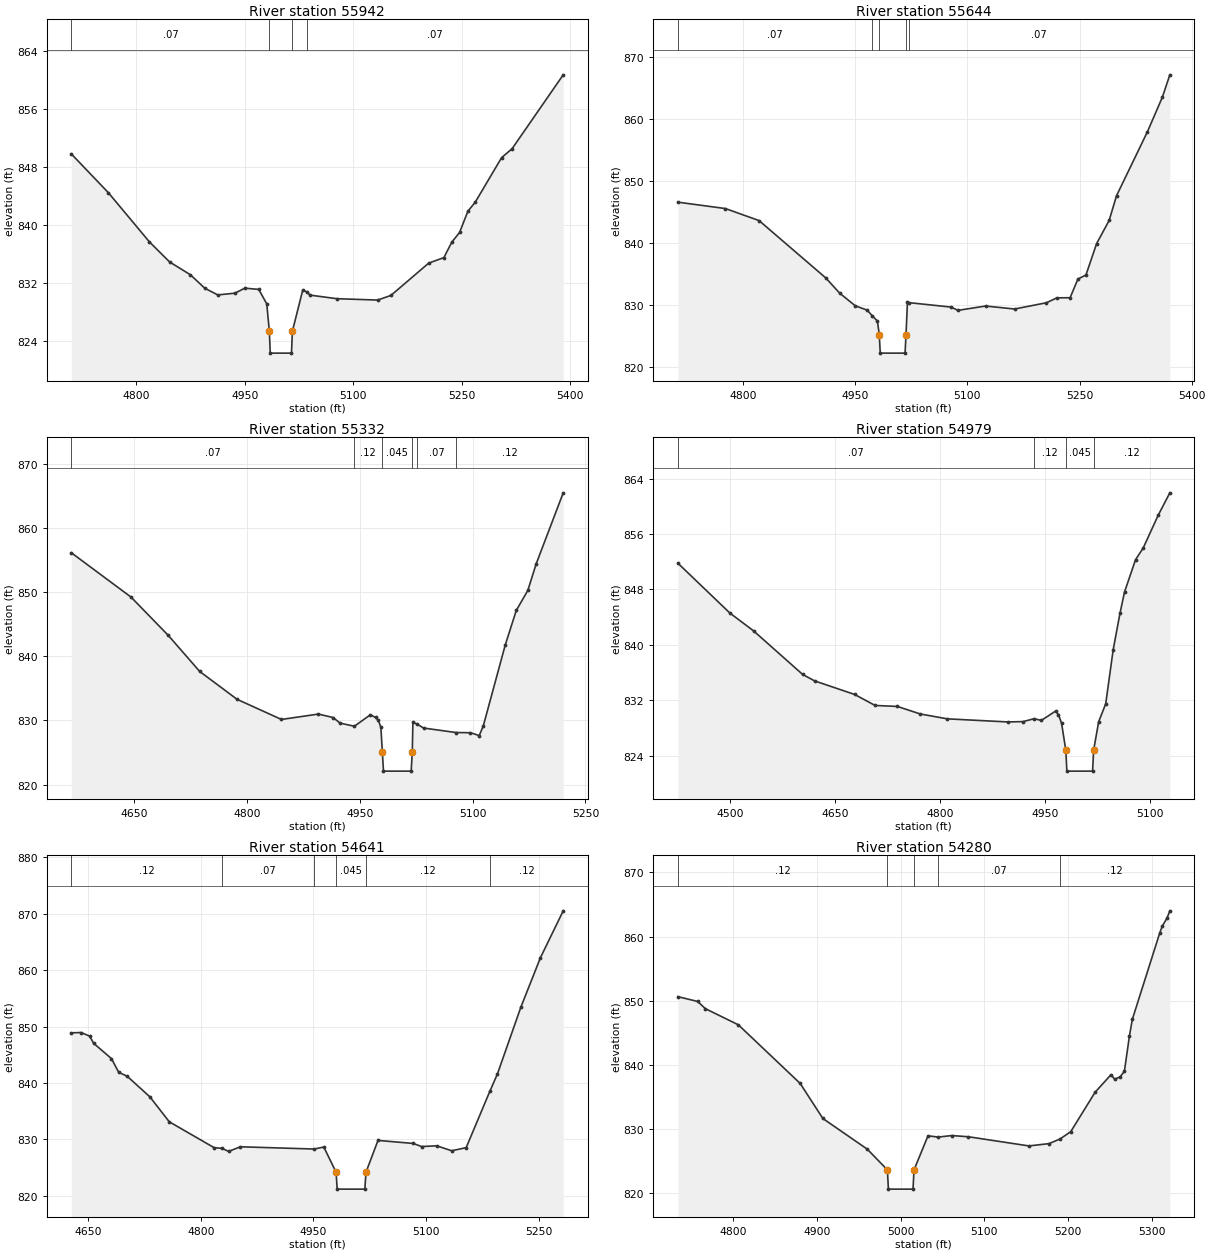
Type RM Length L Ch R = 1 ,55942   ,298,298,298
BEGIN DESCRIPTION:
North Deep Creek 153.0
END DESCRIPTION:
XS GIS Cut Line= 4
      1508138.71        882425.1      1507966.32        882371.6
      1507689.85       882205.13      1507573.94       882071.38
#Sta/Elev= 30
  4710.2  849.79  4761.6  844.43  4818.3  837.66  4846.2   834.9    4875  833.13
  4894.7  831.29  4912.7  830.36  4936.6   830.6  4950.1  831.29  4969.4  831.12
  4980.5  829.13  4984.1  825.34  4985.3  822.34  5014.7  822.34  5015.9  825.34
  5030.3  831.04  5035.6  830.78  5040.4  830.33  5077.4  829.84  5133.8  829.65
  5152.2  830.29  5204.4  834.74  5225.4   835.5  5236.4  837.64  5247.1  838.96
  5258.6  841.89  5268.8  843.14  5305.2  849.27  5319.7   850.5  5390.4  860.68
#Mann= 4 ,-1 , 0
  4710.2     .07       0  4984.1    .045       0  5015.9     .07       0
  5035.6     .07       0
Bank Sta=4984.1,5015.9
Exp/Cntr=0.3,0.1

Type RM Length L Ch R = 1 ,55644   ,312,312,312
BEGIN DESCRIPTION:
North Deep Creek 152.0
END DESCRIPTION:
XS GIS Cut Line= 4
      1508260.83       882264.99      1508122.95       882109.88
      1507854.05       881985.77      1507712.67        881923.7
#Sta/Elev= 30
  4712.7  846.58  4776.3  845.55  4821.3  843.61  4910.5  834.36  4929.2  831.89
  4949.9  829.87  4966.1  829.14  4972.8  828.23  4979.6  827.41  4982.1  825.22
  4983.4  822.22  5016.6  822.22  5017.9  825.22  5019.8  830.49  5021.4  830.37
  5078.3  829.65  5087.3  829.12  5124.3  829.82  5163.2  829.34  5205.8  830.35
  5219.7  831.14  5237.4  831.16  5247.8  834.17  5258.6  834.83  5272.8  839.88
  5289.6  843.63  5299.5  847.62  5340.9  857.96  5360.8  863.52  5370.8  867.13
#Mann= 5 ,-1 , 0
  4712.7     .07       0  4972.8     .12       0  4982.1    .045       0
  5017.9     .12       0  5021.4     .07       0
Bank Sta=4982.1,5017.9
Exp/Cntr=0.3,0.1

Type RM Length L Ch R = 1 ,55332   ,353,353,353
BEGIN DESCRIPTION:
North Deep Creek 151.0
END DESCRIPTION:
XS GIS Cut Line= 4
      1508484.92       882082.28      1508371.17       881930.61
      1508102.27       881744.45      1508074.69       881609.99
#Sta/Elev= 30
  4566.6  856.17    4646  849.25  4695.4  843.29  4737.3  837.65    4787   833.3
    4846  830.16  4895.1     831  4914.6  830.46  4923.9  829.59  4942.9   829.1
  4964.1  830.88  4971.1  830.48  4974.7  830.04  4978.1  828.96  4980.1   825.1
  4981.6   822.1  5018.4   822.1  5019.9   825.1  5020.7  829.73  5026.2  829.44
  5034.9  828.82  5078.1  828.12  5097.1  828.09  5108.9  827.65  5114.3  829.16
  5143.5   841.8  5158.1  847.16  5173.5   850.3  5184.6  854.44  5220.5  865.51
#Mann= 6 ,-1 , 0
  4566.6     .07       0  4942.9     .12       0  4980.1    .045       0
  5019.9     .12       0  5026.2     .07       0  5078.1     .12       0
Bank Sta=4980.1,5019.9
Exp/Cntr=0.3,0.1

Type RM Length L Ch R = 1 ,54979   ,338,338,338
BEGIN DESCRIPTION:
North Deep Creek 150.0
END DESCRIPTION:
XS GIS Cut Line= 3
      1508567.66        882040.9      1508471.14       881706.53
      1508302.23       881392.84
#Sta/Elev= 30
  4424.7  851.79  4499.3  844.58  4533.2  842.01  4603.3  835.73  4620.6  834.79
  4677.7  832.84  4707.1  831.25  4738.9  831.11  4771.8  830.02  4810.3  829.32
  4897.2  828.87  4918.9  828.92  4934.8  829.34    4945  829.09  4965.5  830.44
  4969.5  829.93    4974  828.69  4980.1  824.77  4981.6  821.77  5018.4  821.77
  5019.9  824.77  5027.1   828.9  5037.2  831.49  5047.9   839.3  5057.6  844.54
  5064.1  847.62  5079.9  852.29  5090.9  853.99  5112.4  858.73    5129  861.95
#Mann= 4 ,-1 , 0
  4424.7     .07       0  4934.8     .12       0  4980.1    .045       0
  5019.9     .12       0
Bank Sta=4980.1,5019.9
Exp/Cntr=0.3,0.1

Type RM Length L Ch R = 1 ,54641   ,361,361,361
BEGIN DESCRIPTION:
North Deep Creek 149.0
END DESCRIPTION:
XS GIS Cut Line= 6
      1509012.35       881416.95       1508860.7       881416.95
      1508712.46       881379.02      1508612.49       881316.97
      1508509.06       881268.71      1508391.84       881254.91
#Sta/Elev= 30
  4627.8  848.89    4641  848.95  4652.4   848.3  4657.4  847.06  4681.3  844.32
  4690.8  841.92  4702.4  841.17  4732.3  837.56  4758.2  833.12  4817.9  828.53
  4828.3  828.41  4837.2  827.87  4852.8  828.69  4950.9  828.29  4963.8  828.64
  4980.1  824.18  4981.6  821.18  5018.4  821.18  5019.9  824.18  5035.9  829.82
  5082.7  829.28  5093.9  828.73  5114.1  828.86    5134  827.98  5153.2  828.54
  5184.6   838.5  5194.8  841.61  5225.9  853.43    5252  862.22  5282.3  870.53
#Mann= 6 ,-1 , 0
  4627.8     .12       0  4828.3     .07       0  4950.9     .12       0
  4980.1    .045       0  5019.9     .12       0  5184.6     .12       0
Bank Sta=4980.1,5019.9
Exp/Cntr=0.3,0.1

Type RM Length L Ch R = 1 ,54280   ,212,212,212
BEGIN DESCRIPTION:
North Deep Creek 148.0
END DESCRIPTION:
XS GIS Cut Line= 4
      1509005.49       881365.21      1508981.36       881189.42
      1508826.23       880972.23      1508760.75       880844.71
#Sta/Elev= 30
  4733.8  850.63  4757.4  849.88  4766.7  848.75    4806  846.24  4879.9  837.09
    4907  831.62  4960.2  826.82  4984.1   823.6  4985.3   820.6  5014.7   820.6
  5015.9   823.6  5032.6  828.92  5044.8  828.72    5061  828.96  5080.9  828.77
  5153.2  827.34  5177.2   827.7  5190.6  828.44  5203.2  829.58  5232.2  835.71
  5251.2  838.45  5255.6  837.75    5262  838.11  5267.2  838.97  5273.2  844.47
  5276.7  847.09  5309.3   860.5  5312.4  861.62  5318.1  862.88  5321.5  864.02
#Mann= 5 ,-1 , 0
  4733.8     .12       0  4984.1    .045       0  5015.9     .12       0
  5044.8     .07       0  5190.6     .12       0
Bank Sta=4984.1,5015.9
Exp/Cntr=0.3,0.1

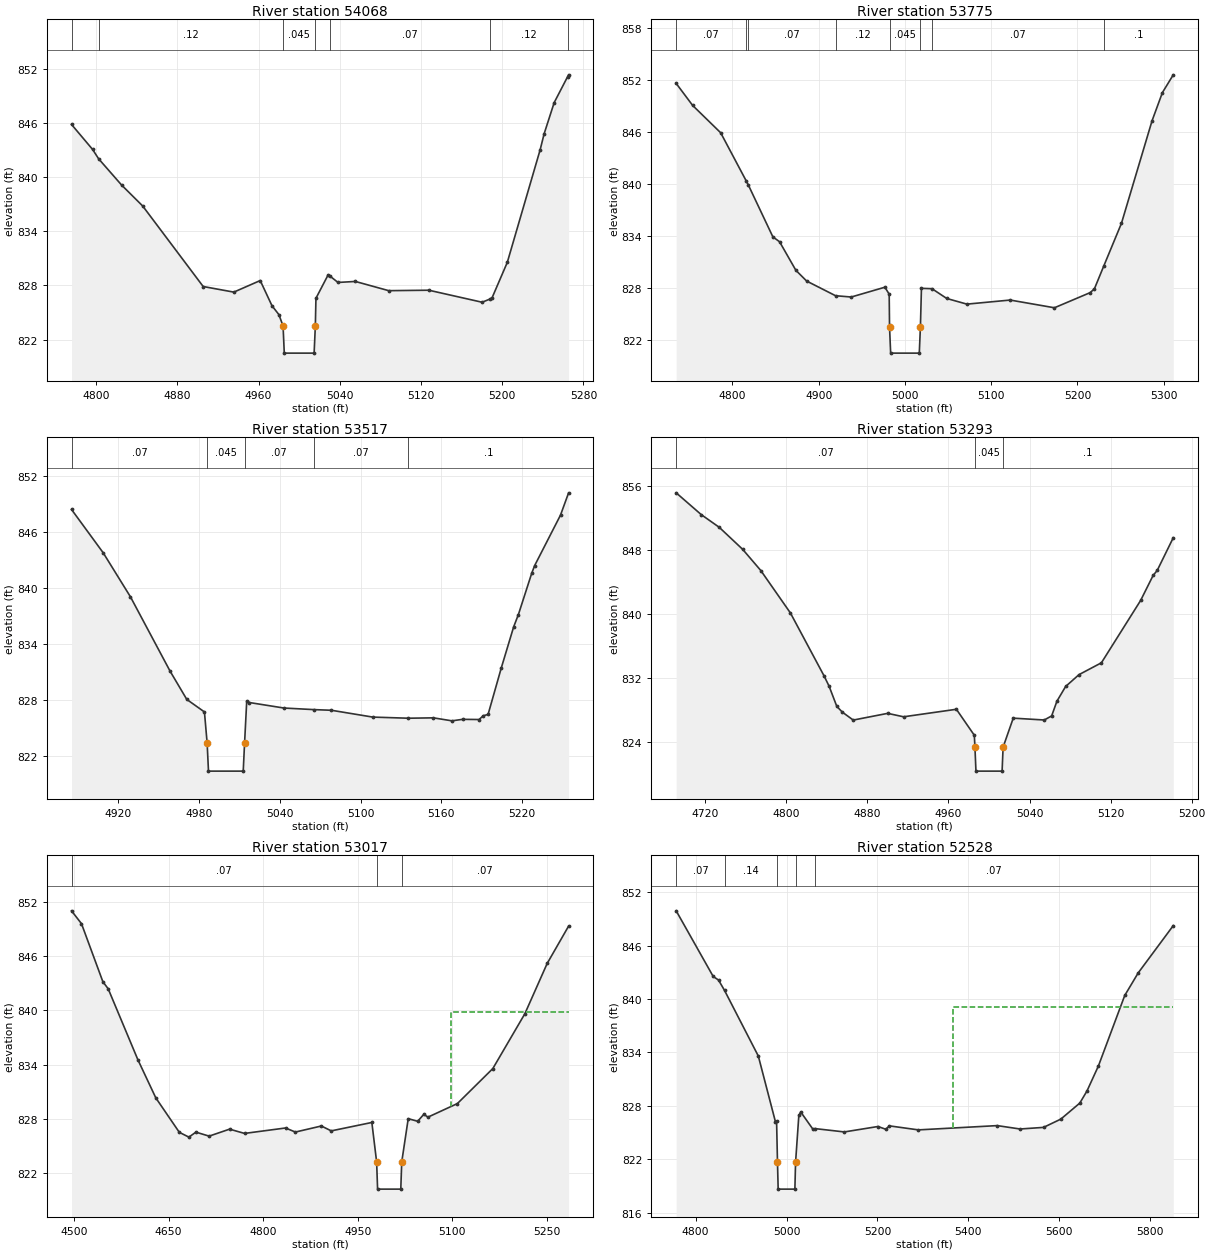
Type RM Length L Ch R = 1 ,54068   ,293,293,293
BEGIN DESCRIPTION:
North Deep Creek 147.0
END DESCRIPTION:
XS GIS Cut Line= 4
      1509264.07       881117.03      1509143.39       881027.39
      1508960.68       880858.46      1508933.09       880772.24
#Sta/Elev= 30
  4775.7  845.81  4796.5  843.04  4802.4  842.01    4825  839.11  4845.8  836.79
  4905.4  827.88  4935.6  827.26  4961.6  828.54  4973.2  825.75    4980  824.77
  4984.1  823.51  4985.3  820.51  5014.7  820.51  5015.9  823.51  5016.5  826.58
  5028.6  829.19  5030.8  828.99  5038.2  828.33  5055.3  828.44  5088.2  827.42
  5127.7  827.47  5180.2  826.14  5188.1   826.5    5190  826.63    5205  830.55
  5237.4  843.02  5241.3  844.78  5251.2  848.23  5264.5  851.11  5265.4   851.3
#Mann= 7 ,-1 , 0
  4775.7     .07       0  4802.4     .12       0  4984.1    .045       0
  5015.9     .12       0  5030.8     .07       0  5188.1     .12       0
  5264.5      .1       0
Bank Sta=4984.1,5015.9
Exp/Cntr=0.3,0.1

Type RM Length L Ch R = 1 ,53775   ,258,258,258
BEGIN DESCRIPTION:
North Deep Creek 146.0
END DESCRIPTION:
XS GIS Cut Line= 4
      1509463.99       880999.79      1509408.84       880886.04
      1509170.97       880644.72      1509074.48       880589.58
#Sta/Elev= 30
  4734.7  851.56  4753.8  849.02  4786.3  845.87  4815.8  840.34  4818.4  839.84
  4846.8  833.87  4854.6   833.3  4873.5  830.01    4886  828.77  4919.5  827.08
  4937.7  826.93  4976.7  828.06  4981.7  827.26  4982.1  823.46  4983.4  820.46
  5016.6  820.46  5017.9  823.46  5019.1  827.93  5031.3  827.89  5048.5  826.76
  5071.8  826.11    5122  826.58  5173.3  825.69  5214.6  827.43  5219.6  827.86
  5230.5   830.5    5251  835.42  5286.5  847.25  5298.5   850.5  5311.1  852.55
#Mann= 8 ,-1 , 0
  4734.7     .07       0  4815.8     .12       0  4818.4     .07       0
  4919.5     .12       0  4982.1    .045       0  5017.9     .12       0
  5031.3     .07       0  5230.5      .1       0
Bank Sta=4982.1,5017.9
Exp/Cntr=0.3,0.1

Type RM Length L Ch R = 1 ,53517   ,224,224,224
BEGIN DESCRIPTION:
North Deep Creek 145.0
END DESCRIPTION:
XS GIS Cut Line= 3
      1509557.03       880596.45      1509391.61       880579.22
      1509226.14       880462.01
#Sta/Elev= 30
  4885.4   848.4  4908.9  843.77  4929.1  839.07  4958.6   831.1    4971  828.08
  4984.1  826.74  4986.1  823.41  4987.1  820.41  5012.9  820.41  5013.9  823.41
  5015.5  827.92  5017.4  827.75  5043.1  827.16  5065.4  826.99  5078.4  826.92
  5109.1  826.19  5135.5  826.07  5154.1  826.11  5167.9  825.79  5175.8  825.95
    5188  825.93  5191.2  826.34  5194.7  826.47  5204.6  831.49  5213.7  835.84
  5217.2  837.15  5227.1  841.57  5229.3   842.4  5248.5   847.8  5254.5  850.18
#Mann= 5 ,-1 , 0
  4885.4     .07       0  4986.1    .045       0  5013.9     .07       0
  5065.4     .07       0  5135.5      .1       0
Bank Sta=4986.1,5013.9
Exp/Cntr=0.3,0.1

Type RM Length L Ch R = 1 ,53293   ,276,276,276
BEGIN DESCRIPTION:
North Deep Creek 144.0
END DESCRIPTION:
XS GIS Cut Line= 5
      1509681.17       880524.04      1509560.53        880410.3
        1509464.       880375.82      1509377.82       880375.82
      1509243.39       880355.14
#Sta/Elev= 30
  4691.3  855.14    4716  852.42  4733.8  850.83  4756.9  848.08  4774.8  845.43
    4804  840.13  4837.2  832.27  4842.2  830.97  4849.8  828.45  4855.3  827.73
    4866  826.74    4900  827.58  4915.7  827.15  4967.8  828.09  4985.5  824.84
  4986.1  823.36  4987.1  820.36  5012.9  820.36  5013.9  823.36  5023.9  826.98
  5054.5  826.75  5061.8  827.26    5067   829.1  5075.6  830.94  5088.8  832.42
  5110.9   833.9  5149.6  841.69  5161.9  844.81    5166  845.45  5181.8  849.53
#Mann= 3 ,-1 , 0
  4691.3     .07       0  4986.1    .045       0  5013.9      .1       0
Bank Sta=4986.1,5013.9
Exp/Cntr=0.3,0.1

Type RM Length L Ch R = 1 ,53017   ,489,489,489
BEGIN DESCRIPTION:
North Deep Creek 143.0
END DESCRIPTION:
XS GIS Cut Line= 4
      1509839.78        880417.2      1509553.64       880162.08
      1509408.84       880089.69      1509167.56       880120.71
#Sta/Elev= 30
  4496.1  851.02  4511.9   849.6  4545.9  843.17  4554.2  842.41  4601.4  834.55
  4629.8  830.34  4667.1  826.53  4682.3     826  4693.4  826.55  4714.4  826.11
  4746.8  826.88  4770.6  826.41  4835.6  827.01  4851.2  826.56  4892.4  827.23
  4908.1  826.69  4972.5  827.62  4980.1  823.25  4981.6  820.25  5018.4  820.25
  5019.9  823.25  5030.2  828.04  5045.2  827.75  5054.9  828.52  5061.5  828.21
  5108.2  829.71  5164.4  833.58  5215.2  839.64  5250.6   845.2  5284.6  849.33
#Mann= 3 ,-1 , 0
  4496.1     .07       0  4980.1    .045       0  5019.9     .07       0
#XS Ineff= 2 , 0
       0                  5097.9       0  839.88
Permanent Ineff=
       F       F
Bank Sta=4980.1,5019.9
Exp/Cntr=0.3,0.1

Type RM Length L Ch R = 1 ,52528   ,331,331,331
BEGIN DESCRIPTION:
North Deep Creek 142.0
END DESCRIPTION:
XS GIS Cut Line= 4
       1510094.9       880141.41      1509867.35       879989.71
      1509312.32       879924.21      1509053.77       879965.58
#Sta/Elev= 30
  4757.1   849.9  4838.6  842.53  4850.3  842.13  4863.6  840.96  4937.9   833.6
  4975.5  826.24  4978.1  826.33  4980.1  821.66  4981.6  818.66  5018.4  818.66
  5019.9  821.66  5027.1  826.93  5031.3  827.32  5057.9   825.4  5063.4  825.45
  5127.3  825.08  5201.3  825.69  5218.4  825.38  5226.5  825.76  5290.3  825.31
  5463.9  825.79    5514  825.41  5565.7  825.59  5603.8  826.52  5645.6  828.32
  5661.4  829.68  5686.5  832.48  5744.5   840.4  5774.1  842.93  5851.3  848.24
#Mann= 5 ,-1 , 0
  4757.1     .07       0  4863.6     .14       0  4980.1    .045       0
  5019.9     .14       0  5063.4     .07       0
#XS Ineff= 2 , 0
       0                  5366.9       0  839.13
Permanent Ineff=
       F       F
Bank Sta=4980.1,5019.9
Exp/Cntr=0.3,0.1

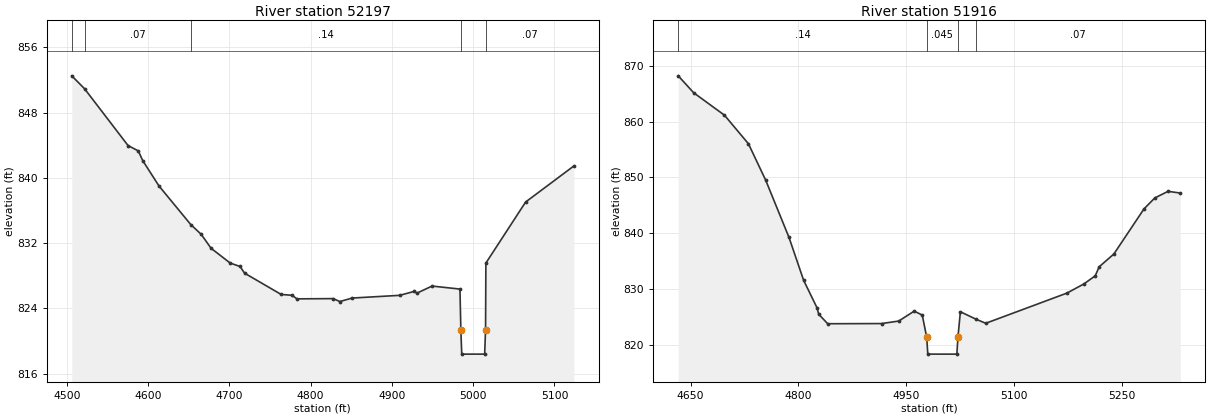
Type RM Length L Ch R = 1 ,52197   ,281,281,281
BEGIN DESCRIPTION:
North Deep Creek 141.0
END DESCRIPTION:
XS GIS Cut Line= 4
      1510236.25       880065.57      1510081.09        879931.1
      1509919.06       879710.47      1509905.28       879572.61
#Sta/Elev= 30
  4506.2  852.52  4521.9  850.94  4575.4  843.97    4588  843.31  4593.5  842.12
  4613.4  839.02  4652.7  834.26  4665.4  833.08  4677.5  831.37  4701.1  829.55
  4713.2  829.13  4718.8  828.31  4763.8   825.7  4777.1   825.6  4783.2  825.16
  4827.7  825.19    4836  824.83  4851.1  825.26  4909.5  825.59  4927.3  826.07
    4931  825.87  4949.4  826.73  4983.7  826.36  4984.8  821.38  4985.9  818.38
  5014.1  818.38  5015.2  821.38  5015.6  829.55  5064.5  837.04  5123.8  841.46
#Mann= 5 ,-1 , 0
  4506.2     .14       0  4521.9     .07       0  4652.7     .14       0
  4984.8    .045       0  5015.2     .07       0
Bank Sta=4984.8,5015.2
Exp/Cntr=0.3,0.1

Type RM Length L Ch R = 1 ,51916   ,594,594,594
BEGIN DESCRIPTION:
North Deep Creek 140.0
END DESCRIPTION:
XS GIS Cut Line= 4
      1510429.25       879882.82      1510291.38       879775.97
      1510156.93       879582.91      1509894.96       879462.27
#Sta/Elev= 30
  4632.8  868.23  4654.2   865.2  4697.1  861.17  4730.4  856.05  4754.4  849.52
  4786.8  839.26  4807.2  831.55  4825.8  826.63  4828.1  825.49  4840.6  823.78
  4915.6  823.81  4939.4  824.26  4960.9  826.04  4972.1  825.33  4978.3  821.33
  4979.8  818.33  5020.2  818.33  5021.7  821.33  5025.1  825.93    5047  824.58
  5060.4  823.86  5173.2  829.27  5196.9  830.92  5212.6  832.37  5218.1  833.99
  5238.5  836.28  5280.4  844.37  5295.4  846.33  5313.9  847.52  5330.9  847.21
#Mann= 4 ,-1 , 0
  4632.8     .14       0  4978.3    .045       0  5021.7     .14       0
    5047     .07       0
Bank Sta=4978.3,5021.7
Exp/Cntr=0.3,0.1