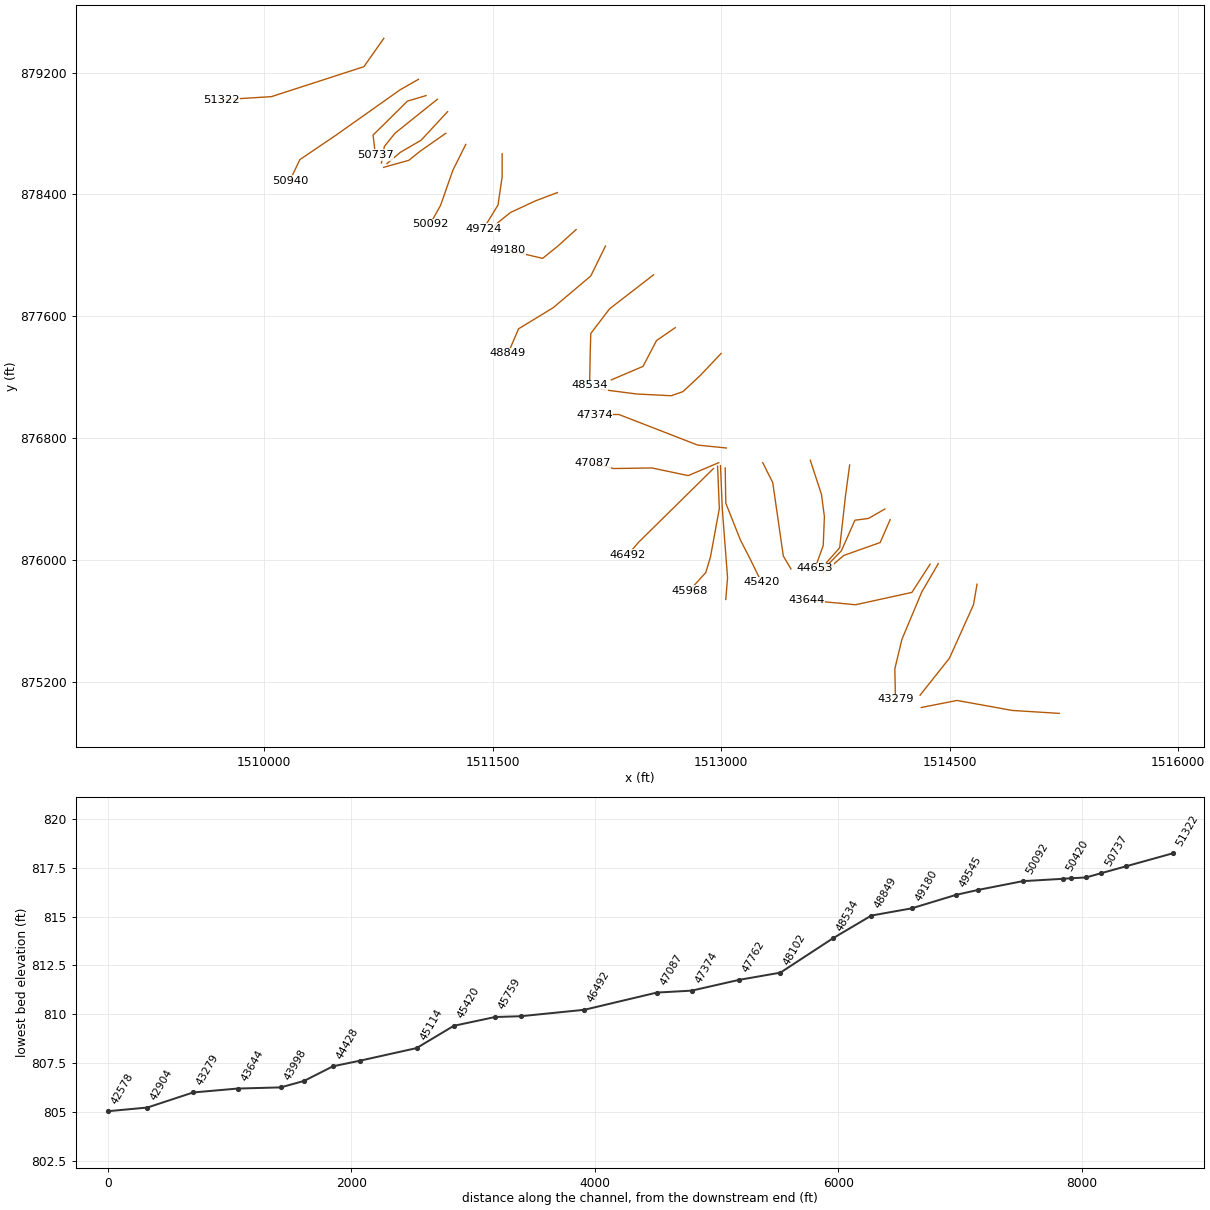
HEC-RAS study North Deep Creek.prj: North Deep Creek Limited Detail Study

--- North Deep Creek.g01 (geometry) --- (continued)

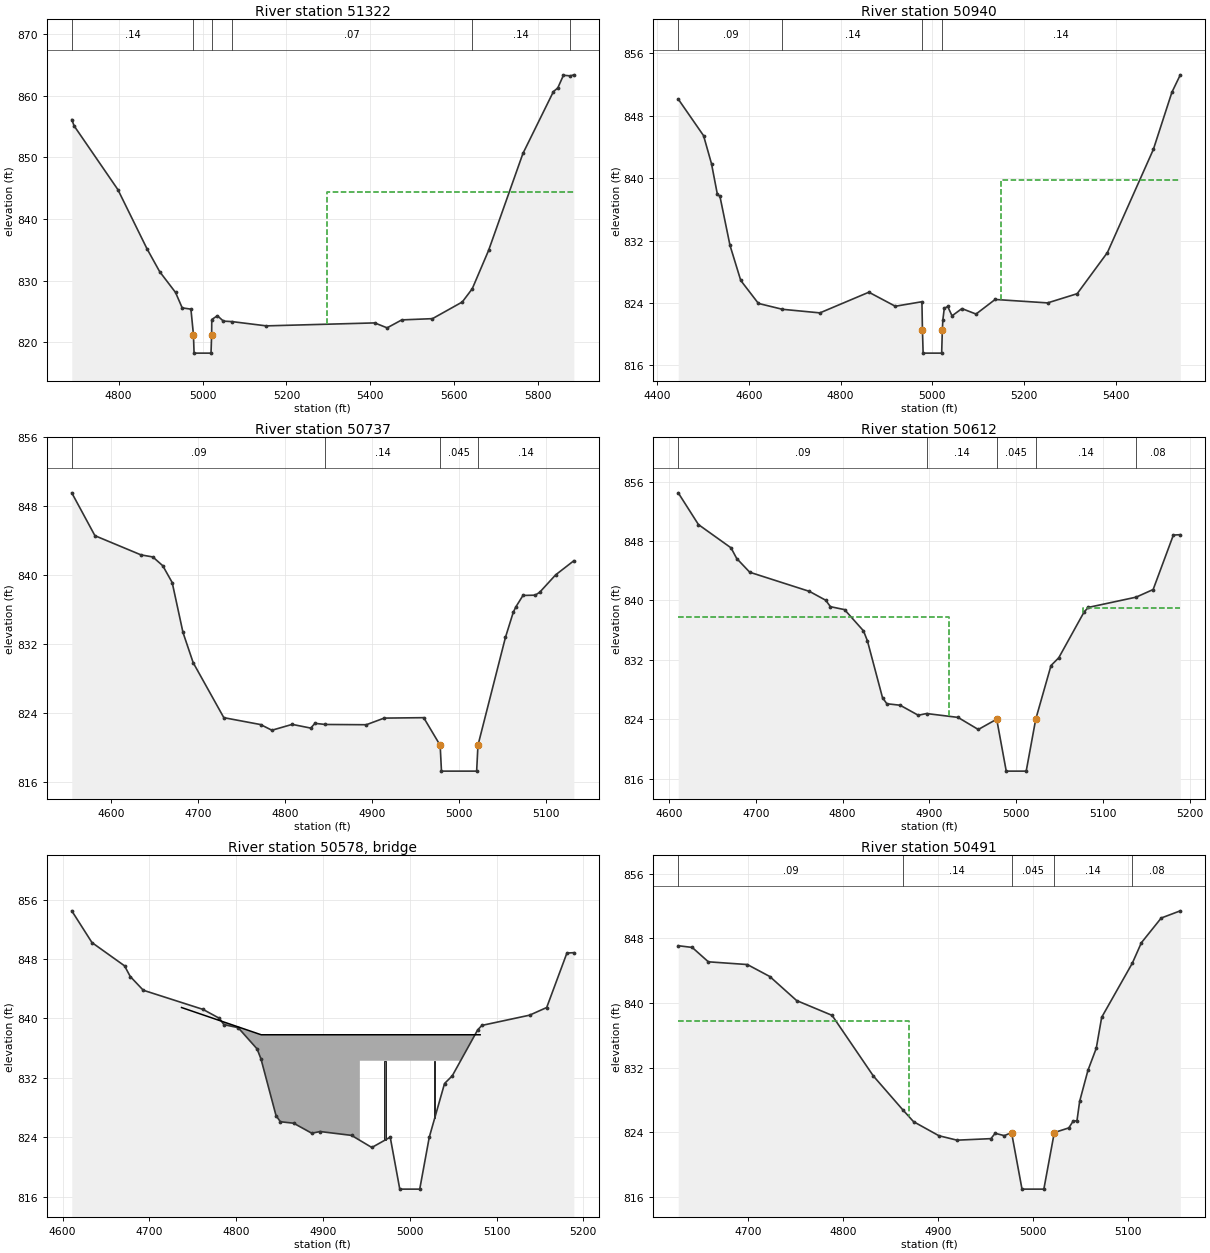
Type RM Length L Ch R = 1 ,51322   ,382,382,382
BEGIN DESCRIPTION:
North Deep Creek 139.0
END DESCRIPTION:
XS GIS Cut Line= 4
      1510784.39       879424.37      1510653.36       879238.17
      1510046.62       879041.67      1509715.62       879020.98
#Sta/Elev= 30
  4688.2  856.11  4693.9  855.07  4798.1  844.75  4867.5  835.16  4897.9  831.43
  4935.6  828.07  4951.5  825.57  4972.3  825.36  4978.3  821.23  4979.8  818.23
  5020.2  818.23  5021.7  821.23    5022  823.68  5035.4  824.29  5049.8  823.42
  5070.6  823.34  5152.1  822.65  5410.5  823.13  5440.1  822.33  5475.1  823.62
  5548.2  823.82  5619.2  826.52    5643  828.66  5682.1   834.9  5763.9  850.61
  5836.6  860.64    5847  861.23  5860.5  863.29  5877.1  863.19  5885.3  863.36
#Mann= 6 ,-1 , 0
  4688.2     .14       0  4978.3    .045       0  5021.7     .14       0
  5070.6     .07       0    5643     .14       0  5877.1     .07       0
#XS Ineff= 2 , 0
       0                  5296.8       0  844.34
Permanent Ineff=
       F       F
Bank Sta=4978.3,5021.7
Exp/Cntr=0.3,0.1

Type RM Length L Ch R = 1 ,50940   ,203,203,203
BEGIN DESCRIPTION:
North Deep Creek 138.0
END DESCRIPTION:
XS GIS Cut Line= 5
      1511011.87       879155.42      1510891.24       879086.48
       1510467.2       878786.56      1510232.78       878627.98
      1510167.28       878490.09
#Sta/Elev= 30
  4446.2  850.14  4501.4  845.45  4518.7  841.85  4531.5  837.92    4537  837.69
    4559  831.38  4582.4  826.89  4620.9  823.94  4673.2  823.19  4754.9  822.73
  4861.6  825.38  4919.2  823.58  4977.2  824.16  4978.3  820.57  4979.8  817.57
  5020.2  817.57  5021.7  820.57  5022.8  821.83  5025.9  823.31  5033.4  823.55
  5042.8  822.35  5064.3  823.28  5095.1  822.58  5136.7  824.45    5251  824.01
  5315.5  825.19  5381.4  830.47  5481.5  843.69  5521.9  851.02  5540.2  853.25
#Mann= 4 ,-1 , 0
  4446.2     .09       0  4673.2     .14       0  4978.3    .045       0
  5021.7     .14       0
#XS Ineff= 2 , 0
       0                  5150.1       0  839.83
Permanent Ineff=
       F       F
Bank Sta=4978.3,5021.7
Exp/Cntr=0.3,0.1

Type RM Length L Ch R = 1 ,50737   ,125,125,125
BEGIN DESCRIPTION:
North Deep Creek 137.0
END DESCRIPTION:
XS GIS Cut Line= 5
      1511061.92       879048.57       1510939.5       879012.36
       1510772.3       878846.89      1510713.69       878790.01
      1510729.21       878658.99
#Sta/Elev= 30
  4555.3  849.55  4581.9  844.57  4634.8  842.34  4648.4   842.1  4659.8  841.08
  4670.6  839.13    4683  833.33  4694.7  829.82  4729.9  823.43  4772.1  822.63
  4785.1  821.97  4808.4  822.65  4829.7  822.22  4834.5  822.77  4846.5  822.64
  4893.5  822.61    4914  823.38  4959.4  823.43  4978.3  820.22  4979.8  817.22
  5020.2  817.22  5021.7  820.22  5053.3  832.77  5062.2  835.66  5065.1  836.28
  5073.4  837.63  5087.4  837.66  5092.6     838  5110.9  840.02  5131.8  841.66
#Mann= 4 ,-1 , 0
  4555.3     .09       0  4846.5     .14       0  4978.3    .045       0
  5021.7     .14       0
Bank Sta=4978.3,5021.7
Exp/Cntr=0.5,0.3

Type RM Length L Ch R = 1 ,50612   ,121,121,121
BEGIN DESCRIPTION:
Country Club Rd (NDC) us
END DESCRIPTION:
XS GIS Cut Line= 5
        1511136.       879024.43      1510972.25       878893.43
      1510856.76       878800.35      1510787.81       878714.16
      1510768.86        878605.6
#Sta/Elev= 30
  4610.5   854.5  4633.8  850.22  4671.3  847.09  4677.9  845.65  4692.9   843.8
  4761.7  841.22  4780.4  840.03  4785.9  839.16  4802.2  838.76    4824   835.9
  4828.5  834.56  4845.9   826.9  4850.9  826.08  4866.2  825.88  4887.1  824.53
  4896.7  824.76  4932.9  824.24  4956.3  822.61  4977.5     824  4988.5     817
  5011.5     817  5022.5     824  5040.1  831.23    5049  832.27  5078.3  838.46
  5083.1  839.06  5138.1  840.44  5157.8  841.47  5181.1  848.81  5189.1  848.86
#Mann= 5 ,-1 , 0
  4610.5     .09       0  4896.7     .14       0  4977.5    .045       0
  5022.5     .14       0  5138.1     .08       0
#XS Ineff= 2 , 0
       0  4922.5   837.8  5077.5       0  838.99
Permanent Ineff=
       F       F
Bank Sta=4977.5,5022.5
Exp/Cntr=0.5,0.3

Type RM Length L Ch R = 3 ,50578   ,,,
BEGIN DESCRIPTION:
Country Club Rd (NDC) tor
Structure ID: LDS_NDC_10
Approximate Survey Structure
END DESCRIPTION:
Bridge Culvert--1,0,-1,-1, 0
Deck Dist Width WeirC Skew NumUp NumDn MinLoCord MaxHiCord MaxSubmerge Is_Ogee
20,28,3,0, 7, 7, , , 0.95, 0, 1,1,,
    4737  4828.8  4942.5  4942.5  5057.5  5057.5  5081.1
  841.47   837.8   837.8   837.8   837.8   837.8   837.8
  796.99  796.99  796.99   834.3   834.3  796.99  796.99
    4737  4828.8  4942.5  4942.5  5057.5  5057.5  5081.1
  841.47   837.8   837.8   837.8   837.8   837.8   837.8
  796.99  796.99  796.99   834.3   834.3  796.99  796.99
Pier Skew, UpSta & Num, DnSta & Num=  ,4971.3, 2 ,4971.3, 2 , 0 , 0 , 0 ,0,0
     1.7     1.7
  823.31   834.3
     1.7     1.7
  823.61   834.3
Pier Skew, UpSta & Num, DnSta & Num=  ,5028.8, 2 ,5028.8, 2 , 0 , 0 , 0 ,0,0
     1.7     1.7
  826.53   834.3
     1.7     1.7
  824.08   834.3
Abutment Skew #Up #Dn= , 2 , 2
  4942.5  4962.8
   834.3  822.99
  4942.5  4962.8
   834.3  823.79
Abutment Skew #Up #Dn= , 2 , 2
  5037.3  5057.5
  830.04   834.3
  5037.3  5057.5
  824.51   834.3
BR Coef= 1 , 1 , 0 ,1.25, 0 ,,,0.8,-1,2,0,
WSPro=,,,, 1 ,,,, 0 ,,,, 0 ,,,,-1 ,-1 ,-1 , 0 , 0 , 0 , 0 , 0
BC Design=,, 0 ,, 0 ,,,,,,
BC HTab HWMax=854.5

Type RM Length L Ch R = 1 ,50491   ,71,71,71
BEGIN DESCRIPTION:
Country Club Rd (NDC) ds
END DESCRIPTION:
XS GIS Cut Line= 4
       1511203.2       878943.38      1511029.13       878755.53
      1510892.96       878676.24      1510805.02        878602.1
#Sta/Elev= 30
  4626.5  847.09  4641.2  846.88  4658.2   845.1  4699.3  844.76  4722.9  843.28
  4751.2   840.3  4788.5  838.47    4832  830.96  4862.8   826.8  4874.3  825.31
    4901  823.57  4920.1  823.02  4955.8  823.21  4960.2  823.87  4969.9  823.58
  4977.5  823.96  4988.5  816.96  5011.5  816.96  5022.5  823.96  5037.8  824.54
  5042.2  825.35  5046.4  825.44  5049.2  827.83  5057.9  831.65  5066.7   834.4
  5072.4  838.23  5104.7  844.94  5114.2  847.46  5135.1  850.52  5155.2  851.41
#Mann= 5 ,-1 , 0
  4626.5     .09       0  4862.8     .14       0  4977.5    .045       0
  5022.5     .14       0  5104.7     .08       0
#XS Ineff= 2 , 0
       0  4869.5   837.8  5130.5       0     841
Permanent Ineff=
       F       F
Bank Sta=4977.5,5022.5
Exp/Cntr=0.5,0.3

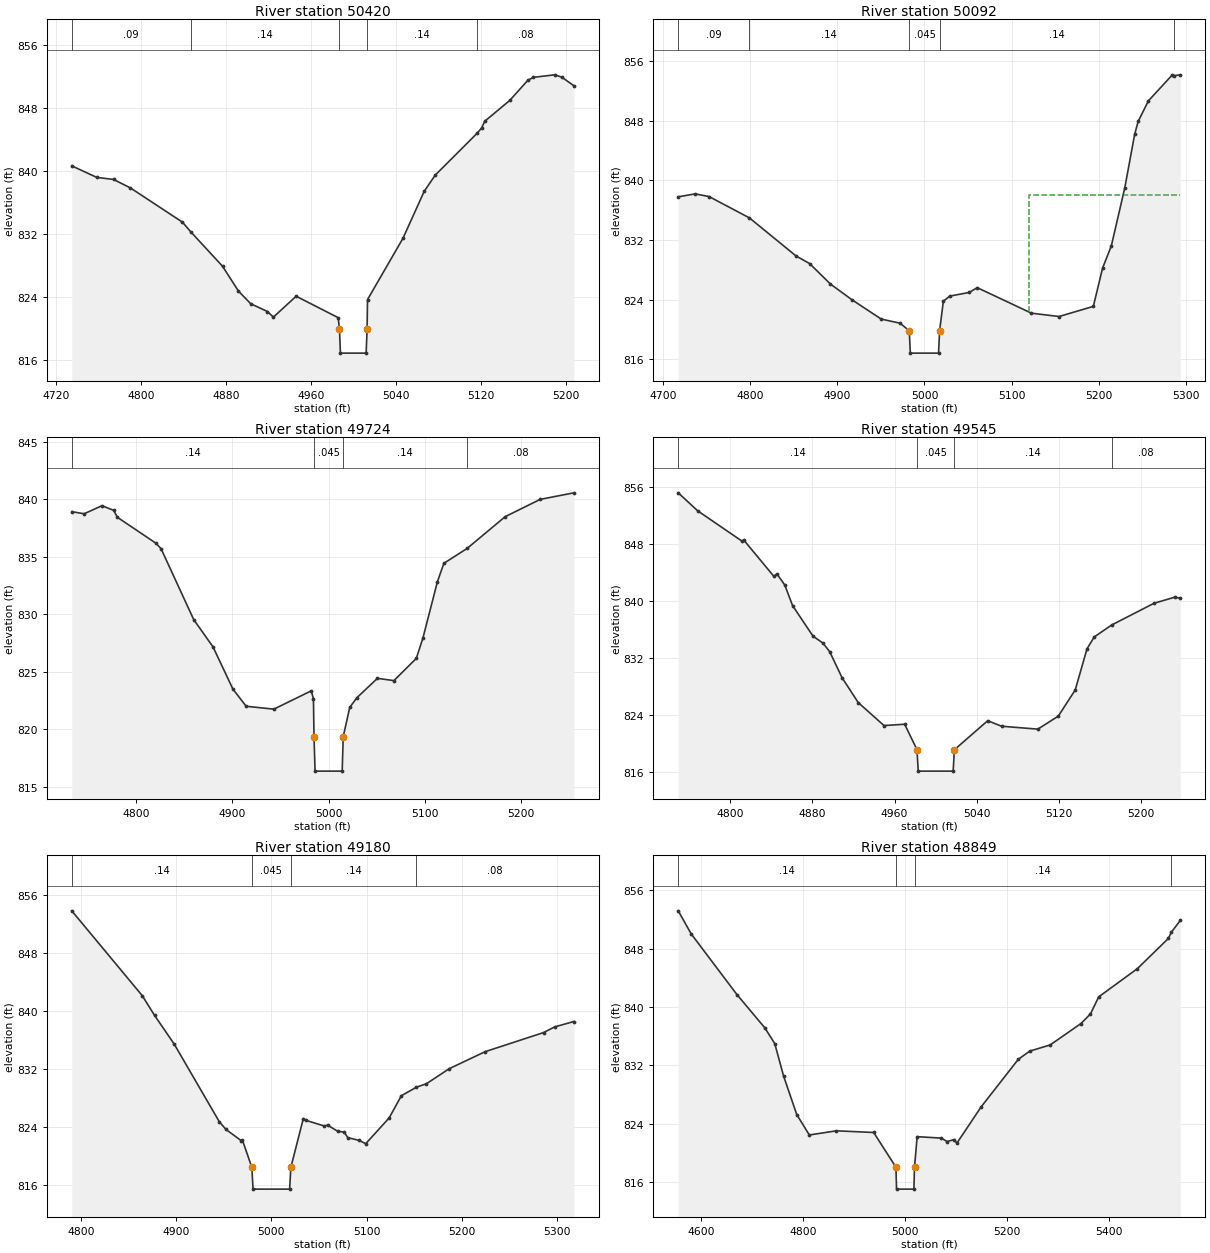
Type RM Length L Ch R = 1 ,50420   ,328,328,328
BEGIN DESCRIPTION:
North Deep Creek 136.0
END DESCRIPTION:
XS GIS Cut Line= 4
      1511191.26       878801.07      1511025.52       878685.44
      1510948.44       878623.78      1510782.77       878577.54
#Sta/Elev= 30
  4734.9  840.65  4758.4  839.19  4774.2  838.93  4790.2  837.85  4839.1  833.52
  4846.8  832.32  4876.9  827.93  4891.9  824.78  4903.4  823.19  4919.1   822.2
  4924.8  821.49  4946.2  824.14  4985.8  821.42    4987  819.93  4987.9  816.93
  5012.1  816.93    5013  819.93  5013.4  823.71  5046.8  831.48  5066.8  837.43
  5077.2  839.48  5116.4  844.75    5121  845.47  5123.7  846.29  5147.3  848.93
  5164.4  851.49  5169.6  851.86  5189.6  852.18  5196.3  851.89  5207.7   850.8
#Mann= 5 ,-1 , 0
  4734.9     .09       0  4846.8     .14       0    4987    .045       0
    5013     .14       0  5116.4     .08       0
Bank Sta=4987,5013
Exp/Cntr=0.3,0.1

Type RM Length L Ch R = 1 ,50092   ,368,368,368
BEGIN DESCRIPTION:
North Deep Creek 135.0
END DESCRIPTION:
XS GIS Cut Line= 4
      1511322.27       878727.85      1511237.48       878558.26
      1511156.55       878327.03      1511087.17        878203.7
#Sta/Elev= 30
  4717.5  837.78  4736.9  838.17  4752.9  837.81  4799.2  834.95  4852.7  829.84
  4868.3  828.82  4892.2  826.07  4916.7  823.98  4950.4  821.38  4972.1  820.82
  4982.6  819.81  4983.8  816.81  5016.2  816.81  5017.4  819.81  5021.7  823.77
  5029.1  824.46  5051.4  824.95  5060.6  825.59  5122.8  822.17  5154.4  821.72
  5193.8  823.08  5204.5  828.25  5214.4  831.17  5229.9  838.99  5241.2  846.15
  5245.2  847.88    5257  850.65    5284  854.08  5286.7  854.03  5293.6  854.14
#Mann= 5 ,-1 , 0
  4717.5     .09       0  4799.2     .14       0  4982.6    .045       0
  5017.4     .14       0  5286.7     .08       0
#XS Ineff= 2 , 0
       0                    5120       0     838
Permanent Ineff=
       F       F
Bank Sta=4982.6,5017.4
Exp/Cntr=0.3,0.1

Type RM Length L Ch R = 1 ,49724   ,179,179,179
BEGIN DESCRIPTION:
North Deep Creek 134.0
END DESCRIPTION:
XS GIS Cut Line= 4
       1511561.2       878666.18       1511561.2       878515.87
      1511534.22       878330.89      1511437.88       878172.89
#Sta/Elev= 30
  4732.8  838.92  4745.7  838.74  4764.2  839.44  4776.3  839.04  4780.3  838.43
  4820.5  836.17  4825.7   835.7  4859.7  829.53  4879.7  827.17  4900.4   823.5
  4914.2     822    4943  821.75  4981.9  823.34  4984.2  822.67  4984.8  819.36
  4985.9  816.36  5014.1  816.36  5015.2  819.36    5022  821.91  5029.6  822.76
  5050.8  824.43  5067.9  824.23  5091.2  826.16  5098.1  827.93  5113.2  832.84
  5119.9  834.43    5144  835.72  5183.7  838.49  5220.1  839.99  5255.1  840.56
#Mann= 4 ,-1 , 0
  4732.8     .14       0  4984.8    .045       0  5015.2     .14       0
    5144     .08       0
Bank Sta=4984.8,5015.2
Exp/Cntr=0.3,0.1

Type RM Length L Ch R = 1 ,49545   ,365,365,365
BEGIN DESCRIPTION:
North Deep Creek 133.0
END DESCRIPTION:
XS GIS Cut Line= 4
      1511923.47       878411.82      1511780.87       878357.86
      1511615.15       878280.79      1511495.69       878184.45
#Sta/Elev= 30
  4749.4  855.15  4768.3  852.63  4811.2   848.4  4813.4  848.49  4842.5  843.43
  4845.5  843.77  4853.1  842.22  4860.7  839.33  4880.6  835.04  4890.2  834.08
  4896.8  832.87  4908.9  829.21  4924.6  825.73  4949.7   822.5  4969.8  822.69
  4981.8  819.11    4983  816.11    5017  816.11  5018.2  819.11  5050.6  823.18
  5064.1  822.41  5099.4     822  5119.3  823.82  5135.8  827.49  5147.3  833.27
  5154.3  834.93  5171.3  836.61  5212.4  839.65  5232.9  840.52  5238.1  840.36
#Mann= 4 ,-1 , 0
  4749.4     .14       0  4981.8    .045       0  5018.2     .14       0
  5171.3     .08       0
Bank Sta=4981.8,5018.2
Exp/Cntr=0.3,0.1

Type RM Length L Ch R = 1 ,49180   ,331,331,331
BEGIN DESCRIPTION:
North Deep Creek 131.0
END DESCRIPTION:
XS GIS Cut Line= 4
      1512046.82       878169.06      1511927.32       878061.12
      1511827.12       877980.19      1511595.86       878034.15
#Sta/Elev= 30
  4790.4  853.78  4864.4  842.09  4877.4  839.36  4897.9  835.43  4945.3  824.72
  4952.4  823.64  4968.3  822.11  4969.6  822.19  4979.5  818.42  4980.8  815.42
  5019.2  815.42  5020.5  818.42  5033.6  825.15  5036.1  824.91  5055.4  824.13
  5059.1  824.24  5069.6   823.4  5076.6  823.27  5080.2  822.52  5092.4  822.13
  5099.1  821.68  5123.7  825.23  5136.6   828.3  5152.4  829.47  5162.9  829.95
  5186.8  832.02  5224.6  834.37  5285.9     837  5297.5  837.78  5317.7  838.52
#Mann= 4 ,-1 , 0
  4790.4     .14       0  4979.5    .045       0  5020.5     .14       0
  5152.4     .08       0
Bank Sta=4979.5,5020.5
Exp/Cntr=0.3,0.1

Type RM Length L Ch R = 1 ,48849   ,315,315,315
BEGIN DESCRIPTION:
North Deep Creek 130.0
END DESCRIPTION:
XS GIS Cut Line= 5
      1512239.48       878061.13      1512143.13       877864.57
      1511896.48       877656.47      1511669.11       877517.73
      1511599.73       877355.84
#Sta/Elev= 30
  4555.1  853.18  4580.4  850.03  4670.1  841.71  4724.8  837.15  4744.3  834.99
  4761.6  830.54  4787.4  825.27    4812  822.47  4865.2  823.04  4938.2  822.81
  4981.8  818.05    4983  815.05    5017  815.05  5018.2  818.05  5023.4  822.24
  5070.7  822.04  5082.1  821.57  5095.4  821.83  5101.3  821.35  5148.8  826.32
  5221.6  832.83  5244.1  833.96    5284   834.8  5344.3  837.73  5363.1  839.05
  5379.2  841.39  5454.9  845.25  5515.7  849.39  5521.7  850.25  5539.2  851.87
#Mann= 4 ,-1 , 0
  4555.1     .14       0  4981.8    .045       0  5018.2     .14       0
  5521.7     .08       0
Bank Sta=4981.8,5018.2
Exp/Cntr=0.3,0.1

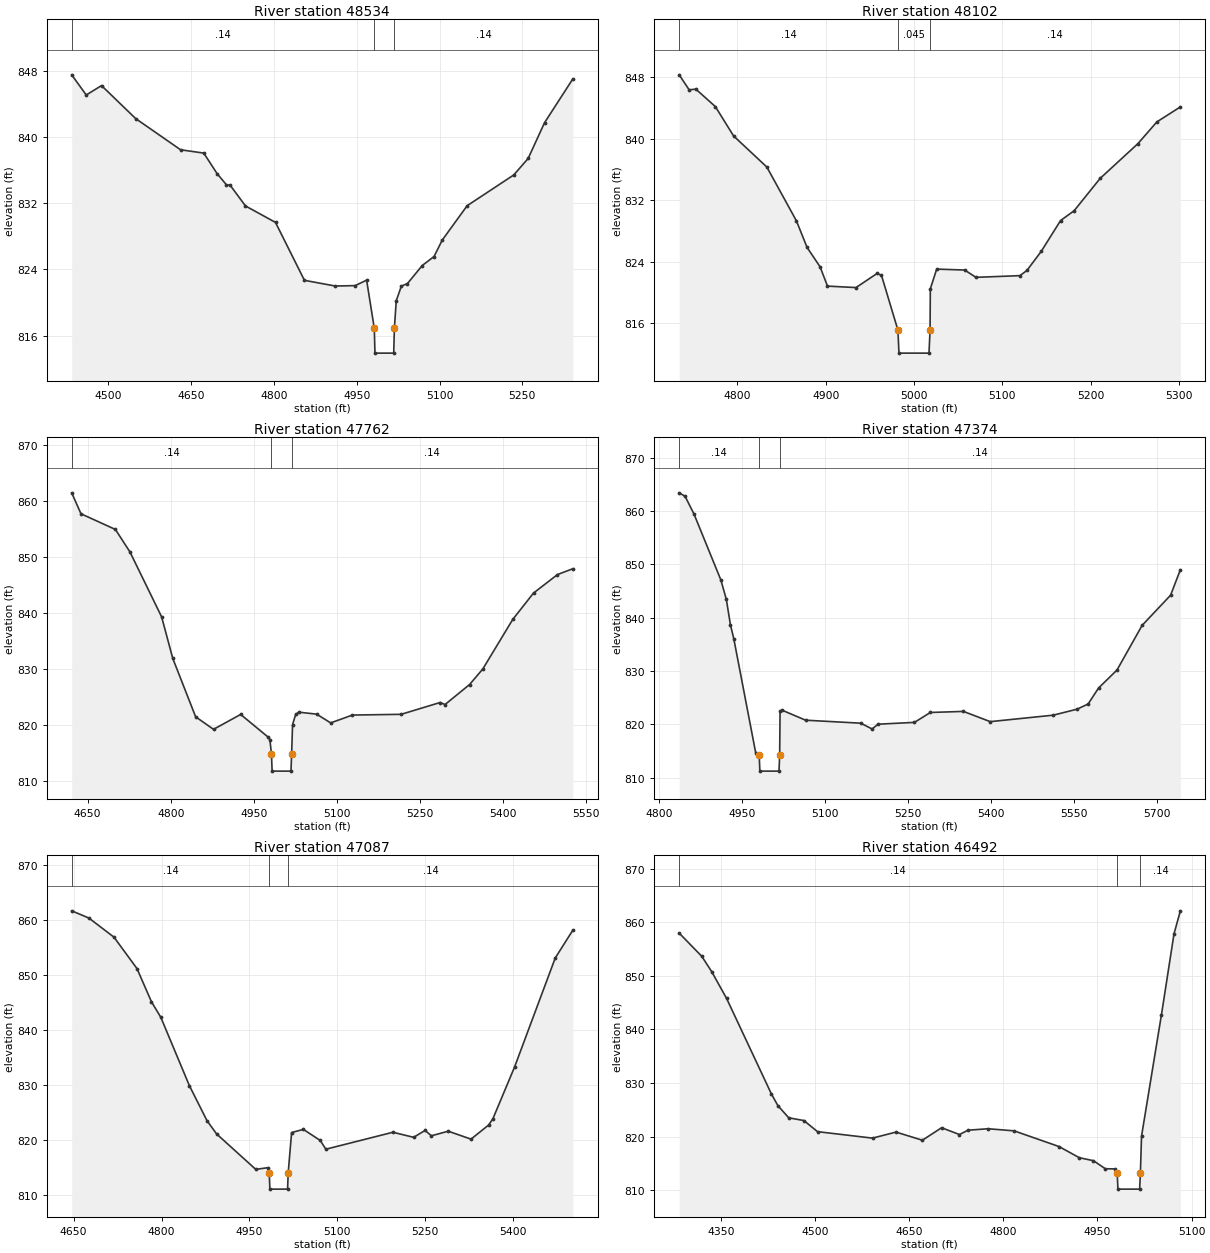
Type RM Length L Ch R = 1 ,48534   ,432,432,432
BEGIN DESCRIPTION:
North Deep Creek 129.0
END DESCRIPTION:
XS GIS Cut Line= 5
      1512555.51        877872.3      1512266.45       877648.76
      1512143.13        877486.9      1512139.28       877359.72
      1512135.42       877147.79
#Sta/Elev= 30
  4433.5  847.53  4459.8  845.09  4487.5  846.23  4549.4  842.24  4630.8  838.47
  4672.8  838.07  4696.9  835.59  4713.7  834.25  4720.7  834.18  4748.4  831.68
  4802.8  829.69  4855.2  822.69  4911.1     822  4947.1  822.05  4967.9  822.71
  4981.8  816.89    4983  813.89    5017  813.89  5018.2  816.89  5021.6  820.23
  5030.9  821.99  5041.9   822.3  5068.7  824.48  5090.1  825.57    5105  827.56
  5150.1  831.71  5234.6  835.43  5260.6  837.42  5290.3  841.74  5341.6  847.04
#Mann= 3 ,-1 , 0
  4433.5     .14       0  4981.8    .045       0  5018.2     .14       0
Bank Sta=4981.8,5018.2
Exp/Cntr=0.3,0.1

Type RM Length L Ch R = 1 ,48102   ,340,340,340
BEGIN DESCRIPTION:
North Deep Creek 128.0
END DESCRIPTION:
XS GIS Cut Line= 4
      1512698.05       877525.42      1512574.76       877440.65
      1512486.12       877271.08      1512277.97       877182.43
#Sta/Elev= 30
  4734.3   848.3  4745.5  846.35  4753.1  846.44  4775.2  844.17  4795.8  840.36
  4833.5  836.31  4866.9  829.33    4879  825.87  4893.7  823.35  4902.1  820.84
  4934.4  820.65  4958.3  822.49  4963.2  822.24  4981.8  815.13    4983  812.13
    5017  812.13  5018.2  815.13  5018.5  820.49  5025.7  823.05  5057.4  822.93
  5070.1  821.98  5119.9   822.2  5127.8  822.87    5144  825.35  5165.9  829.36
  5181.3  830.64  5210.7  834.84  5253.4  839.35  5274.9  842.18  5301.5  844.13
#Mann= 3 ,-1 , 0
  4734.3     .14       0  4981.8    .045       0  5018.2     .14       0
Bank Sta=4981.8,5018.2
Exp/Cntr=0.3,0.1

Type RM Length L Ch R = 1 ,47762   ,388,388,388
BEGIN DESCRIPTION:
North Deep Creek 127.0
END DESCRIPTION:
XS GIS Cut Line= 6
      1512998.71        877355.9       1512863.8       877213.28
      1512748.18       877105.37       1512671.1       877078.39
      1512443.73       877089.95      1512204.81       877120.78
#Sta/Elev= 30
  4621.2  861.44  4637.9   857.7  4700.1   854.9  4726.3  850.89  4783.5   839.3
  4803.6  831.89  4844.9  821.46  4877.2  819.22  4926.2  821.88  4975.7  817.84
    4979  817.38  4981.8  814.76    4983  811.76    5017  811.76  5018.2  814.76
  5019.9  820.06  5025.6   821.9  5031.6  822.28  5063.4  821.93  5088.7  820.37
    5128  821.77  5215.9   821.9  5286.3  824.01  5295.2  823.65  5339.5  827.22
  5363.4     830  5417.4  838.84  5454.9  843.55  5498.2  846.85  5525.9  847.89
#Mann= 3 ,-1 , 0
  4621.2     .14       0  4981.8    .045       0  5018.2     .14       0
Bank Sta=4981.8,5018.2
Exp/Cntr=0.3,0.1

Type RM Length L Ch R = 1 ,47374   ,287,287,287
BEGIN DESCRIPTION:
North Deep Creek 126.0
END DESCRIPTION:
XS GIS Cut Line= 4
      1513033.34        876735.4      1512844.53       876754.67
      1512328.11       876955.07      1512166.24       876955.07
#Sta/Elev= 30
    4837  863.45  4847.6  862.79  4863.8  859.44  4912.3  847.07  4922.1  843.45
  4929.5  838.69  4935.7     836  4975.4  814.53  4981.5  814.21  4982.7  811.21
  5017.3  811.21  5018.5  814.21  5019.2  822.48  5023.5  822.62  5065.4  820.77
    5165  820.21  5185.6  819.12  5196.2  820.02  5262.1  820.36  5290.8  822.22
  5350.6  822.42    5399   820.5  5512.7  821.71    5556  822.84  5575.9  823.81
  5594.7   826.8  5628.1  830.19  5673.5  838.57    5725  844.24  5742.6  849.01
#Mann= 3 ,-1 , 0
    4837     .14       0  4981.5    .045       0  5018.5     .14       0
Bank Sta=4981.5,5018.5
Exp/Cntr=0.3,0.1

Type RM Length L Ch R = 1 ,47087   ,595,595,595
BEGIN DESCRIPTION:
North Deep Creek 125.0
END DESCRIPTION:
XS GIS Cut Line= 5
      1512983.27       876639.06      1512782.87       876554.27
      1512543.93       876604.37      1512293.43       876600.52
      1512154.66       876635.21
#Sta/Elev= 30
  4646.7  861.66    4676  860.35  4718.9  856.87  4758.1  851.17  4782.8  845.14
  4798.7  842.33  4847.5  829.91  4877.7  823.52  4894.1  821.12  4960.8   814.7
  4981.2     815  4983.8  814.11  4984.9  811.11  5015.1  811.11  5016.2  814.11
    5022  821.39  5042.1  821.96  5070.9  819.95  5080.4  818.36  5194.9  821.44
  5230.3  820.52  5249.7  821.77  5260.6   820.8  5289.4  821.63  5328.2  820.19
  5358.1  822.74  5365.5  823.88  5402.5  833.28    5472   853.1    5502  858.15
#Mann= 3 ,-1 , 0
  4646.7     .14       0  4983.8    .045       0  5016.2     .14       0
Bank Sta=4983.8,5016.2
Exp/Cntr=0.3,0.1

Type RM Length L Ch R = 1 ,46492   ,524,524,524
BEGIN DESCRIPTION:
North Deep Creek 124.0
END DESCRIPTION:
XS GIS Cut Line= 3
      1512948.58       876600.52      1512455.29       876114.93
      1512385.91       876033.99
#Sta/Elev= 30
  4283.4  857.97  4319.3  853.65    4335  850.81  4358.9  845.79  4430.2  828.01
  4440.6  825.81  4457.9  823.53  4482.1  823.02  4503.8  820.95  4591.5  819.74
  4628.9  820.87    4671  819.35  4701.6  821.68  4730.1  820.41  4743.7  821.22
  4775.7  821.49  4817.1   821.1  4888.8  818.17  4921.1  816.09  4943.7  815.53
  4962.6  814.03  4978.6     814  4981.5  813.23  4982.7  810.23  5017.3  810.23
  5018.5  813.23  5020.3   820.1  5052.1  842.78  5072.1  857.85  5082.2  862.13
#Mann= 3 ,-1 , 0
  4283.4     .14       0  4981.5    .045       0  5018.5     .14       0
Bank Sta=4981.5,5018.5
Exp/Cntr=0.3,0.1

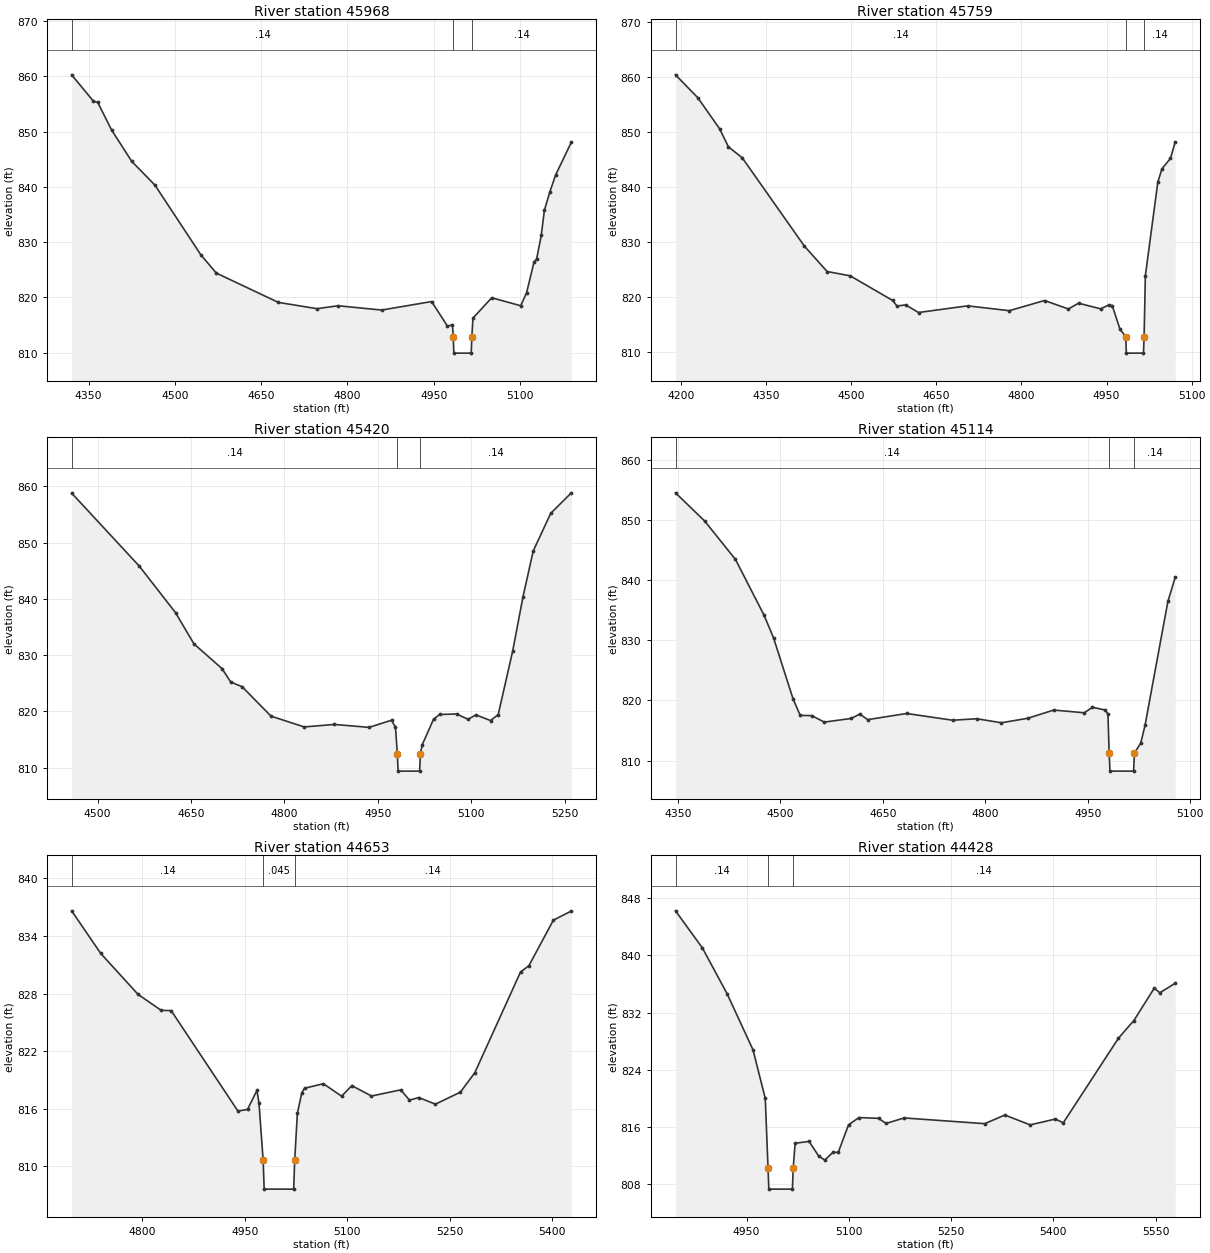
Type RM Length L Ch R = 1 ,45968   ,209,209,209
BEGIN DESCRIPTION:
North Deep Creek 123.0
END DESCRIPTION:
XS GIS Cut Line= 5
      1512975.56       876615.95      1512987.12       876338.46
      1512929.31       876022.44      1512898.48       875918.39
      1512790.57       875798.92
#Sta/Elev= 30
  4320.6   860.3  4358.3  855.54  4365.9  855.31  4389.9  850.33  4425.1  844.62
  4465.5  840.31  4545.1  827.71  4572.1  824.39  4679.8  819.09  4746.9  817.95
  4783.8  818.48  4859.4   817.7  4946.2  819.24  4973.8  814.79  4982.5  815.03
  4983.8   812.9  4984.9   809.9  5015.1   809.9  5016.2   812.9  5018.1  816.24
  5050.7  819.93  5101.1  818.48  5111.4  820.86  5124.1  826.34  5128.9  827.02
  5136.8  831.21  5142.2  835.75  5151.9  839.15  5161.9  842.19  5189.1   848.1
#Mann= 3 ,-1 , 0
  4320.6     .14       0  4983.8    .045       0  5016.2     .14       0
Bank Sta=4983.8,5016.2
Exp/Cntr=0.3,0.1

Type RM Length L Ch R = 1 ,45759   ,339,339,339
BEGIN DESCRIPTION:
North Deep Creek 122.0
END DESCRIPTION:
XS GIS Cut Line= 4
      1512994.83       876619.79      1513006.39       876338.46
      1513041.07        875883.7      1513029.51       875741.11
#Sta/Elev= 30
  4190.3  860.42  4229.7  856.25    4268  850.63  4283.5  847.35  4307.9  845.35
  4417.4  829.31  4457.6  824.68  4498.1  823.91    4573  819.43  4580.7  818.42
    4596  818.62  4618.6  817.24  4705.1  818.45  4778.6  817.57  4840.7  819.42
  4882.7  817.88  4900.6  818.93  4939.5  817.91  4954.3  818.63    4960   818.5
  4973.7  814.21  4983.8  812.86  4984.9  809.86  5015.1  809.86  5016.2  812.86
  5018.4  823.92  5040.4  840.94  5047.8  843.38  5062.7  845.23    5071  848.22
#Mann= 3 ,-1 , 0
  4190.3     .14       0  4983.8    .045       0  5016.2     .14       0
Bank Sta=4983.8,5016.2
Exp/Cntr=0.3,0.1

Type RM Length L Ch R = 1 ,45420   ,306,306,306
BEGIN DESCRIPTION:
North Deep Creek 121.0
END DESCRIPTION:
XS GIS Cut Line= 5
      1513025.66       876604.38      1513029.51       876373.14
      1513125.86       876130.35      1513187.52       876010.88
      1513264.58        875852.9
#Sta/Elev= 30
  4458.3  858.78    4567  845.81  4625.3  837.53  4654.8     832  4699.9  827.61
  4713.8  825.23    4732  824.41  4778.6  819.17  4831.8  817.26  4880.5   817.7
    4936  817.18  4972.2  818.45  4978.5  817.19  4981.5  812.41  4982.7  809.41
  5017.3  809.41  5018.5  812.41  5021.2  814.04  5039.6  818.61  5049.3  819.47
  5076.6  819.56    5095  818.61  5107.7   819.4  5131.2  818.39  5143.5  819.44
  5166.9   830.8  5183.2   840.3  5199.8  848.52  5227.9  855.19    5261  858.83
#Mann= 3 ,-1 , 0
  4458.3     .14       0  4981.5    .045       0  5018.5     .14       0
Bank Sta=4981.5,5018.5
Exp/Cntr=0.3,0.1

Type RM Length L Ch R = 1 ,45114   ,461,461,461
BEGIN DESCRIPTION:
North Deep Creek 120.0
END DESCRIPTION:
XS GIS Cut Line= 4
      1513272.31       876639.04      1513337.82       876508.03
      1513407.19        876026.3      1513457.31       875941.48
#Sta/Elev= 30
  4346.5  854.48  4389.3  849.79  4434.3  843.42    4476   834.2  4490.1  830.39
  4518.5  820.31  4529.1  817.53  4546.2  817.48  4564.3  816.41  4603.4  817.01
  4616.4  817.74  4627.9  816.82    4685  817.84  4752.4  816.72  4787.6  816.97
  4823.7   816.3  4862.1  817.04  4900.3  818.41  4945.1  817.96  4957.1  818.87
    4976  818.41  4979.7  817.73  4981.5  811.27  4982.7  808.27  5017.3  808.27
  5018.5  811.27  5027.8  812.94    5034  815.86  5067.5  836.44  5078.2  840.44
#Mann= 3 ,-1 , 0
  4346.5     .14       0  4981.5    .045       0  5018.5     .14       0
Bank Sta=4981.5,5018.5
Exp/Cntr=0.3,0.1

Type RM Length L Ch R = 1 ,44653   ,225,225,225
BEGIN DESCRIPTION:
North Deep Creek 119.0
END DESCRIPTION:
XS GIS Cut Line= 5
      1513584.45       876654.52      1513657.69       876430.95
      1513676.95        876284.5      1513669.25       876095.67
      1513615.28       875945.32
#Sta/Elev= 30
  4696.5  836.62  4739.1  832.18  4793.8  827.91  4827.5  826.26  4842.3  826.22
    4940  815.76    4954  815.93  4967.8  817.91  4970.8  816.61  4976.9  810.63
  4978.4  807.63  5021.6  807.63  5023.1  810.63    5027  815.51  5033.5  817.67
  5037.5  818.14  5065.1  818.61  5091.8  817.31  5106.7  818.41  5135.5  817.33
  5178.3  817.97  5191.2   816.9  5204.8  817.17  5229.2  816.48  5265.7  817.73
  5286.8  819.75  5353.8  830.25    5366   830.9  5401.9  835.65  5428.2   836.6
#Mann= 3 ,-1 , 0
  4696.5     .14       0  4976.9    .045       0  5023.1     .14       0
Bank Sta=4976.9,5023.1
Exp/Cntr=0.3,0.1

Type RM Length L Ch R = 1 ,44428   ,238,238,238
BEGIN DESCRIPTION:
North Deep Creek 118.0
END DESCRIPTION:
XS GIS Cut Line= 4
      1513842.67       876623.66      1513815.69       876423.24
      1513777.15       876080.25      1513653.83       875941.51
#Sta/Elev= 30
  4845.8  846.24  4885.2  841.06  4921.4  834.67  4959.5  826.81  4977.5  820.01
  4981.5  810.34  4982.7  807.34  5017.3  807.34  5018.5  810.34  5021.3  813.75
  5041.7  814.01  5055.8  811.97  5064.7   811.4  5077.1  812.51  5084.5  812.46
  5099.6  816.33  5114.9  817.34  5143.6  817.24  5154.7  816.52  5181.1  817.29
  5299.5  816.49  5328.9   817.7    5366  816.32  5403.2  817.14  5414.6   816.6
  5495.6  828.44  5518.2  830.91  5548.1  835.43  5556.3  834.79  5578.8  836.12
#Mann= 3 ,-1 , 0
  4845.8     .14       0  4981.5    .045       0  5018.5     .14       0
Bank Sta=4981.5,5018.5
Exp/Cntr=0.3,0.1

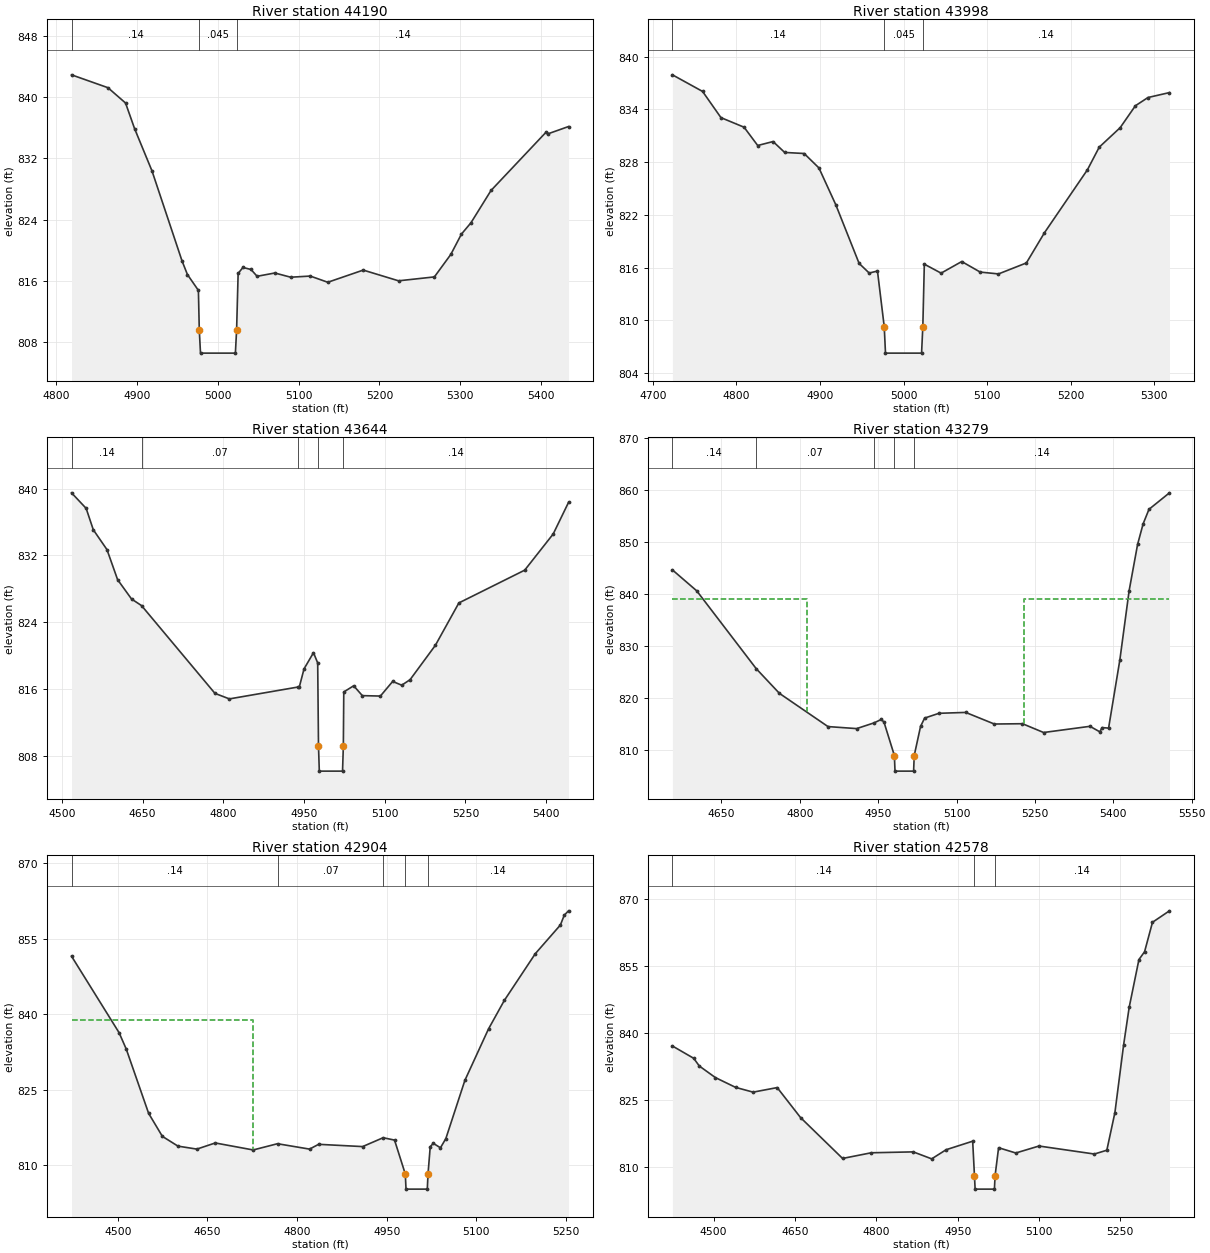
Type RM Length L Ch R = 1 ,44190   ,192,192,192
BEGIN DESCRIPTION:
North Deep Creek 117.0
END DESCRIPTION:
XS GIS Cut Line= 5
      1514073.91       876334.61      1513965.99       876272.94
      1513877.35       876261.38      1513788.72       876060.98
      1513661.54       875929.96
#Sta/Elev= 30
  4818.7  842.92  4863.8  841.24  4885.6  839.24  4896.8  835.89  4918.3  830.39
  4955.5  818.64  4962.2  816.85  4975.8  814.78  4976.9  809.59  4978.4  806.59
  5021.6  806.59  5023.1  809.59    5025  816.99  5030.9  817.77  5040.9  817.51
  5048.5  816.62  5070.4  817.05  5090.1   816.5  5114.3  816.65    5136  815.84
  5179.9  817.43  5223.6  816.03    5268  816.54  5288.3  819.47  5301.5  822.13
  5313.3  823.61  5338.1  827.82  5406.5  835.46  5409.2  835.24  5434.1  836.17
#Mann= 3 ,-1 , 0
  4818.7     .14       0  4976.9    .045       0  5023.1     .14       0
Bank Sta=4976.9,5023.1
Exp/Cntr=0.3,0.1

Type RM Length L Ch R = 1 ,43998   ,354,354,354
BEGIN DESCRIPTION:
North Deep Creek 116.0
END DESCRIPTION:
XS GIS Cut Line= 4
      1514108.59       876265.24      1514043.07       876114.93
      1513804.13       876030.15      1513669.29       875914.57
#Sta/Elev= 30
  4723.3  837.92  4759.4  836.03  4781.4  833.05  4809.1  831.96  4825.4  829.88
  4843.8  830.33  4857.7  829.09    4881  828.97  4898.7  827.33  4918.9  823.14
  4946.8  816.47  4958.9  815.37  4968.8   815.6  4976.9  809.26  4978.4  806.26
  5021.6  806.26  5023.1  809.26  5024.9  816.38    5045  815.36  5069.7  816.68
  5091.8  815.48  5113.7  815.27  5147.1  816.52  5168.7  819.95  5220.2  827.12
  5234.3  829.69  5259.4  831.91  5277.6   834.4  5292.7  835.34  5318.4   835.9
#Mann= 3 ,-1 , 0
  4723.3     .14       0  4976.9    .045       0  5023.1     .14       0
Bank Sta=4976.9,5023.1
Exp/Cntr=0.3,0.1

Type RM Length L Ch R = 1 ,43644   ,365,365,365
BEGIN DESCRIPTION:
North Deep Creek 115.0
END DESCRIPTION:
XS GIS Cut Line= 4
      1514370.67       875972.38      1514251.18       875787.36
      1513881.21       875706.43      1513557.54       875737.25
#Sta/Elev= 30
  4517.7  839.49  4544.9  837.63  4558.2  835.07  4583.6   832.7  4603.4   829.1
  4629.3  826.79  4647.9     826  4784.4   815.5  4811.2  814.84  4938.8  816.26
  4941.2  816.26    4950  818.43  4967.6  820.37  4975.4  819.14  4976.9   809.2
  4978.4   806.2  5021.6   806.2  5023.1   809.2  5023.9  815.67  5042.3  816.41
  5058.4  815.23    5092  815.18  5114.8  816.93  5131.6  816.48  5147.2  817.14
  5194.2  821.25  5237.9  826.32  5360.3  830.24  5413.3  834.57  5441.8  838.35
#Mann= 5 ,-1 , 0
  4517.7     .14       0  4647.9     .07       0  4938.8     .14       0
  4976.9    .045       0  5023.1     .14       0
Bank Sta=4976.9,5023.1
Exp/Cntr=0.3,0.1

Type RM Length L Ch R = 1 ,43279   ,375,375,375
BEGIN DESCRIPTION:
North Deep Creek 114.0
END DESCRIPTION:
XS GIS Cut Line= 5
      1514424.62       875976.23      1514316.69       875791.21
      1514185.66       875479.05      1514139.41       875286.36
      1514143.27         875086.
#Sta/Elev= 30
  4556.2  844.66  4602.7  840.64  4716.6  825.68    4761  820.94  4853.9  814.56
  4908.8  814.17  4942.1  815.27  4956.1  815.94  4961.2  815.39    4981     809
  4982.2     806  5017.8     806    5019     809  5031.1  814.59  5038.9  816.19
  5066.3  817.11  5117.5  817.28  5172.3  815.05  5226.2  815.11  5266.6  813.42
  5355.4  814.61  5374.2  813.55  5378.6  814.36    5391  814.27  5412.5  827.33
  5430.3  840.66  5446.5  849.56  5457.1  853.51  5468.3   856.3  5507.5  859.47
#Mann= 5 ,-1 , 0
  4556.2     .14       0  4716.6     .07       0  4942.1     .14       0
    4981    .045       0    5019     .14       0
#XS Ineff= 2 , 0
       0  4813.6  838.99  5229.3       0  838.99
Permanent Ineff=
       F       F
Bank Sta=4981,5019
Exp/Cntr=0.3,0.1

Type RM Length L Ch R = 1 ,42904   ,326,326,326
BEGIN DESCRIPTION:
North Deep Creek 113.0
END DESCRIPTION:
XS GIS Cut Line= 4
      1514678.96       875841.34      1514655.83       875706.43
      1514497.82       875355.73      1514305.13       875112.93
#Sta/Elev= 30
  4422.6   851.5  4502.2   836.3  4514.2  833.04  4551.6  820.28  4574.6  815.71
  4600.7  813.77  4632.3  813.18  4663.1   814.4  4726.5  813.01  4767.2  814.25
  4820.8  813.18    4836  814.13  4909.6  813.68  4943.9  815.44    4963  814.97
    4981  808.23  4982.2  805.23  5017.8  805.23    5019  808.23  5022.7  813.65
  5027.8  814.33  5039.8  813.44  5048.8  815.26  5080.7  826.84  5120.2  837.05
  5146.6   842.7  5198.5     852  5240.5   857.7  5246.9  859.64  5254.1  860.51
#Mann= 5 ,-1 , 0
  4422.6     .14       0  4767.2     .07       0  4943.9     .14       0
    4981    .045       0    5019     .14       0
#XS Ineff= 2 , 0
       0  4726.1  838.76               0
Permanent Ineff=
       F       F
Bank Sta=4981,5019
Exp/Cntr=0.3,0.1

Type RM Length L Ch R = 1 ,42578   ,326,326,326
BEGIN DESCRIPTION:
North Deep Creek 112.0
END DESCRIPTION:
XS GIS Cut Line= 4
      1515218.45       874993.47      1514910.18       875012.74
      1514547.92       875078.25      1514312.83       875032.01
#Sta/Elev= 30
    4424  837.05  4463.2   834.3  4473.6  832.57  4503.2  829.99  4540.6  827.79
  4572.8  826.73  4617.2  827.75  4660.3  821.04  4737.8   811.9  4790.7  813.17
  4868.1  813.37  4902.1  811.81  4928.7  813.85  4977.7  815.76    4981  808.04
  4982.2  805.04  5017.8  805.04    5019  808.04  5025.5   814.3  5057.2  813.12
    5100  814.68  5202.1  812.89  5225.1  813.74    5240  822.16  5256.1  837.34
  5266.4  845.75  5284.3  856.38  5294.7  858.13  5309.3  864.72  5340.6  867.28
#Mann= 3 ,-1 , 0
    4424     .14       0    4981    .045       0    5019     .14       0
Bank Sta=4981,5019
Exp/Cntr=0.3,0.1