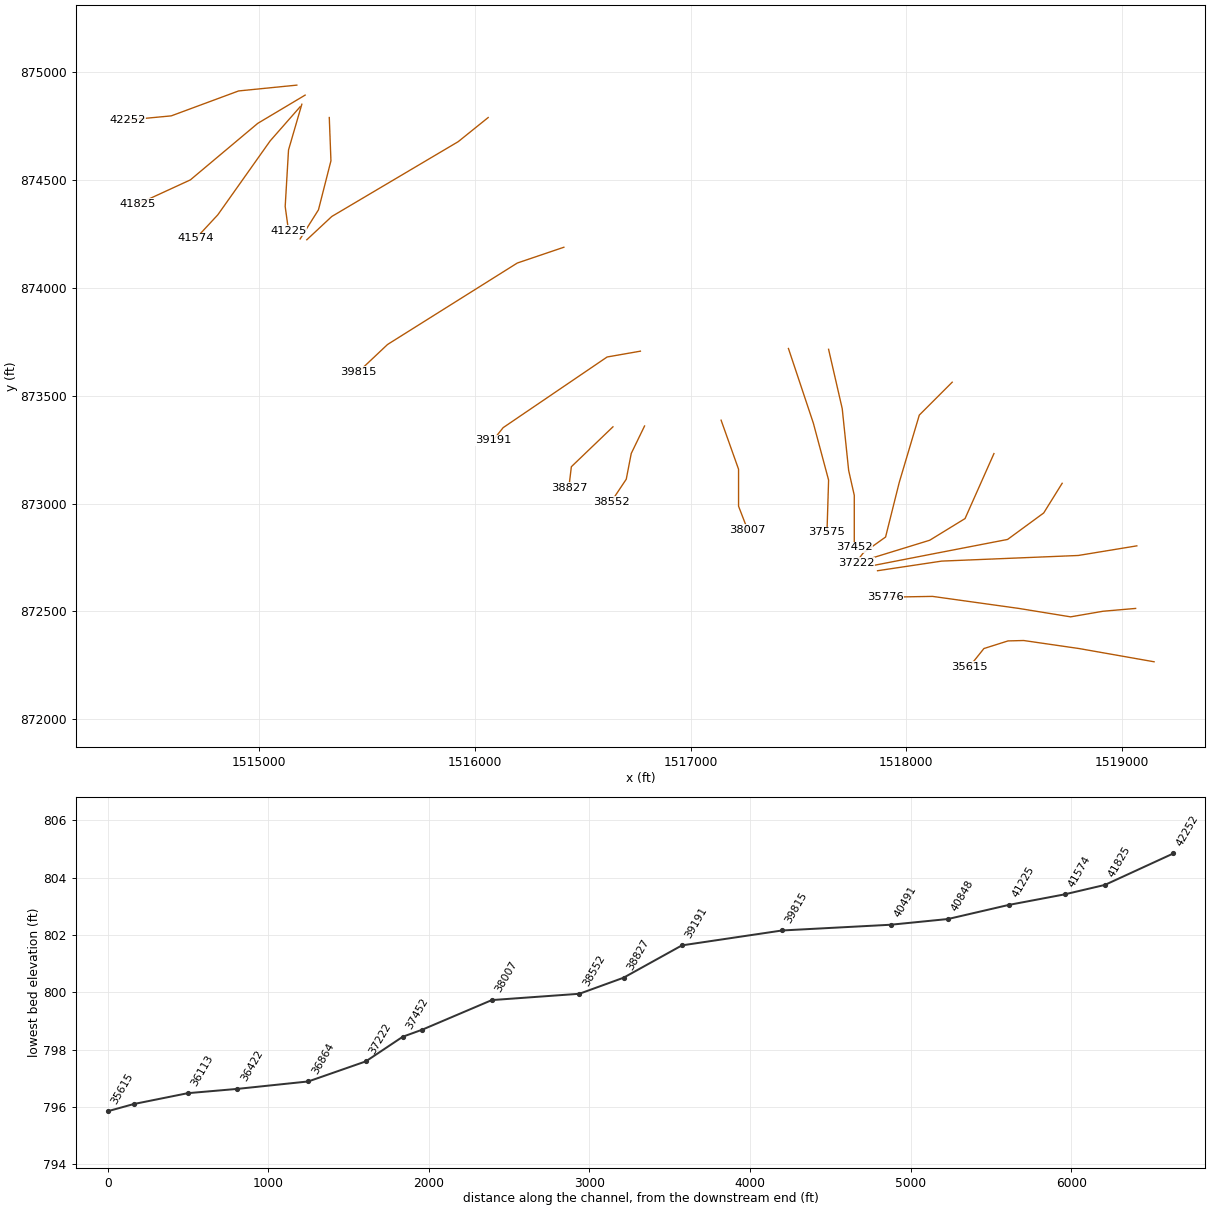
HEC-RAS study North Deep Creek.prj: North Deep Creek Limited Detail Study

--- North Deep Creek.g01 (geometry) --- (continued)

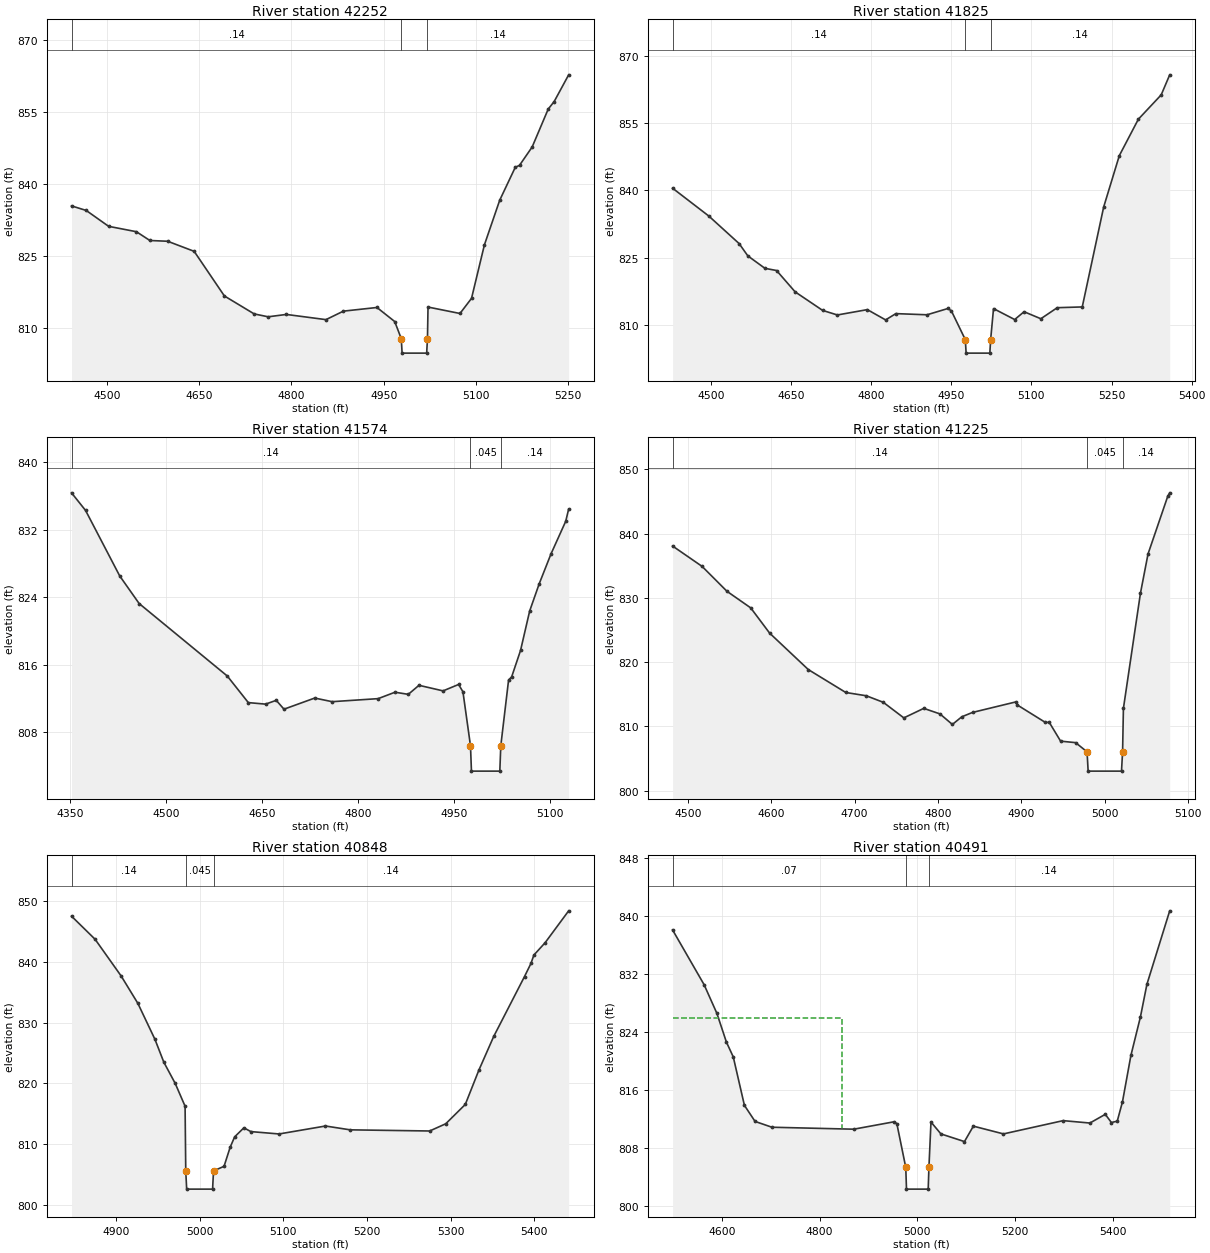
Type RM Length L Ch R = 1 ,42252   ,427,427,427
BEGIN DESCRIPTION:
North Deep Creek 111.0
END DESCRIPTION:
XS GIS Cut Line= 4
      1515176.05       874939.51      1514906.33       874912.54
      1514594.17       874796.92      1514389.93       874777.66
#Sta/Elev= 30
    4442  835.53  4465.9  834.58  4502.4  831.27  4547.6  830.15  4569.5  828.32
  4598.5  828.16  4641.6  826.06  4690.8  816.76  4739.3  813.02    4762  812.42
  4791.6  812.91  4856.1  811.83  4884.5   813.6  4939.1  814.36    4968  811.43
  4978.7  807.85    4980  804.85    5020  804.85  5021.3  807.85  5022.2  814.45
  5074.2  813.11    5093  816.26    5114  827.42  5138.9  836.72  5164.2  843.57
  5171.1  843.98  5191.7  847.81  5217.8   855.7  5227.5  857.27  5251.1  862.84
#Mann= 3 ,-1 , 0
    4442     .14       0  4978.7    .045       0  5021.3     .14       0
Bank Sta=4978.7,5021.3
Exp/Cntr=0.3,0.1

Type RM Length L Ch R = 1 ,41825   ,251,251,251
BEGIN DESCRIPTION:
North Deep Creek 110.0
END DESCRIPTION:
XS GIS Cut Line= 4
       1515214.6       874893.25      1514994.97       874762.24
       1514682.8       874500.18      1514440.01       874388.42
#Sta/Elev= 30
  4428.3  840.49    4496   834.3  4552.9  828.15  4569.2  825.41  4601.2  822.64
    4623  822.15  4657.7   817.4  4709.3  813.26  4736.8  812.25  4792.9  813.44
  4827.1  811.15  4846.3  812.55  4904.6  812.29    4944   813.7  4950.3  813.14
  4976.3  806.75  4977.8  803.75  5022.2  803.75  5023.7  806.75  5029.1  813.67
  5068.7  811.23  5086.3  812.97  5117.7  811.41  5148.4  813.87  5195.2  814.04
  5235.3   836.3  5264.6  847.75  5300.2  855.85    5343  861.28  5358.9  865.74
#Mann= 3 ,-1 , 0
  4428.3     .14       0  4976.3    .045       0  5023.7     .14       0
Bank Sta=4976.3,5023.7
Exp/Cntr=0.3,0.1

Type RM Length L Ch R = 1 ,41574   ,349,349,349
BEGIN DESCRIPTION:
North Deep Creek 109.0
END DESCRIPTION:
XS GIS Cut Line= 4
      1515191.54       874839.35      1515052.77       874681.31
      1514809.98       874338.32      1514709.78       874230.41
#Sta/Elev= 30
  4352.1   836.4  4374.1  834.31  4427.5  826.55  4457.9  823.28  4595.8  814.69
  4628.7  811.54  4655.7  811.36  4672.4  811.81  4684.5  810.76  4732.6  812.08
  4759.8  811.65  4831.8  812.01  4858.2  812.77    4879  812.52  4895.7  813.59
  4933.4  812.93  4957.7  813.69  4964.5  812.82  4976.3  806.42  4977.8  803.42
  5022.2  803.42  5023.7  806.42  5035.9  814.22  5040.7  814.59  5054.6  817.72
  5068.9   822.4  5083.8  825.62  5102.3  829.17  5125.3  833.03  5129.9  834.48
#Mann= 3 ,-1 , 0
  4352.1     .14       0  4976.3    .045       0  5023.7     .14       0
Bank Sta=4976.3,5023.7
Exp/Cntr=0.3,0.1

Type RM Length L Ch R = 1 ,41225   ,377,377,377
BEGIN DESCRIPTION:
North Deep Creek 108.0
END DESCRIPTION:
XS GIS Cut Line= 4
      1515199.23       874850.92      1515137.56       874638.92
      1515122.14       874376.86      1515137.55       874265.12
#Sta/Elev= 30
  4481.7  838.06  4517.1  834.89    4547  831.01  4575.4  828.44  4598.1  824.51
  4644.5  818.84  4689.4  815.28    4714  814.77  4734.4  813.75    4759  811.33
  4782.9  812.81  4802.3  811.95  4817.2  810.31  4828.5   811.5  4841.4  812.18
  4893.8  813.83  4894.8  813.36  4928.5  810.64  4933.4  810.63    4947  807.71
    4965  807.48  4978.7  806.05    4980  803.05    5020  803.05  5021.3  806.05
  5022.3  812.81  5042.7   830.7  5051.8  836.82  5075.5  845.81  5077.8  846.33
#Mann= 3 ,-1 , 0
  4481.7     .14       0  4978.7    .045       0  5021.3     .14       0
Bank Sta=4978.7,5021.3
Exp/Cntr=0.3,0.1

Type RM Length L Ch R = 1 ,40848   ,357,357,357
BEGIN DESCRIPTION:
North Deep Creek 107.0
END DESCRIPTION:
XS GIS Cut Line= 4
      1515326.39       874789.24       1515334.1       874588.82
      1515276.29       874361.44      1515191.51       874226.55
#Sta/Elev= 30
  4846.8  847.54    4875  843.73  4906.1  837.69  4926.1  833.18  4946.6  827.23
  4957.2  823.47  4970.8  819.98  4982.6  816.22  4983.4  805.56  4984.5  802.56
  5015.5  802.56  5016.6  805.56  5029.2  806.32  5036.5  809.46  5041.9  811.18
  5052.9  812.66  5061.3  812.04    5095  811.65  5150.5  812.96    5180  812.33
  5275.1  812.14  5294.3  813.33  5317.7  816.52  5333.9  822.16  5351.7  827.73
  5388.5  837.59  5396.2  839.75  5399.7  841.13  5413.1  843.16  5441.3  848.42
#Mann= 3 ,-1 , 0
  4846.8     .14       0  4983.4    .045       0  5016.6     .14       0
Bank Sta=4983.4,5016.6
Exp/Cntr=0.3,0.1

Type RM Length L Ch R = 1 ,40491   ,676,676,676
BEGIN DESCRIPTION:
North Deep Creek 106.0
END DESCRIPTION:
XS GIS Cut Line= 4
       1516062.5       874789.24      1515923.74       874677.46
      1515337.96       874330.61      1515222.34       874222.71
#Sta/Elev= 30
  4499.2  838.13  4563.8  830.56  4589.9  826.61  4609.3  822.66  4623.4   820.6
  4646.2  813.92    4668   811.7  4702.5   810.9  4869.9  810.63    4953  811.66
  4958.1  811.38  4976.3  805.36  4977.8  802.36  5022.2  802.36  5023.7  805.36
  5027.9  811.62  5048.2  809.98  5096.4  808.92  5114.6  811.05  5176.2  809.98
  5298.3  811.81    5353  811.48  5384.5  812.68    5397  811.55    5409  811.74
  5419.7  814.42  5436.9   820.8  5456.4  826.12  5469.7  830.63  5516.3  840.76
#Mann= 3 ,-1 , 0
  4499.2     .07       0  4976.3    .045       0  5023.7     .14       0
#XS Ineff= 2 , 0
       0  4846.4  825.92               0
Permanent Ineff=
       F       F
Bank Sta=4976.3,5023.7
Exp/Cntr=0.3,0.1

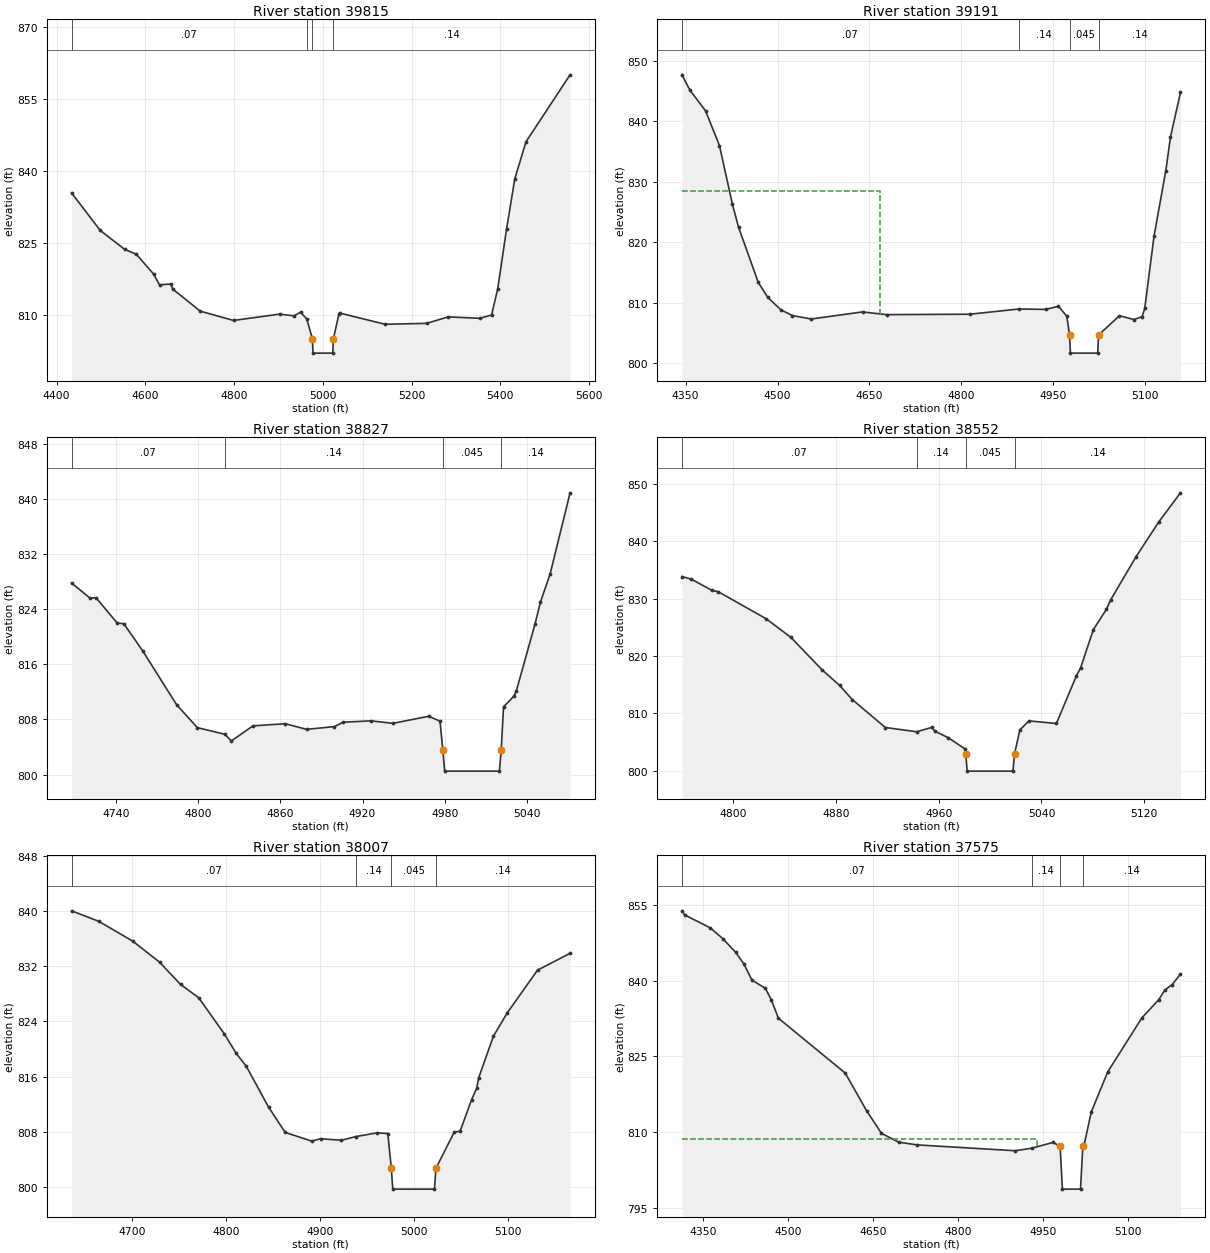
Type RM Length L Ch R = 1 ,39815   ,624,624,624
BEGIN DESCRIPTION:
North Deep Creek 105.0
END DESCRIPTION:
XS GIS Cut Line= 4
      1516413.17       874188.02      1516197.36        874114.8
      1515596.16       873737.12      1515461.25       873609.92
#Sta/Elev= 30
  4433.7  835.45  4498.2  827.65    4553  823.74  4579.8  822.69  4618.7  818.56
  4631.8  816.34  4657.3  816.52  4661.6  815.47  4723.7  810.88  4798.7  808.95
  4902.7  810.27  4934.6   809.9  4949.6  810.66  4963.5  809.29  4976.3  805.16
  4977.8  802.16  5022.2  802.16  5023.7  805.16  5036.2  810.29  5038.9  810.46
  5139.9  808.16    5234  808.34  5282.1  809.69  5353.6   809.4  5380.1  810.08
  5393.9  815.48  5413.8  827.89  5432.5   838.4  5457.7  846.08    5557  859.98
#Mann= 4 ,-1 , 0
  4433.7     .07       0  4963.5     .14       0  4976.3    .045       0
  5023.7     .14       0
Bank Sta=4976.3,5023.7
Exp/Cntr=0.3,0.1

Type RM Length L Ch R = 1 ,39191   ,364,364,364
BEGIN DESCRIPTION:
North Deep Creek 104.0
END DESCRIPTION:
XS GIS Cut Line= 4
      1516767.75       873706.29      1516613.57       873679.31
      1516131.85       873351.74       1516085.6       873293.93
#Sta/Elev= 30
  4344.2  847.64  4356.9  845.14  4382.6  841.69  4405.3  835.94  4426.4  826.25
  4436.4  822.46  4468.5  813.34  4484.1  810.85  4505.6  808.79  4524.3  807.85
  4554.7  807.28  4638.7  808.45  4677.8     808  4813.7  808.07  4893.1  808.93
  4937.5  808.87  4958.3  809.38  4971.9  807.72  4976.3  804.64  4977.8  801.64
  5022.2  801.64  5023.7  804.64  5057.7  807.82  5081.5  807.19  5094.8  807.68
    5099  809.04  5114.2  821.01  5133.4  831.81    5141  837.39  5157.3  844.73
#Mann= 4 ,-1 , 0
  4344.2     .07       0  4893.1     .14       0  4976.3    .045       0
  5023.7     .14       0
#XS Ineff= 2 , 0
       0  4667.1  828.41               0
Permanent Ineff=
       F       F
Bank Sta=4976.3,5023.7
Exp/Cntr=0.3,0.1

Type RM Length L Ch R = 1 ,38827   ,275,275,275
BEGIN DESCRIPTION:
North Deep Creek 103.0
END DESCRIPTION:
XS GIS Cut Line= 3
      1516640.52       873355.56      1516447.86       873170.61
       1516436.3       873074.27
#Sta/Elev= 30
  4707.5  827.78  4720.9  825.61  4725.4  825.64  4740.7     822  4745.7  821.87
  4759.5  817.93  4784.3  810.11  4799.4  806.81  4819.4  805.86  4824.2  804.88
    4840  807.08  4863.7  807.38  4879.1  806.57  4899.4  806.96  4905.8   807.6
  4926.1   807.8  4942.1  807.44  4968.3  808.46  4976.6  807.76  4978.7  803.51
    4980  800.51    5020  800.51  5021.3  803.51    5023  809.83  5030.6  811.39
  5032.3   812.1    5046  821.84  5049.9  824.98    5057  829.07  5071.6  840.86
#Mann= 4 ,-1 , 0
  4707.5     .07       0  4819.4     .14       0  4978.7    .045       0
  5021.3     .14       0
Bank Sta=4978.7,5021.3
Exp/Cntr=0.3,0.1

Type RM Length L Ch R = 1 ,38552   ,545,545,545
BEGIN DESCRIPTION:
North Deep Creek 102.0
END DESCRIPTION:
XS GIS Cut Line= 4
      1516786.98       873359.41      1516725.34       873232.27
      1516702.21        873112.8      1516632.87       873008.78
#Sta/Elev= 30
  4760.2  833.84  4767.5   833.4  4783.4  831.45  4788.5   831.2  4825.7   826.5
    4845  823.24  4869.4  817.56  4882.8   814.9  4892.7  812.42  4918.5  807.55
  4942.8  806.81  4954.6  807.56    4957   806.9  4967.4  805.78  4980.2  803.86
    4981  802.95  4982.2  799.95  5017.8  799.95    5019  802.95  5023.2  807.13
  5030.2   808.7  5051.6  808.25  5067.1  816.52  5070.5  817.98  5080.4  824.62
  5090.6  828.17  5093.8  829.78  5113.7  837.34  5131.5  843.44  5148.2  848.44
#Mann= 4 ,-1 , 0
  4760.2     .07       0  4942.8     .14       0    4981    .045       0
    5019     .14       0
Bank Sta=4981,5019
Exp/Cntr=0.3,0.1

Type RM Length L Ch R = 1 ,38007   ,432,432,432
BEGIN DESCRIPTION:
North Deep Creek 101.0
END DESCRIPTION:
XS GIS Cut Line= 4
      1517141.56       873386.39      1517222.48       873159.05
      1517222.48       872987.55      1517264.86       872877.76
#Sta/Elev= 30
    4636  840.01  4665.1  838.48  4701.3   835.6  4729.6  832.58    4752  829.35
  4771.3  827.43  4798.5  822.21  4811.1   819.4    4822  817.49  4845.6  811.61
  4863.3  807.94  4891.6  806.68  4901.1  807.03    4923   806.8  4938.3  807.33
    4961  807.87  4972.5  807.78  4976.3  802.73  4977.8  799.73  5022.2  799.73
  5023.7  802.73  5043.2  807.97  5049.5  808.12  5061.7  812.68  5067.2  814.36
  5069.2  815.83    5085  821.89  5099.4  825.19  5131.9  831.43  5166.5  833.86
#Mann= 4 ,-1 , 0
    4636     .07       0  4938.3     .14       0  4976.3    .045       0
  5023.7     .14       0
Bank Sta=4976.3,5023.7
Exp/Cntr=0.5,0.3

Type RM Length L Ch R = 1 ,37575   ,123,123,123
BEGIN DESCRIPTION:
Myers Rd (NDC) us
END DESCRIPTION:
XS GIS Cut Line= 4
      1517453.62       873718.65      1517568.91       873372.78
      1517639.57       873108.76      1517632.13       872867.06
#Sta/Elev= 30
  4312.7  853.87  4317.1  853.08  4362.4   850.5  4384.6  848.37  4407.5  845.63
  4421.9  843.33  4436.2  840.12  4459.7  838.52  4470.1  836.28  4482.8  832.59
  4600.8   821.7  4638.3  814.27  4664.7  809.76    4695  808.01  4727.5  807.47
  4900.8  806.31  4930.5  806.83  4967.2  807.95    4980   807.2    4984   798.7
    5016   798.7    5020   807.2  5022.5  807.56    5035  814.01    5064  821.94
    5124  832.61  5153.8  836.23  5164.8  838.17  5177.7  839.25  5192.4  841.34
#Mann= 4 ,-1 , 0
  4312.7     .07       0  4930.5     .14       0    4980    .045       0
    5020     .14       0
#XS Ineff= 2 , 0
       0  4939.5  808.61  5060.5       0  816.59
Permanent Ineff=
       F       F
Bank Sta=4980,5020
Exp/Cntr=0.5,0.3

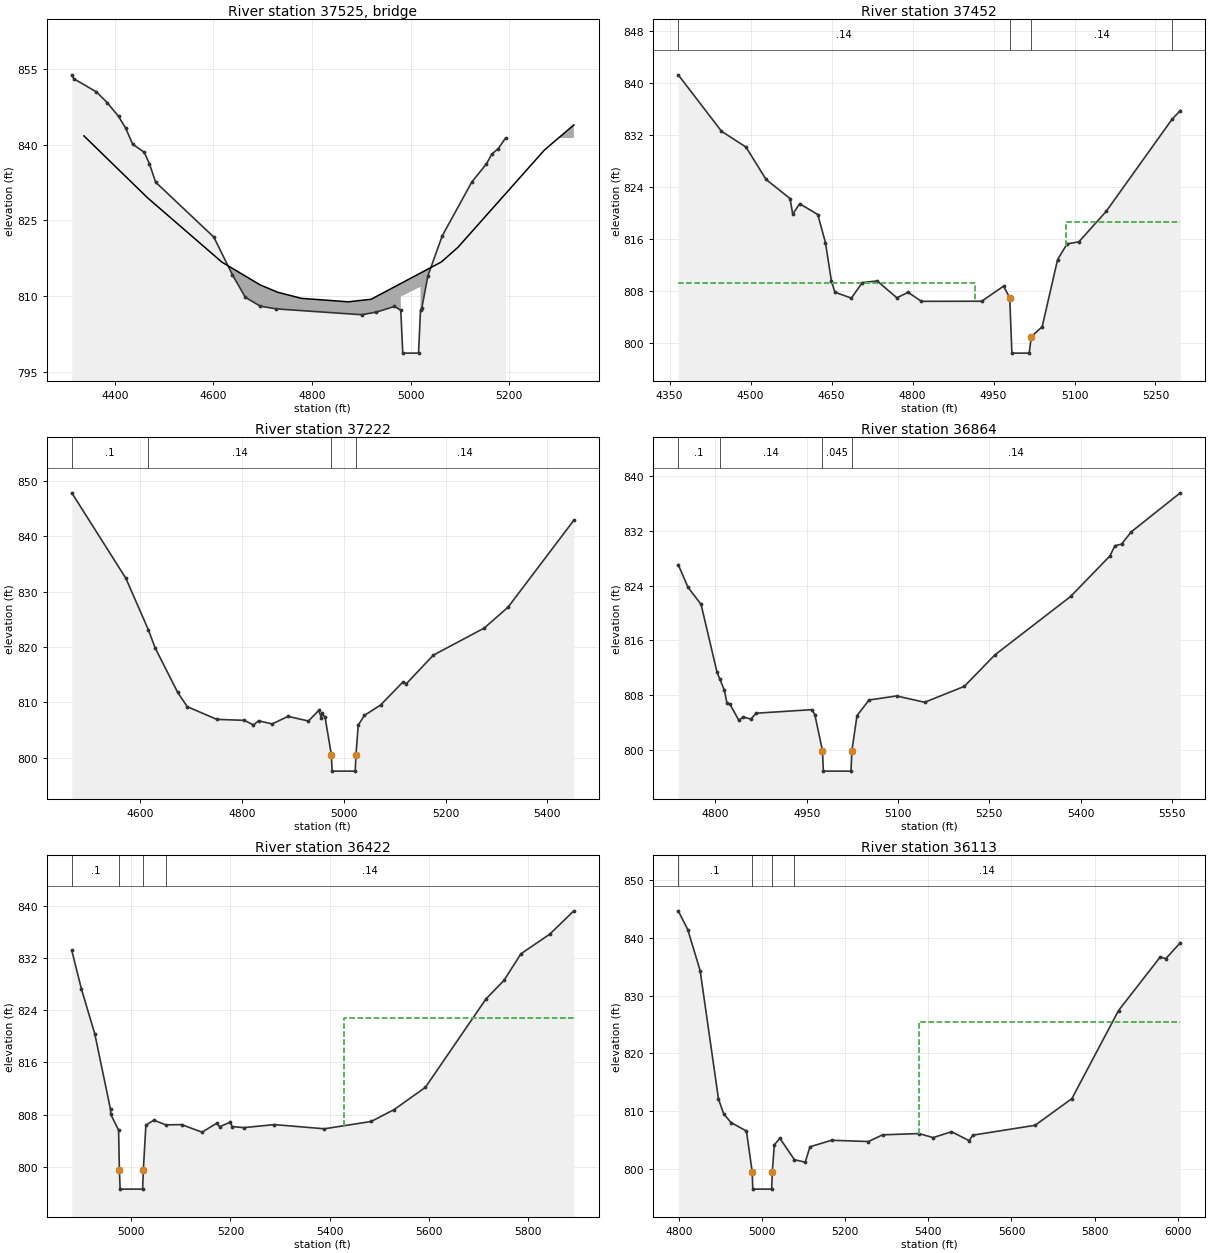
Type RM Length L Ch R = 3 ,37525   ,,,
BEGIN DESCRIPTION:
Myers Rd (NDC) tor
Structure ID: LDS_NDC_09
Approximate Survey Structure
END DESCRIPTION:
Bridge Culvert--1,0,-1,-1, 0
Deck Dist Width WeirC Skew NumUp NumDn MinLoCord MaxHiCord MaxSubmerge Is_Ogee
40.5,19,3,0, 16, 16, , , 0.95, 0, 1,1,,
  4337.3  4466.5  4617.2  4694.9    4730  4778.4  4873.6  4919.8    4980    4980
    5020    5020  5062.1  5095.7  5271.6    5331
  841.77  829.48  816.74  812.22  810.78  809.56  808.87  809.38   812.5   812.5
  814.58  814.58  816.76  819.65  838.99  843.94
   778.7   778.7   778.7   778.7   778.7   778.7   778.7   778.7   778.7   809.9
  811.86   778.7   778.7   778.7   778.7   778.7
  4337.3  4466.5  4617.2  4694.9    4730  4778.4  4873.6  4919.8    4980    4980
    5020    5020  5062.1  5095.7  5271.6    5331
  841.77  829.48  816.74  812.22  810.78  809.56  808.87  809.38   812.5   812.5
  814.58  814.58  816.76  819.65  838.99  843.94
   778.7   778.7   778.7   778.7   778.7   778.7   778.7   778.7   778.7   809.9
  811.86   778.7   778.7   778.7   778.7   778.7
BR Coef= 1 , 1 , 0 ,1.25, 0 ,,,0.8,-1,2,0,
WSPro=,,,, 1 ,,,, 0 ,,,, 0 ,,,,-1 ,-1 ,-1 , 0 , 0 , 0 , 0 , 0
BC Design=,, 0 ,, 0 ,,,,,,
BC HTab HWMax=853.87

Type RM Length L Ch R = 1 ,37452   ,230,230,230
BEGIN DESCRIPTION:
Myers Rd (NDC) ds
END DESCRIPTION:
XS GIS Cut Line= 5
      1517639.56       873714.93      1517702.78       873439.71
      1517732.53       873153.38      1517758.56       873038.11
      1517758.56       872796.44
#Sta/Elev= 30
  4365.9  841.28    4446   832.6  4491.4  830.16  4528.6  825.18    4573  822.24
    4578  819.83  4590.8  821.45  4624.4  819.78  4638.7  815.43  4649.6  809.58
  4656.1  807.83  4686.6  806.92  4706.8   809.3  4734.4  809.56    4771  806.96
  4791.6  807.81  4816.4  806.42  4928.1  806.44  4968.6  808.76    4980  806.95
    4984  798.45    5016  798.45    5020  800.98  5040.1  802.52  5068.6  812.82
  5086.2  815.27    5108  815.57  5158.7  820.27  5280.4  834.41    5296  835.79
#Mann= 4 ,-1 , 0
  4365.9     .14       0    4980    .045       0    5020     .14       0
  5280.4     .14       0
#XS Ineff= 2 , 0
       0  4916.5  809.28  5083.5       0   818.7
Permanent Ineff=
       F       F
Bank Sta=4980,5020
Exp/Cntr=0.5,0.3

Type RM Length L Ch R = 1 ,37222   ,358,358,358
BEGIN DESCRIPTION:
North Deep Creek 100.0
END DESCRIPTION:
XS GIS Cut Line= 6
      1518212.24       873562.44      1518059.76       873409.96
       1517966.8        873097.6      1517903.59       872844.74
      1517799.47       872770.37        1517766.       872725.75
#Sta/Elev= 30
  4466.1  847.85  4572.4   832.4  4616.4  823.14  4629.8  819.85  4674.2  811.79
  4692.9  809.23  4750.9  806.94  4805.2  806.76  4822.7  805.92  4832.8  806.68
  4859.7  806.12  4890.9  807.48  4930.8  806.64  4950.9  808.54  4956.4  807.26
  4957.6     808  4963.5  807.32  4975.8  800.59  4977.3  797.59  5022.7  797.59
  5024.2  800.59  5028.6  805.89  5040.7  807.65  5072.5  809.53  5115.9  813.64
  5123.3   813.4  5176.2  818.54  5276.1  823.43  5322.8   827.2    5452   842.9
#Mann= 4 ,-1 , 0
  4466.1      .1       0  4616.4     .14       0  4975.8    .045       0
  5024.2     .14       0
Bank Sta=4975.8,5024.2
Exp/Cntr=0.3,0.1

Type RM Length L Ch R = 1 ,36864   ,442,442,442
BEGIN DESCRIPTION:
North Deep Creek 99.0
END DESCRIPTION:
XS GIS Cut Line= 4
       1518405.6        873231.5      1518271.72       872930.27
      1518108.11       872829.87      1517818.03       872740.61
#Sta/Elev= 30
  4738.8  827.05  4754.8  823.75  4776.3  821.25  4802.5  811.35  4807.3   810.3
  4814.8  808.67  4818.9  806.81  4823.5   806.7  4838.5   804.3  4845.5  804.81
  4858.1  804.49  4866.8  805.35  4958.6  805.87  4963.3  805.13  4975.8  799.89
  4977.3  796.89  5022.7  796.89  5024.2  799.89  5032.6     805  5052.4  807.28
  5097.6  807.87  5143.8  806.95  5208.9  809.27  5259.2  813.87  5383.6   822.4
  5448.2  828.32  5456.4  829.82  5467.3  830.04  5483.3  831.84  5563.9  837.54
#Mann= 4 ,-1 , 0
  4738.8      .1       0  4807.3     .14       0  4975.8    .045       0
  5024.2     .14       0
Bank Sta=4975.8,5024.2
Exp/Cntr=0.3,0.1

Type RM Length L Ch R = 1 ,36422   ,309,309,309
BEGIN DESCRIPTION:
North Deep Creek 98.0
END DESCRIPTION:
XS GIS Cut Line= 5
      1518721.66       873093.86      1518636.14        872956.3
      1518468.81       872833.59      1518122.98       872766.65
      1517836.69       872710.88
#Sta/Elev= 30
  4879.7  833.15  4899.3  827.21  4926.2  820.37  4957.9  808.83  4958.4  808.06
  4974.2  805.66  4975.8  799.63  4977.3  796.63  5022.7  796.63  5024.2  799.63
  5029.3  806.42  5045.5  807.18  5069.4  806.46  5101.5   806.5  5142.6  805.34
  5172.1   806.7  5178.1  806.17    5199  806.85  5203.8   806.2  5227.2  806.04
  5288.7   806.5  5389.6  805.86  5484.1  806.98  5530.2  808.79  5593.5   812.2
  5715.7  825.72    5752  828.55  5786.3  832.63  5844.5  835.63  5893.1   839.2
#Mann= 4 ,-1 , 0
  4879.7      .1       0  4975.8    .045       0  5024.2      .1       0
  5069.4     .14       0
#XS Ineff= 2 , 0
       0                  5429.1       0  822.88
Permanent Ineff=
       F       F
Bank Sta=4975.8,5024.2
Exp/Cntr=0.3,0.1

Type RM Length L Ch R = 1 ,36113   ,337,337,337
BEGIN DESCRIPTION:
North Deep Creek 97.0
END DESCRIPTION:
XS GIS Cut Line= 4
       1519067.5       872803.84      1518796.04       872759.21
      1518163.88       872733.18       1517866.4       872688.56
#Sta/Elev= 30
  4797.8  844.66  4820.7  841.41  4850.5  834.32  4894.7  812.08  4907.3   809.5
  4924.9     808    4962  806.54  4975.8  799.48  4977.3  796.48  5022.7  796.48
  5024.2  799.48  5029.1  804.16  5042.6  805.27  5077.5  801.57  5103.5  801.15
  5114.9  803.81  5166.8  804.94  5255.7  804.72  5289.7  805.88  5377.2   806.1
  5411.3   805.4  5455.6  806.42  5497.8  804.88  5507.2  805.83  5656.9  807.53
  5745.4  812.15  5857.7   827.4  5958.2  836.68  5971.3  836.37  6006.4  839.14
#Mann= 4 ,-1 , 0
  4797.8      .1       0  4975.8    .045       0  5024.2      .1       0
  5077.5     .14       0
#XS Ineff= 2 , 0
       0                  5377.6       0  825.37
Permanent Ineff=
       F       F
Bank Sta=4975.8,5024.2
Exp/Cntr=0.5,0.3

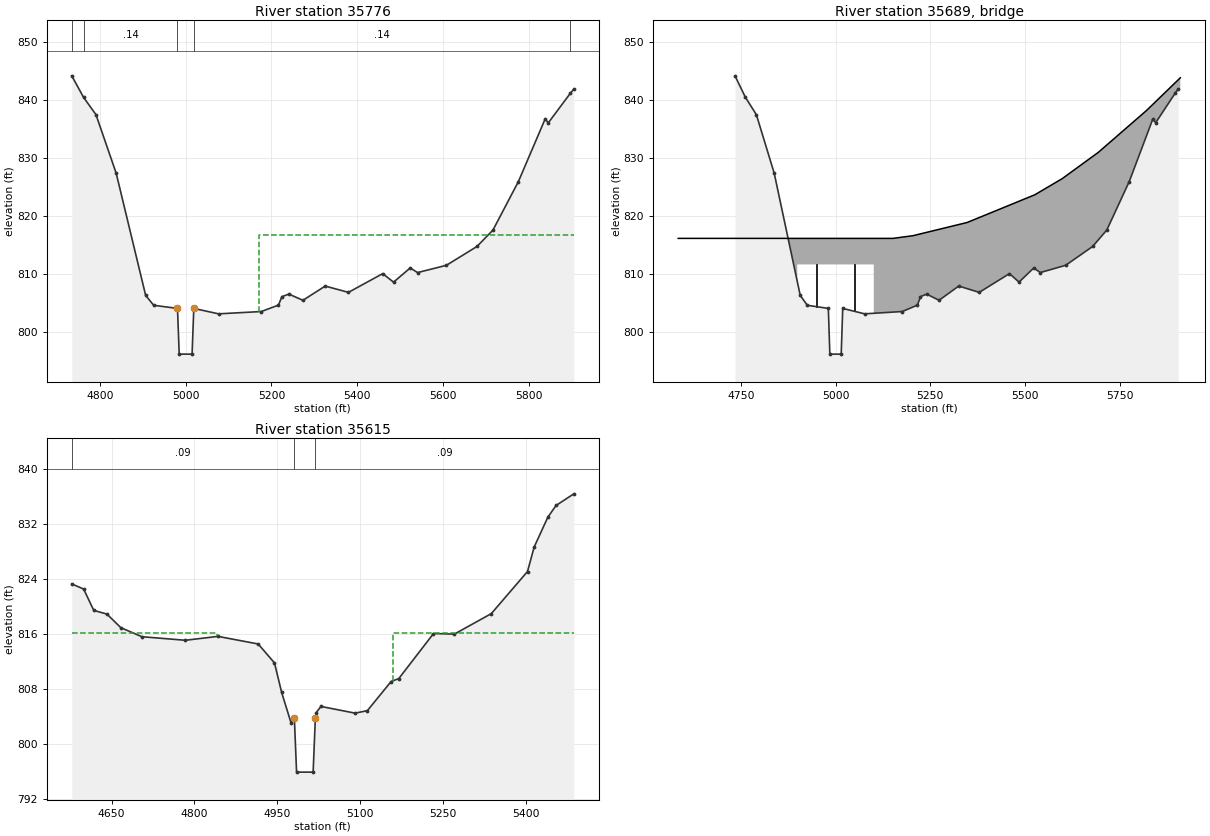
Type RM Length L Ch R = 1 ,35776   ,161,161,161
BEGIN DESCRIPTION:
Old US 421 (NDC) us
END DESCRIPTION:
XS GIS Cut Line= 6
      1519061.96       872513.79      1518911.32       872500.77
      1518760.71       872474.74      1518520.87       872513.79
      1518121.12       872569.57      1517901.71       872565.85
#Sta/Elev= 30
  4734.6  844.19    4762  840.48    4791  837.48  4838.1  827.36  4906.8  806.25
  4925.5  804.54    4981     804    4985   796.1    5015   796.1    5019     804
  5076.8  803.06  5176.3  803.46  5216.3  804.57  5224.3  806.03  5240.7  806.47
  5273.3   805.4  5325.3  807.86  5379.4  806.77  5459.2  810.01  5484.5  808.54
  5523.4  810.99  5540.5  810.19  5607.7  811.45  5678.9   814.7  5716.2  817.54
  5775.5  825.92  5837.7  836.72  5845.3  836.08  5896.9  841.21  5904.7  841.89
#Mann= 5 ,-1 , 0
  4734.6      .1       0    4762     .14       0    4981    .045       0
    5019     .14       0  5896.9     .14       0
#XS Ineff= 2 , 0
       0    4828   816.1    5172       0  816.66
Permanent Ineff=
       F       F
Bank Sta=4981,5019
Exp/Cntr=0.5,0.3

Type RM Length L Ch R = 3 ,35689   ,,,
BEGIN DESCRIPTION:
Old US 421 (NDC) tor
Structure ID: LDS_NDC_08
Approximate Survey Structure
END DESCRIPTION:
Bridge Culvert--1,0,-1,-1, 0
Deck Dist Width WeirC Skew NumUp NumDn MinLoCord MaxHiCord MaxSubmerge Is_Ogee
71,32,3,0, 14, 14, , , 0.95, 0, 1,1,,
  4584.7    4899    4899    5101    5101  5151.6  5204.8  5347.6  5423.7  5526.3
  5598.4  5693.9  5820.9  5910.3
   816.1   816.1   816.1   816.1   816.1   816.1  816.57  818.85  820.89  823.64
  826.42  830.97  838.19  843.85
   776.1   776.1   811.6   811.6   776.1   776.1   776.1   776.1   776.1   776.1
   776.1   776.1   776.1   776.1
  4584.7    4899    4899    5101    5101  5151.6  5204.8  5347.6  5423.7  5526.3
  5598.4  5693.9  5820.9  5910.3
   816.1   816.1   816.1   816.1   816.1   816.1  816.57  818.85  820.89  823.64
  826.42  830.97  838.19  843.85
   776.1   776.1   811.6   811.6   776.1   776.1   776.1   776.1   776.1   776.1
   776.1   776.1   776.1   776.1
Pier Skew, UpSta & Num, DnSta & Num=  ,4949.5, 2 ,4949.5, 2 , 0 , 0 , 0 ,0,0
       3       3
  804.14   811.6
       3       3
  810.38   811.6
Pier Skew, UpSta & Num, DnSta & Num=  ,5050.5, 2 ,5050.5, 2 , 0 , 0 , 0 ,0,0
       3       3
   803.3   811.6
       3       3
  805.11   811.6
Abutment Skew #Up #Dn= , 2 , 2
    4899  4908.3
   811.6  806.05
    4899  4908.3
   811.6  814.56
Abutment Skew #Up #Dn= , 2 , 2
  5091.8    5101
  803.46   811.6
  5091.8    5101
  804.46   811.6
BR Coef= 1 , 1 , 0 ,1.25, 0 ,,,0.8,0,2,0,
WSPro=,,,, 1 ,,,, 0 ,,,, 0 ,,,,-1 ,-1 ,-1 , 0 , 0 , 0 , 0 , 0
BC Design=,, 0 ,, 0 ,,,,,,
BC HTab HWMax=844.19

Type RM Length L Ch R = 1 ,35615   ,206,206,206
BEGIN DESCRIPTION:
Old US 421 (NDC) ds
END DESCRIPTION:
XS GIS Cut Line= 6
      1519147.42       872266.51      1518799.76       872327.86
      1518543.18       872365.05      1518470.67       872363.19
      1518359.11       872327.86      1518292.17       872244.19
#Sta/Elev= 30
    4578   823.3  4599.5  822.55  4617.8  819.44  4641.7   818.9  4666.8  816.92
  4704.9   815.6  4783.8  815.08  4842.6  815.65  4915.5  814.54    4945  811.78
    4958  807.47  4975.1  803.01    4981  803.75    4985  795.85    5015  795.85
    5019  803.75  5020.6  804.54  5029.1  805.43  5091.1  804.45  5113.2  804.82
  5156.1  809.06  5170.1   809.5  5232.9  816.06  5270.7  815.98  5337.6  818.97
  5403.1  825.11  5415.2  828.69  5439.9  833.03  5454.8  834.74    5487  836.44
#Mann= 3 ,-1 , 0
    4578     .09       0    4981    .045       0    5019     .09       0
#XS Ineff= 2 , 0
       0    4841   816.1    5159       0  816.21
Permanent Ineff=
       F       F
Bank Sta=4981,5019
Exp/Cntr=0.5,0.3