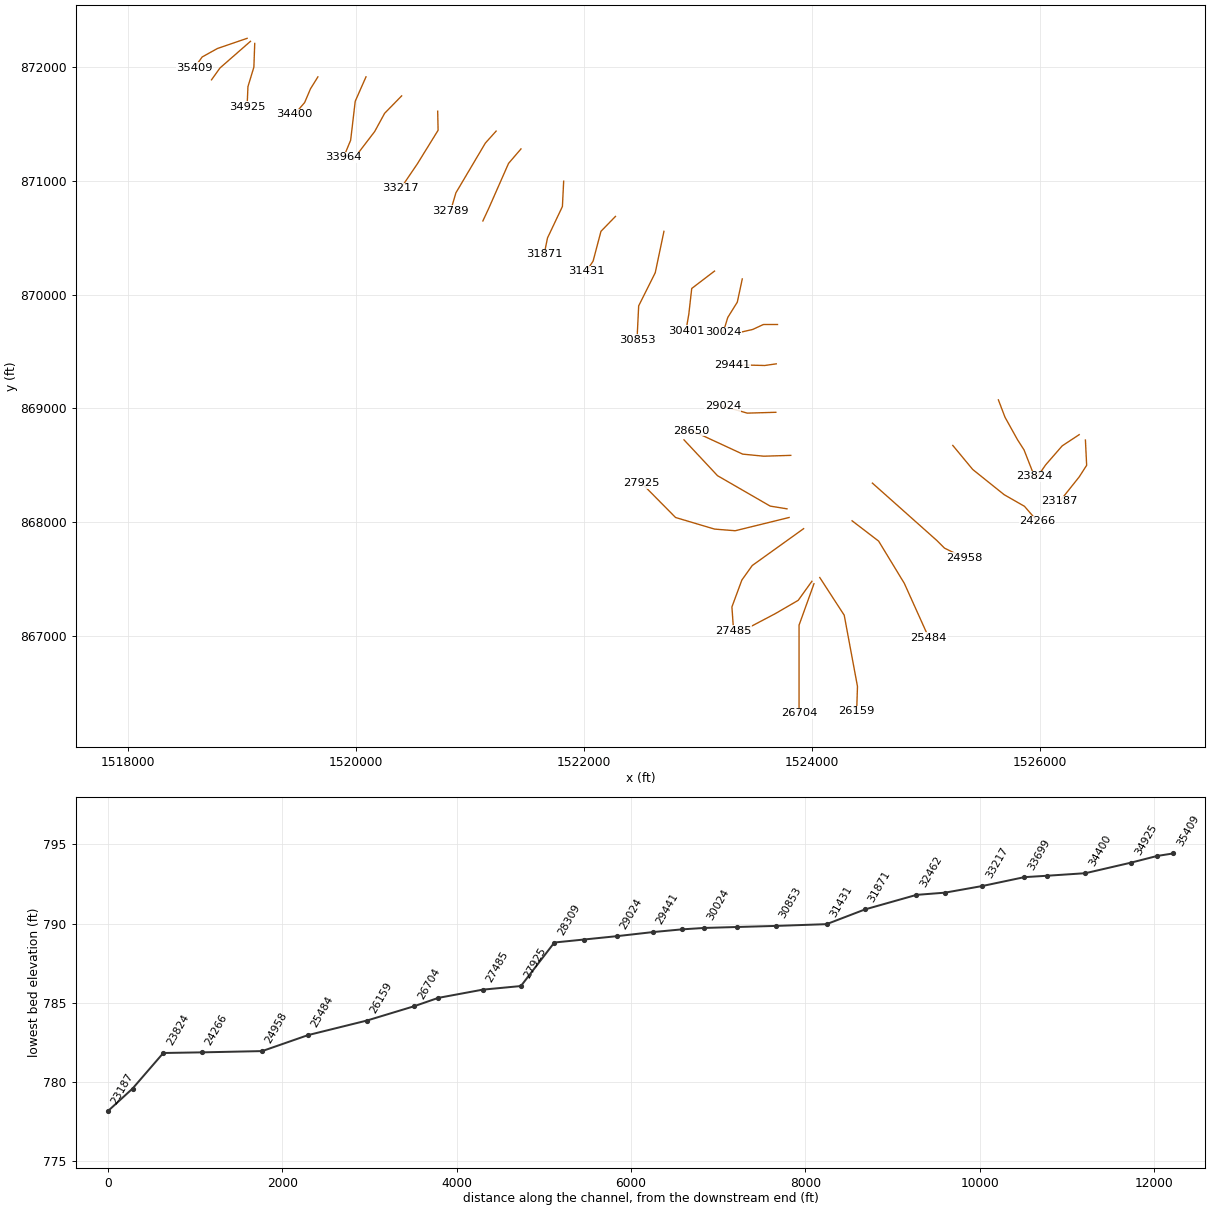
HEC-RAS study North Deep Creek.prj: North Deep Creek Limited Detail Study

--- North Deep Creek.g01 (geometry) --- (continued)

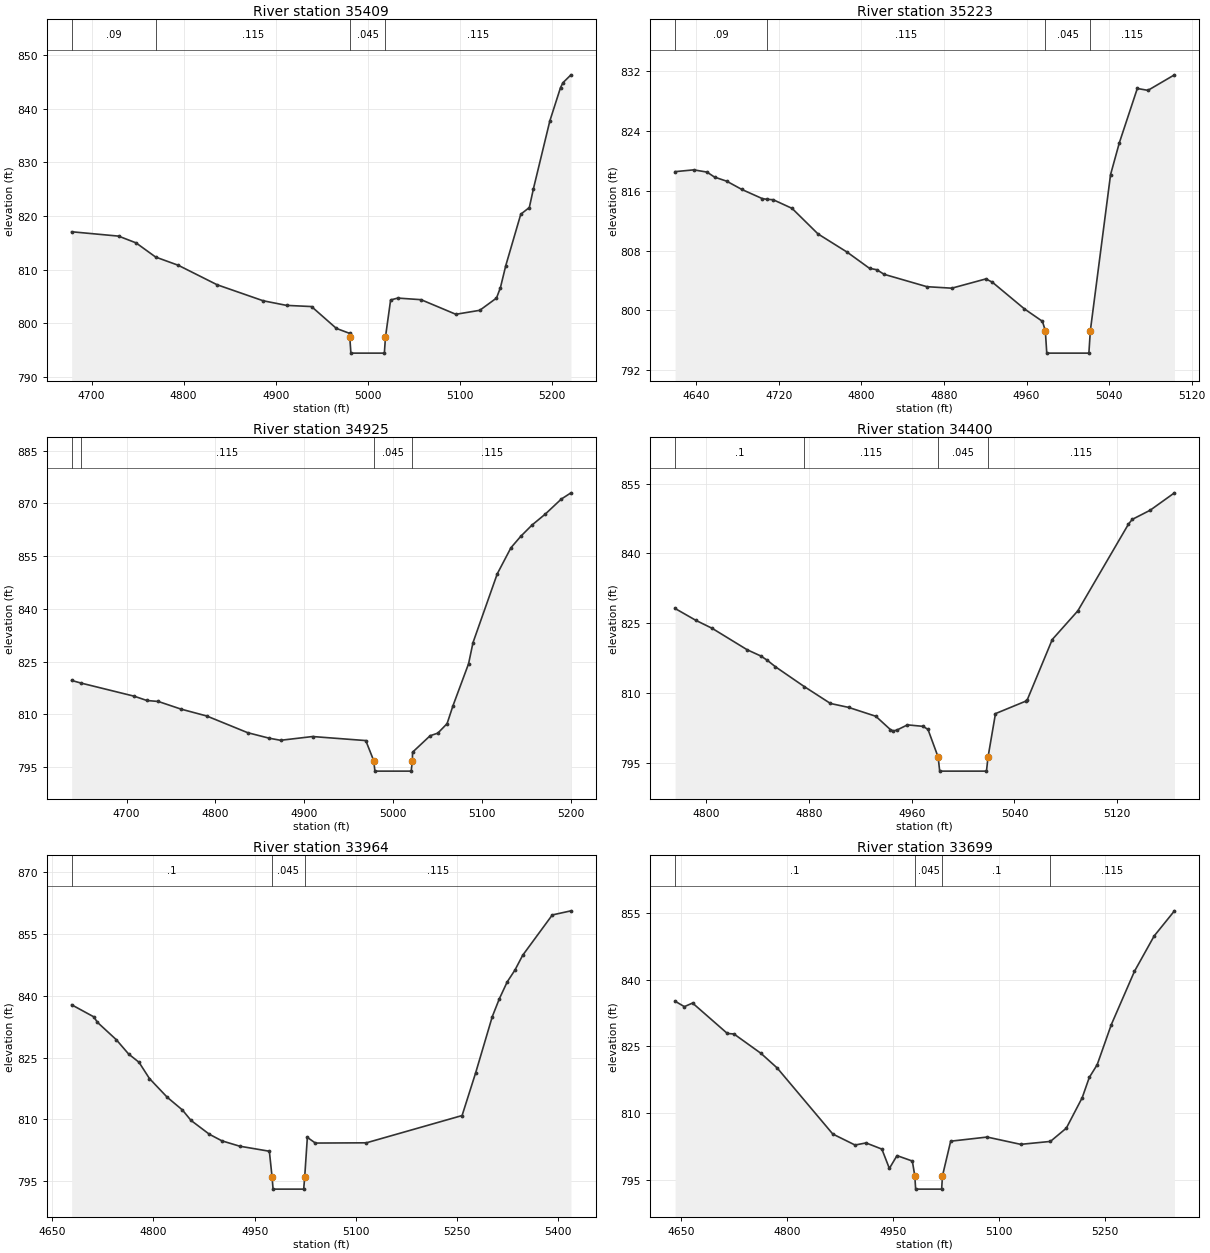
Type RM Length L Ch R = 1 ,35409   ,186,186,186
BEGIN DESCRIPTION:
North Deep Creek 95.0
END DESCRIPTION:
XS GIS Cut Line= 4
       1519041.5       872249.78      1518781.17       872160.53
       1518647.3       872086.15      1518580.37        871993.2
#Sta/Elev= 30
  4678.2  817.05  4729.2  816.24  4748.2  814.98  4769.6  812.33  4794.2   810.8
  4836.4  807.17  4886.4  804.19  4911.8  803.33    4939  803.11    4966  799.04
  4980.3  798.12  4980.6  797.43  4981.8  794.43  5018.2  794.43  5019.4  797.43
    5025  804.34  5032.8  804.69  5058.1  804.39  5095.9  801.67  5121.9  802.41
  5140.1  804.69  5144.4  806.65  5150.2  810.75  5166.5  820.32  5175.8  821.57
  5180.3   825.1  5198.1  837.71  5209.7  843.91  5212.4  844.84  5221.1   846.3
#Mann= 4 ,-1 , 0
  4678.2     .09       0  4769.6    .115       0  4980.6    .045       0
  5019.4    .115       0
Bank Sta=4980.6,5019.4
Exp/Cntr=0.3,0.1

Type RM Length L Ch R = 1 ,35223   ,298,298,298
BEGIN DESCRIPTION:
North Deep Creek 94.0
END DESCRIPTION:
XS GIS Cut Line= 3
      1519071.21       872223.74      1518803.48       871989.47
      1518729.11       871885.36
#Sta/Elev= 30
  4619.6  818.58  4637.7  818.82  4650.5  818.52  4657.8  817.85  4669.6   817.3
  4684.3  816.19  4704.2  814.96    4709  814.87  4714.6  814.82  4732.9  813.66
    4758  810.24  4786.3  807.79  4807.9  805.63    4815  805.44    4822  804.83
  4863.5  803.17  4887.6  802.97  4920.6  804.21  4926.9  803.77    4958  800.19
  4975.4  798.53  4978.2  797.27  4979.6  794.27  5020.4  794.27  5021.8  797.27
  5041.4  818.19  5049.9  822.45  5067.3  829.72  5077.6  829.47  5103.3  831.55
#Mann= 4 ,-1 , 0
  4619.6     .09       0    4709    .115       0  4978.2    .045       0
  5021.8    .115       0
Bank Sta=4978.2,5021.8
Exp/Cntr=0.3,0.1

Type RM Length L Ch R = 1 ,34925   ,525,525,525
BEGIN DESCRIPTION:
North Deep Creek 93.0
END DESCRIPTION:
XS GIS Cut Line= 4
       1519108.4       872205.11      1519100.96       871996.91
       1519048.9       871825.86      1519041.46       871651.05
#Sta/Elev= 30
  4638.2  819.64  4649.2  818.87  4708.5  815.17  4722.9  813.94  4735.8  813.66
  4761.2   811.5  4790.3  809.53  4836.4  804.78  4860.7  803.21  4873.4  802.62
  4909.4  803.69  4969.3  802.54  4978.2  796.85  4979.6  793.85  5020.4  793.85
  5021.8  796.85  5021.9  799.22  5041.7  803.91  5050.4  804.66  5060.8  807.35
  5067.5  812.48    5085  824.39    5090  830.41  5117.3  849.97  5132.7  857.39
  5143.8  860.65  5156.4  863.84  5171.4  866.97  5189.4  871.24  5200.3  873.01
#Mann= 4 ,-1 , 0
  4638.2     .09       0  4649.2    .115       0  4978.2    .045       0
  5021.8    .115       0
Bank Sta=4978.2,5021.8
Exp/Cntr=0.3,0.1

Type RM Length L Ch R = 1 ,34400   ,436,436,436
BEGIN DESCRIPTION:
North Deep Creek 92.0
END DESCRIPTION:
XS GIS Cut Line= 4
      1519662.85       871911.57       1519597.4       871806.12
      1519546.49       871686.12       1519459.2       871584.28
#Sta/Elev= 30
  4775.9  828.16  4792.2  825.59  4804.7   823.9    4832  819.28  4842.5  817.96
  4847.7  817.01  4853.9  815.64  4876.5  811.35  4896.8  807.73  4910.9  806.89
  4932.1  804.98  4943.4  802.12  4945.8  801.82  4948.7  802.04  4956.7  803.13
  4968.9  802.81  4972.7  802.14  4980.6  796.18  4981.8  793.18  5018.2  793.18
  5019.4  796.18  5025.2  805.55  5049.3  808.29  5049.9  808.49  5069.4  821.49
  5089.3  827.66  5128.7  846.31  5131.6  847.32  5145.6   849.3  5164.5  853.04
#Mann= 4 ,-1 , 0
  4775.9      .1       0  4876.5    .115       0  4980.6    .045       0
  5019.4    .115       0
Bank Sta=4980.6,5019.4
Exp/Cntr=0.3,0.1

Type RM Length L Ch R = 1 ,33964   ,265,265,265
BEGIN DESCRIPTION:
North Deep Creek 91.0
END DESCRIPTION:
XS GIS Cut Line= 4
      1520084.69        871911.6      1519990.13       871697.03
      1519950.13       871355.21      1519888.32       871206.15
#Sta/Elev= 30
  4678.8  837.84  4711.6  834.91  4717.1  833.56  4745.1  829.33  4763.3  825.86
  4778.6  823.87  4794.1  819.91  4820.5  815.35    4843  812.26  4855.6  809.74
  4882.9  806.36  4901.5  804.76  4927.8  803.46  4971.8  802.23  4975.8  796.02
  4977.3  793.02  5022.7  793.02  5024.2  796.02  5028.1   805.6    5040  804.22
  5115.6  804.28  5257.4  810.91  5277.4  821.23  5302.2  834.98  5312.6  839.29
  5324.3  843.41  5335.7  846.27  5347.2  849.87  5391.1  859.68  5418.8  860.68
#Mann= 3 ,-1 , 0
  4678.8      .1       0  4975.8    .045       0  5024.2    .115       0
Bank Sta=4975.8,5024.2
Exp/Cntr=0.3,0.1

Type RM Length L Ch R = 1 ,33699   ,482,482,482
BEGIN DESCRIPTION:
North Deep Creek 90.0
END DESCRIPTION:
XS GIS Cut Line= 4
      1520397.37       871744.27      1520248.31       871591.58
      1520161.04       871431.57      1519971.97       871184.33
#Sta/Elev= 30
  4641.1  835.15  4654.2  833.93  4665.8  834.74  4715.1   827.9  4724.4  827.79
  4762.7  823.43  4785.6  820.15  4864.3  805.31  4895.8  802.84  4911.4  803.31
  4933.8  801.92  4944.4  797.58  4955.2  800.46  4976.9  799.24  4980.4  795.93
  4981.6  792.93  5018.4  792.93  5019.6  795.93  5031.2   803.7  5082.8  804.63
  5130.3  802.99  5172.4  803.65  5194.9  806.63  5217.4  813.48  5227.4  818.02
  5238.6  820.89  5258.6   829.9  5291.4  841.88  5319.2   849.8    5348  855.46
#Mann= 4 ,-1 , 0
  4641.1      .1       0  4980.4    .045       0  5019.6      .1       0
  5172.4    .115       0
Bank Sta=4980.4,5019.6
Exp/Cntr=0.3,0.1

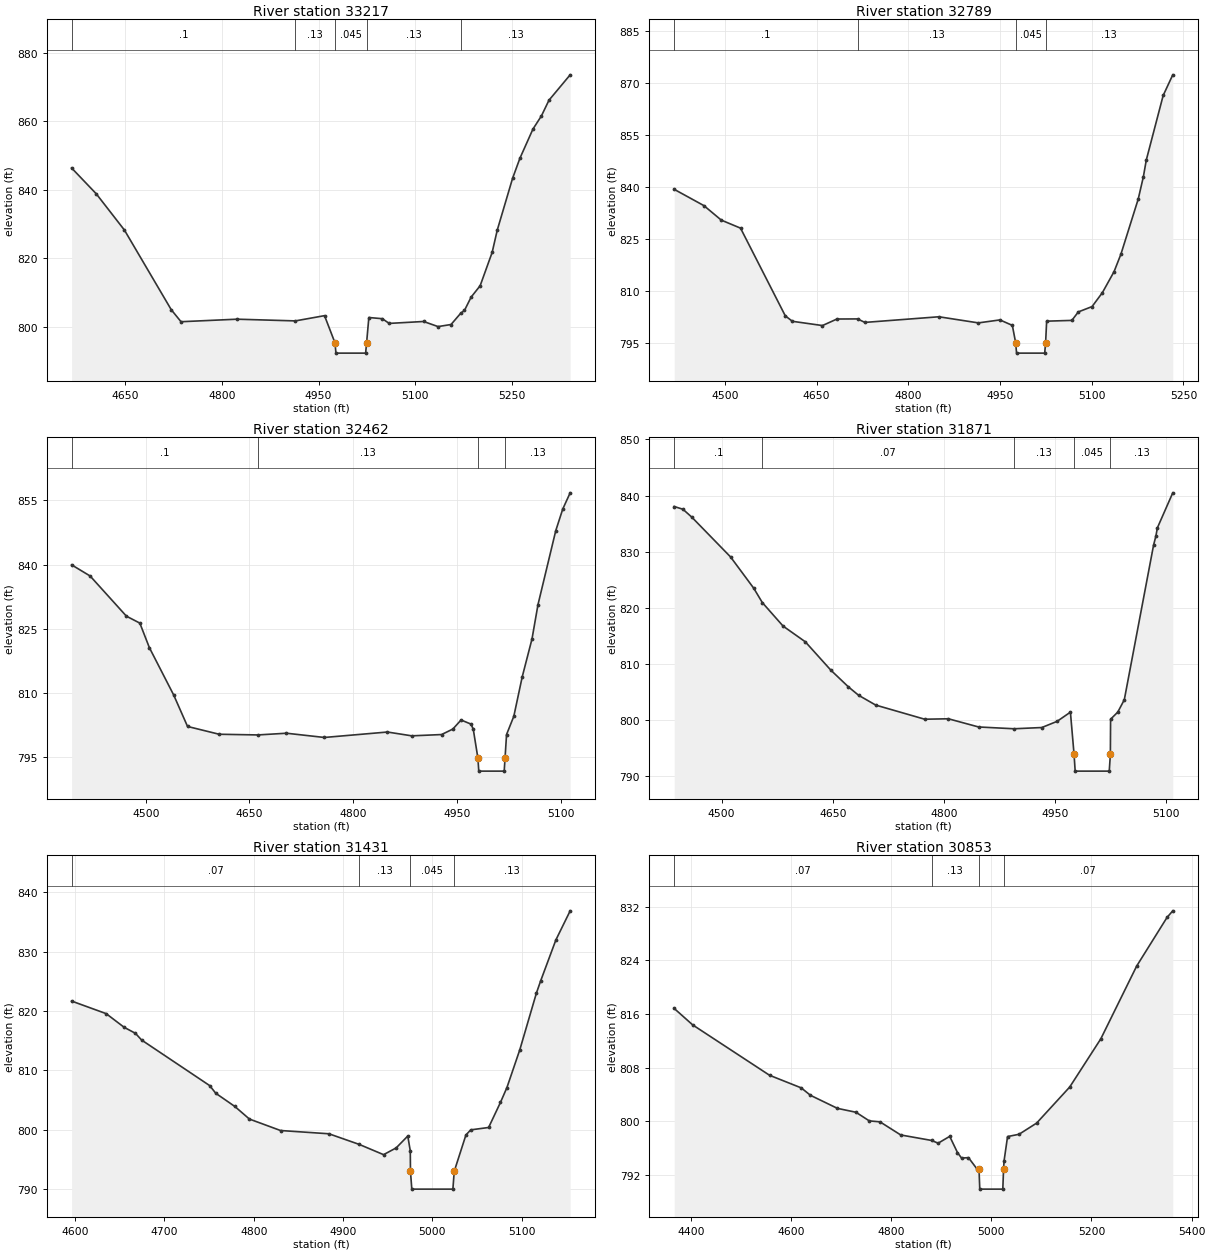
Type RM Length L Ch R = 1 ,33217   ,428,428,428
BEGIN DESCRIPTION:
North Deep Creek 89.0
END DESCRIPTION:
XS GIS Cut Line= 4
      1520713.77        871609.8      1520717.41       871442.48
      1520535.59       871147.94      1520390.13       870933.39
#Sta/Elev= 30
  4567.3  846.38  4605.5  838.85  4649.2  828.26  4721.8  805.02  4736.9  801.53
  4823.7  802.27  4914.1  801.77  4959.3   803.3  4975.5  795.37    4977  792.37
    5023  792.37  5024.5  795.37    5028  802.76  5048.9  802.41  5059.5  801.04
  5112.8   801.6  5135.3  800.11  5155.4  800.72  5170.4  804.01  5176.2  804.83
  5186.5  808.71  5200.5  812.03  5219.1  821.75    5227  828.25  5250.7  843.33
  5262.1   849.2  5282.3  857.72  5295.5  861.58  5307.1  866.13    5340  873.55
#Mann= 5 ,-1 , 0
  4567.3      .1       0  4914.1     .13       0  4975.5    .045       0
  5024.5     .13       0  5170.4     .13       0
Bank Sta=4975.5,5024.5
Exp/Cntr=0.3,0.1

Type RM Length L Ch R = 1 ,32789   ,327,327,327
BEGIN DESCRIPTION:
North Deep Creek 88.0
END DESCRIPTION:
XS GIS Cut Line= 4
      1521226.49       871435.19      1521131.95       871329.76
      1520873.77       870893.39      1520826.49       870733.36
#Sta/Elev= 30
    4417   839.3  4465.6  834.59    4494   830.4  4525.5  828.08  4598.7  802.73
  4610.3  801.15  4659.5  799.92  4683.2  801.81  4716.9  801.84  4728.9  800.83
    4850  802.46  4914.5  800.69  4949.8  801.55  4970.1  799.97  4975.5  794.95
    4977  791.95    5023  791.95  5024.5  794.95  5026.2  801.19  5067.4  801.41
    5078  803.86  5100.5  805.41  5117.4  809.44  5136.5  815.52  5147.7  820.56
    5176  836.49  5184.4  842.92  5189.2  847.78  5216.8  866.43  5232.5   872.4
#Mann= 4 ,-1 , 0
    4417      .1       0  4716.9     .13       0  4975.5    .045       0
  5024.5     .13       0
Bank Sta=4975.5,5024.5
Exp/Cntr=0.3,0.1

Type RM Length L Ch R = 1 ,32462   ,591,591,591
BEGIN DESCRIPTION:
North Deep Creek 87.0
END DESCRIPTION:
XS GIS Cut Line= 4
      1521444.65       871278.81      1521335.59       871151.57
      1521161.05       870755.21      1521110.12       870646.08
#Sta/Elev= 30
  4392.7  839.98  4419.5  837.37    4472  827.99  4491.4  826.37  4505.2  820.64
  4540.4  809.57  4560.4  802.24  4606.1  800.42  4662.1  800.26  4703.5  800.66
  4758.3  799.67  4849.5  800.94  4884.7  800.05  4927.8  800.35  4944.1  801.63
    4956  803.75  4970.2   802.8  4973.6  801.65  4980.4  794.81  4981.6  791.81
  5018.4  791.81  5019.6  794.81  5021.8  800.36  5032.3  804.61  5044.4  813.78
  5058.6  822.67  5067.3  830.71    5093  847.97  5103.1  853.01  5113.8  856.79
#Mann= 4 ,-1 , 0
  4392.7      .1       0  4662.1     .13       0  4980.4    .045       0
  5019.6     .13       0
Bank Sta=4980.4,5019.6
Exp/Cntr=0.3,0.1

Type RM Length L Ch R = 1 ,31871   ,440,440,440
BEGIN DESCRIPTION:
North Deep Creek 86.0
END DESCRIPTION:
XS GIS Cut Line= 4
      1521819.23       870995.23      1521808.32       870773.39
      1521677.41       870497.02      1521648.32       870355.19
#Sta/Elev= 30
    4436  838.05  4447.8  837.56  4459.7  836.16    4512  829.07  4543.4  823.47
  4554.9  820.93  4582.9  816.74  4612.9  813.94  4647.3  808.89  4671.1   805.9
  4684.8  804.41  4707.9  802.66    4774  800.14  4805.9  800.22  4846.7  798.76
  4894.5  798.44    4932  798.66  4952.6  799.76  4970.6   801.4  4975.5  793.89
    4977  790.89    5023  790.89  5024.5  793.89  5024.8  800.14  5034.5  801.41
  5043.3  803.61  5082.8  831.17    5086  832.83  5087.9  834.24  5108.7  840.49
#Mann= 5 ,-1 , 0
    4436      .1       0  4554.9     .07       0  4894.5     .13       0
  4975.5    .045       0  5024.5     .13       0
Bank Sta=4975.5,5024.5
Exp/Cntr=0.3,0.1

Type RM Length L Ch R = 1 ,31431   ,578,578,578
BEGIN DESCRIPTION:
North Deep Creek 85.0
END DESCRIPTION:
XS GIS Cut Line= 4
      1522273.78       870686.11      1522146.51       870555.21
      1522077.41       870293.39      1522019.26       870206.15
#Sta/Elev= 30
  4596.1  821.66  4634.8  819.54  4654.9  817.24  4667.6  816.22  4674.5  815.09
  4750.7  807.41  4757.5  806.12  4778.9  803.89  4795.2  801.77    4830  799.84
  4884.2  799.29  4918.1   797.5  4945.4  795.77  4959.5  796.91  4972.5  798.91
  4975.3  796.41  4975.5  792.96    4977  789.96    5023  789.96  5024.5  792.96
  5037.6  799.09    5043  799.95    5063  800.35  5076.3  804.59  5083.5  807.08
  5097.9  813.44  5116.5     823  5121.4  825.12  5138.3  831.96  5154.3  836.87
#Mann= 4 ,-1 , 0
  4596.1     .07       0  4918.1     .13       0  4975.5    .045       0
  5024.5     .13       0
Bank Sta=4975.5,5024.5
Exp/Cntr=0.3,0.1

Type RM Length L Ch R = 1 ,30853   ,452,452,452
BEGIN DESCRIPTION:
North Deep Creek 84.0
END DESCRIPTION:
XS GIS Cut Line= 4
      1522699.23       870555.18      1522622.87       870191.57
      1522477.42       869900.66      1522462.87        869602.5
#Sta/Elev= 30
    4367  816.83  4403.8  814.38  4557.4  806.85  4620.6  804.97    4639  803.86
  4692.9  801.91  4729.8  801.33  4756.5  800.04  4777.8   799.9  4819.2  797.94
  4880.8  797.12  4893.9  796.71    4917  797.73  4932.5  795.31  4940.6  794.49
  4954.5  794.55  4971.5  792.86  4975.5  792.85    4977  789.85    5023  789.85
  5024.5  792.85  5025.5  794.06  5032.5   797.7  5055.4  798.04  5090.5  799.71
  5156.6   805.1  5218.6  812.29  5290.3  823.17  5350.9  830.43  5362.3  831.41
#Mann= 4 ,-1 , 0
    4367     .07       0  4880.8     .13       0  4975.5    .045       0
  5024.5     .07       0
Bank Sta=4975.5,5024.5
Exp/Cntr=0.3,0.1

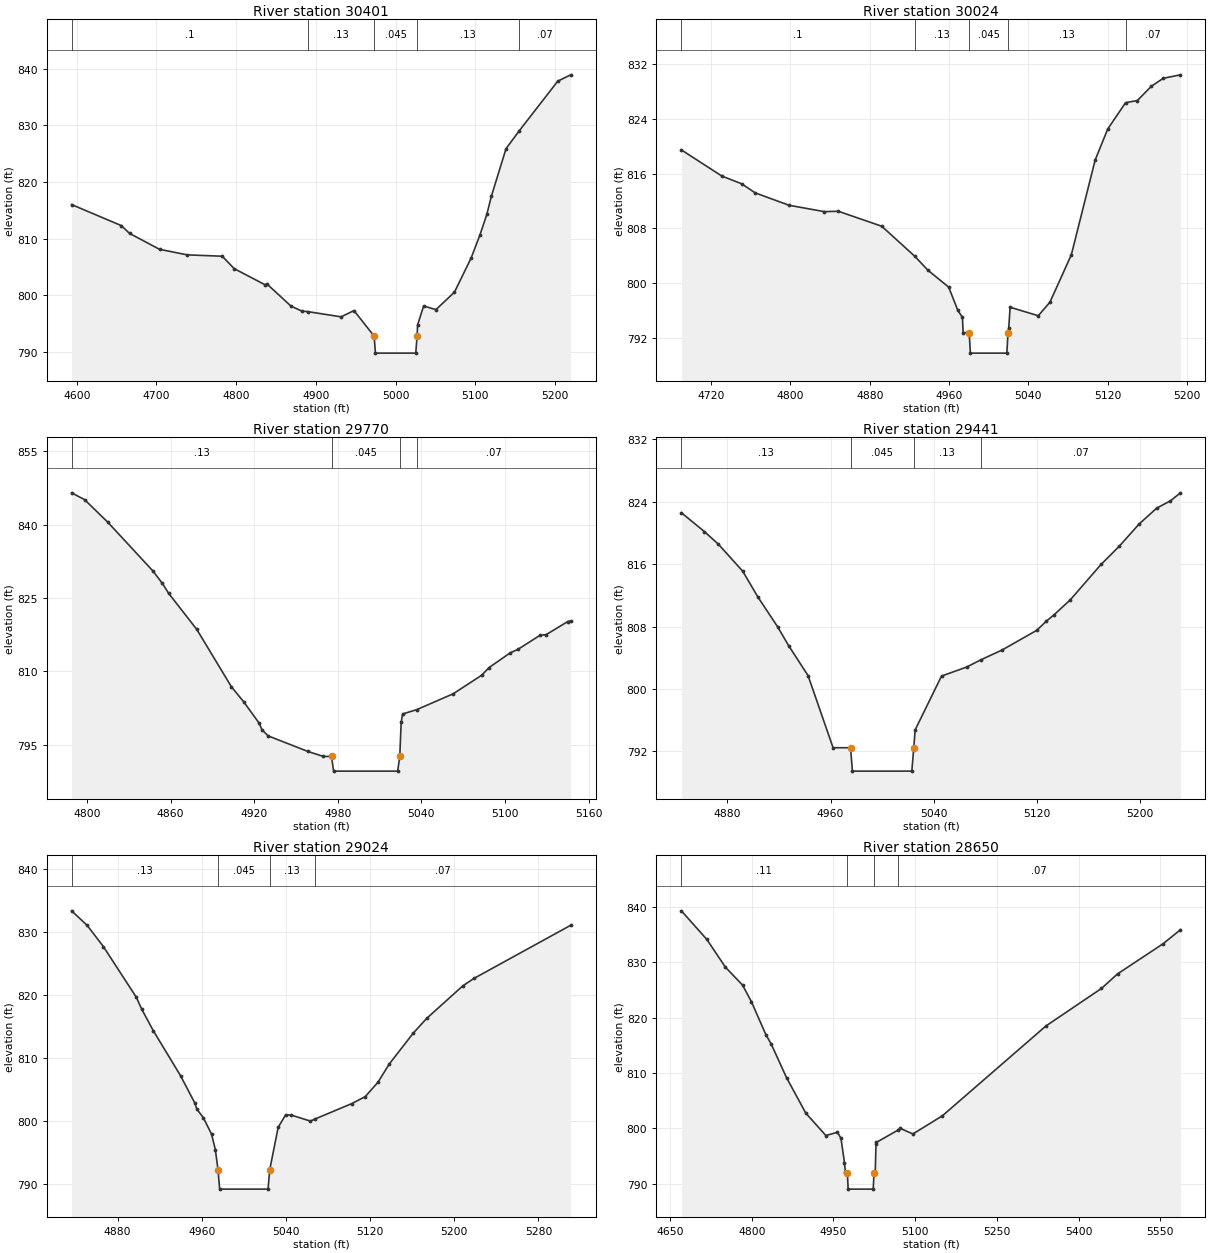
Type RM Length L Ch R = 1 ,30401   ,377,377,377
BEGIN DESCRIPTION:
North Deep Creek 83.0
END DESCRIPTION:
XS GIS Cut Line= 4
      1523142.86        870206.1      1522942.87       870053.39
      1522917.42       869827.93      1522891.96       869682.46
#Sta/Elev= 30
  4593.5  816.01  4655.8   812.3  4666.2  810.92  4703.8  808.11  4738.6  807.13
  4782.5  806.89  4797.5   804.7  4835.7  801.89    4839  801.94  4868.7  798.09
  4882.3  797.21  4890.7  797.09  4931.6  796.19  4947.8  797.29  4973.1  792.78
  4974.7  789.78  5025.3  789.78    5027  792.78  5027.6  794.75  5035.2  798.11
  5050.6  797.46  5073.8  800.53  5094.8  806.58  5105.7  810.58  5114.5  814.28
  5120.1  817.44  5138.6  825.89    5155  829.01  5203.5   837.8  5219.7  838.92
#Mann= 5 ,-1 , 0
  4593.5      .1       0  4890.7     .13       0  4973.1    .045       0
    5027     .13       0    5155     .07       0
Bank Sta=4973.1,5027
Exp/Cntr=0.3,0.1

Type RM Length L Ch R = 1 ,30024   ,254,254,254
BEGIN DESCRIPTION:
North Deep Creek 82.0
END DESCRIPTION:
XS GIS Cut Line= 4
      1523386.52       870137.05      1523342.88       869933.38
      1523259.24       869798.84      1523219.24       869667.92
#Sta/Elev= 30
    4690  819.46  4730.9  815.63  4750.7  814.51  4764.4  813.18  4798.6  811.36
  4834.2  810.43  4848.4  810.48  4892.2  808.29  4925.7  803.87  4938.8  801.85
  4959.7  799.38    4969  795.96  4973.6  794.97  4974.3  792.72  4980.4  792.72
  4981.6  789.72  5018.4  789.72  5019.6  792.72  5020.3  793.37  5021.7  796.44
  5050.1  795.19  5061.9  797.18  5083.5  804.12  5107.5  817.97  5120.2  822.52
  5138.2  826.37  5150.1  826.69  5164.2  828.77  5176.2  829.94  5193.6  830.45
#Mann= 5 ,-1 , 0
    4690      .1       0  4925.7     .13       0  4980.4    .045       0
  5019.6     .13       0  5138.2     .07       0
Bank Sta=4980.4,5019.6
Exp/Cntr=0.3,0.1

Type RM Length L Ch R = 1 ,29770   ,329,329,329
BEGIN DESCRIPTION:
North Deep Creek 81.0
END DESCRIPTION:
XS GIS Cut Line= 4
      1523695.63       869737.02      1523571.97       869737.02
      1523477.42       869693.38      1523350.19        869664.3
#Sta/Elev= 30
  4788.9  846.47  4798.2  845.08  4814.8  840.49  4847.1  830.56  4853.9  828.04
  4858.6  825.93  4878.8  818.56  4903.6  806.87  4912.6  803.74  4923.6   799.4
  4925.5  798.11  4929.9  796.84  4958.6  793.64  4969.7  792.63  4975.5  792.63
    4977  789.63    5023  789.63  5024.5  792.63  5025.5   799.6  5026.5   801.3
  5036.8   802.2  5062.8  805.42  5083.3  809.21  5088.6  810.78  5103.7  813.77
  5109.3   814.5  5125.1  817.35  5129.6  817.51  5145.1  820.18  5147.2  820.31
#Mann= 4 ,-1 , 0
  4788.9     .13       0  4975.5    .045       0  5024.5     .13       0
  5036.8     .07       0
Bank Sta=4975.5,5024.5
Exp/Cntr=0.3,0.1

Type RM Length L Ch R = 1 ,29441   ,417,417,417
BEGIN DESCRIPTION:
North Deep Creek 80.0
END DESCRIPTION:
XS GIS Cut Line= 3
      1523684.69       869391.56      1523582.88       869377.02
      1523299.22       869384.29
#Sta/Elev= 28
  4844.5   822.6  4862.3  820.18  4873.1  818.57    4892   815.1  4903.6  811.83
    4919  807.98  4927.5  805.57  4942.6  801.72    4962  792.46  4975.5  792.46
    4977  789.46    5023  789.46  5024.5  792.46  5025.6  794.76    5046  801.65
  5065.5  802.81  5076.4  803.73    5093     805  5119.8  807.52  5127.3  808.71
    5133  809.48  5145.7  811.42  5169.6  815.97  5183.7   818.3    5199  821.14
  5212.7  823.19  5223.3  824.12  5231.1  825.15
#Mann= 4 ,-1 , 0
  4844.5     .13       0  4975.5    .045       0  5024.5     .13       0
  5076.4     .07       0
Bank Sta=4975.5,5024.5
Exp/Cntr=0.3,0.1

Type RM Length L Ch R = 1 ,29024   ,374,374,374
BEGIN DESCRIPTION:
North Deep Creek 79.0
END DESCRIPTION:
XS GIS Cut Line= 3
      1523681.03       868966.11      1523430.15       868958.83
      1523215.57       869020.66
#Sta/Elev= 30
  4836.3  833.31  4851.1     831  4866.5  827.64  4897.8  819.61    4903   817.7
  4913.9  814.32  4939.8  807.18  4953.6  802.78  4955.3  801.88  4961.4  800.55
  4969.3  797.91  4972.9  795.45  4975.5   792.2    4977   789.2    5023   789.2
  5024.5   792.2  5032.6  798.99  5039.7  800.98  5044.9  800.94  5063.3  799.98
  5067.7  800.32  5102.5  802.75  5115.4  803.87  5127.4  806.13  5138.3  809.06
  5161.1  813.95  5173.8  816.27  5208.1  821.42  5218.6  822.59  5310.6  831.02
#Mann= 4 ,-1 , 0
  4836.3     .13       0  4975.5    .045       0  5024.5     .13       0
  5067.7     .07       0
Bank Sta=4975.5,5024.5
Exp/Cntr=0.3,0.1

Type RM Length L Ch R = 1 ,28650   ,341,341,341
BEGIN DESCRIPTION:
North Deep Creek 78.0
END DESCRIPTION:
XS GIS Cut Line= 4
      1523811.97       868587.92       1523575.6       868580.65
      1523390.15       868598.83      1522942.86       868806.11
#Sta/Elev= 30
    4671  839.29  4717.5  834.14  4751.8  829.11  4783.2  825.87  4799.3   822.9
  4826.4  816.83  4835.6  815.26  4863.9  809.14  4899.2  802.74  4936.1  798.68
  4957.4  799.26  4963.8  798.18  4970.2   793.8  4971.9  792.01  4975.5  791.99
    4977  788.99    5023  788.99  5024.5  791.99  5026.7  791.99  5028.1  797.08
  5028.7  797.43  5068.5  799.66  5072.9  799.96  5095.8  798.96  5150.1  802.26
  5339.8  818.47  5441.8  825.26  5471.3  827.89  5555.1  833.35  5586.8  835.88
#Mann= 4 ,-1 , 0
    4671     .11       0  4975.5    .045       0  5024.5     .11       0
  5068.5     .07       0
Bank Sta=4975.5,5024.5
Exp/Cntr=0.3,0.1

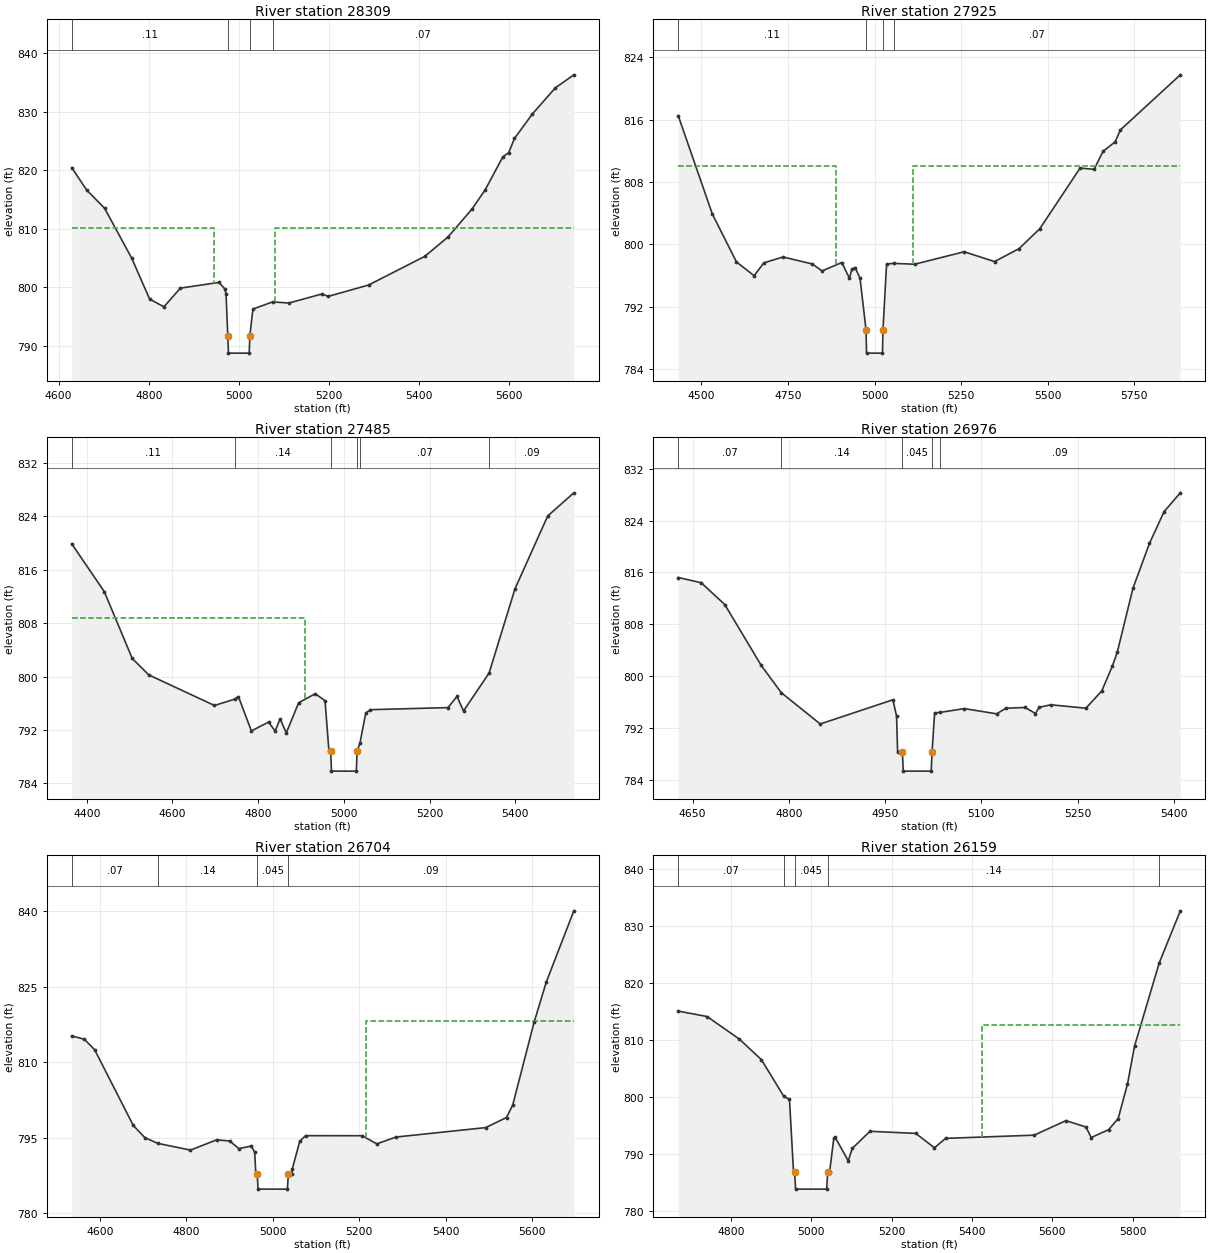
Type RM Length L Ch R = 1 ,28309   ,384,384,384
BEGIN DESCRIPTION:
North Deep Creek 77.5
END DESCRIPTION:
XS GIS Cut Line= 4
      1523778.75       868118.49      1523631.57       868142.45
      1523169.36        868409.5      1522874.92       868724.48
#Sta/Elev= 30
  4629.3  820.46  4662.4  816.62    4702  813.54  4762.4  804.99    4802  798.03
  4833.7   796.7  4870.3  799.89    4956  800.87  4968.5  799.79  4971.6  798.93
  4975.5   791.8    4977   788.8    5023   788.8  5024.5   791.8  5031.3  796.32
    5075  797.54  5111.2  797.35  5183.7  798.88  5198.7  798.49  5287.9  800.42
  5412.6  805.31  5463.9   808.6  5517.6   813.4  5547.1  816.72  5585.6  822.26
    5599  823.03  5611.6  825.43  5651.3   829.6  5702.4  834.07  5743.4  836.29
#Mann= 4 ,-1 , 0
  4629.3     .11       0  4975.5    .045       0  5024.5     .11       0
    5075     .07       0
#XS Ineff= 2 , 0
       0  4945.8  810.14  5081.1       0  810.14
Permanent Ineff=
       F       F
Bank Sta=4975.5,5024.5
Exp/Cntr=0.3,0.1

Type RM Length L Ch R = 1 ,27925   ,440,440,440
BEGIN DESCRIPTION:
North Deep Creek 77.0
END DESCRIPTION:
XS GIS Cut Line= 5
      1523797.47       868042.48      1523324.69        867926.1
      1523142.87       867940.65      1522801.05       868042.46
      1522502.89       868344.27
#Sta/Elev= 30
  4433.1   816.5  4531.5   803.9  4601.3  797.74  4652.3  795.98  4680.4  797.63
    4736  798.38  4820.6  797.48  4848.5  796.59  4905.6  797.67  4927.6  795.65
  4934.6  796.83  4944.2  797.03  4958.2  795.65  4975.5  789.05    4977  786.05
    5023  786.05  5024.5  789.05  5034.9  797.48  5056.1  797.56    5116  797.45
    5259  799.05  5346.7  797.79  5417.8  799.46  5477.6  802.01  5593.8  809.78
  5634.2  809.62  5660.3  811.94  5694.8  813.13  5710.5  814.69  5883.3  821.74
#Mann= 4 ,-1 , 0
  4433.1     .11       0  4975.5    .045       0  5024.5     .11       0
  5056.1     .07       0
#XS Ineff= 2 , 0
       0  4888.3  810.06  5111.7       0  810.06
Permanent Ineff=
       F       F
Bank Sta=4975.5,5024.5
Exp/Cntr=0.3,0.1

Type RM Length L Ch R = 1 ,27485   ,509,509,509
BEGIN DESCRIPTION:
North Deep Creek 76.0
END DESCRIPTION:
XS GIS Cut Line= 5
      1523924.68       867944.27      1523473.79       867620.64
      1523382.88       867493.37       1523295.6       867257.01
      1523310.15       867049.69
#Sta/Elev= 30
  4365.2  819.88    4441  812.73  4506.3   802.7  4544.9  800.24    4698  795.66
    4745   796.6  4753.9     797  4784.2  791.84  4824.2  793.17  4839.6  791.83
  4851.2  793.66  4865.6  791.54  4894.4  796.06    4933  797.42    4956  796.38
  4965.1  788.84  4969.2  788.82    4971  785.82    5029  785.82  5030.8  788.82
  5037.4     790    5051  794.53    5062  795.03  5242.8  795.34  5263.9  797.01
    5279  794.84  5338.7  800.52  5399.1  813.14  5475.4  824.06  5536.4  827.53
#Mann= 6 ,-1 , 0
  4365.2     .11       0    4745     .14       0  4969.2    .045       0
  5030.8     .14       0  5037.4     .07       0  5338.7     .09       0
#XS Ineff= 2 , 0
       0  4909.3  808.79               0
Permanent Ineff=
       F       F
Bank Sta=4969.2,5030.8
Exp/Cntr=0.3,0.1

Type RM Length L Ch R = 1 ,26976   ,272,272,272
BEGIN DESCRIPTION:
North Deep Creek 74.0
END DESCRIPTION:
XS GIS Cut Line= 5
      1523997.45       867482.49      1523877.42       867315.19
      1523677.42       867198.82      1523477.42       867093.37
      1523371.99       867038.83
#Sta/Elev= 30
  4627.7  815.21  4663.5   814.4  4700.2  811.03  4756.8  801.66  4788.2  797.42
  4848.9  792.58  4962.1  796.32  4967.8   793.8  4969.4  788.31  4976.9   788.3
  4978.2   785.3  5021.8   785.3  5023.1   788.3  5027.1   794.3  5035.6  794.37
  5073.3  794.96  5123.7  794.15  5138.2  795.02    5168  795.13  5184.2   794.2
    5190  795.16  5208.1  795.55  5262.7  795.02  5287.4  797.68  5303.8  801.49
  5311.6  803.67    5336  813.53  5361.8   820.5  5384.6   825.4  5409.8  828.29
#Mann= 5 ,-1 , 0
  4627.7     .07       0  4788.2     .14       0  4976.9    .045       0
  5023.1     .14       0  5035.6     .09       0
Bank Sta=4976.9,5023.1
Exp/Cntr=0.3,0.1

Type RM Length L Ch R = 1 ,26704   ,545,545,545
BEGIN DESCRIPTION:
North Deep Creek 73.0
END DESCRIPTION:
XS GIS Cut Line= 4
      1524015.62       867460.69       1523884.7         867097.
       1523884.7       866475.18       1523884.7       866322.44
#Sta/Elev= 30
  4535.2  815.23  4564.6  814.54  4588.2  812.46  4677.3  797.45  4704.1  795.02
  4733.8  793.88  4809.7  792.53  4870.2  794.57  4900.5  794.34  4921.7  792.82
  4950.6  793.35  4958.2  792.12  4960.9  787.79    4964  787.78  4966.1  784.78
  5033.9  784.78    5036  787.78  5044.4  787.78  5044.9  788.71  5062.5   794.3
  5075.8   795.4    5207  795.39  5240.6  793.77  5285.2  795.13  5492.2     797
  5540.6  799.01  5555.1  801.53  5604.3  817.91  5632.6  825.93  5696.3  840.07
#Mann= 4 ,-1 , 0
  4535.2     .07       0  4733.8     .14       0    4964    .045       0
    5036     .09       0
#XS Ineff= 2 , 0
       0                  5215.7       0  818.12
Permanent Ineff=
       F       F
Bank Sta=4964,5036
Exp/Cntr=0.3,0.1

Type RM Length L Ch R = 1 ,26159   ,675,675,675
BEGIN DESCRIPTION:
North Deep Creek 72.0
END DESCRIPTION:
XS GIS Cut Line= 4
      1524066.52       867515.19      1524281.06       867184.28
      1524397.43       866558.82      1524390.15       866340.61
#Sta/Elev= 30
  4669.4  815.11  4741.2  814.16  4821.6  810.19  4876.4  806.58    4932  800.15
  4946.1  799.62  4956.2  786.87  4958.9  786.87  4961.3  783.87  5038.7  783.87
  5041.1  786.87  5045.9  786.87  5056.4  792.81  5059.2  793.03  5092.4  788.83
  5102.2  791.01  5146.2  794.02  5260.2  793.65  5306.8  791.12  5334.3  792.78
  5554.8  793.34  5633.7  795.89  5683.6  794.77  5696.7  792.92    5740  794.31
  5763.7  796.25  5786.9  802.31  5804.4  808.95  5865.8  823.56  5918.3  832.71
#Mann= 5 ,-1 , 0
  4669.4     .07       0    4932     .14       0  4958.9    .045       0
  5041.1     .14       0  5865.8     .14       0
#XS Ineff= 2 , 0
       0                  5424.5       0  812.64
Permanent Ineff=
       F       F
Bank Sta=4958.9,5041.1
Exp/Cntr=0.3,0.1

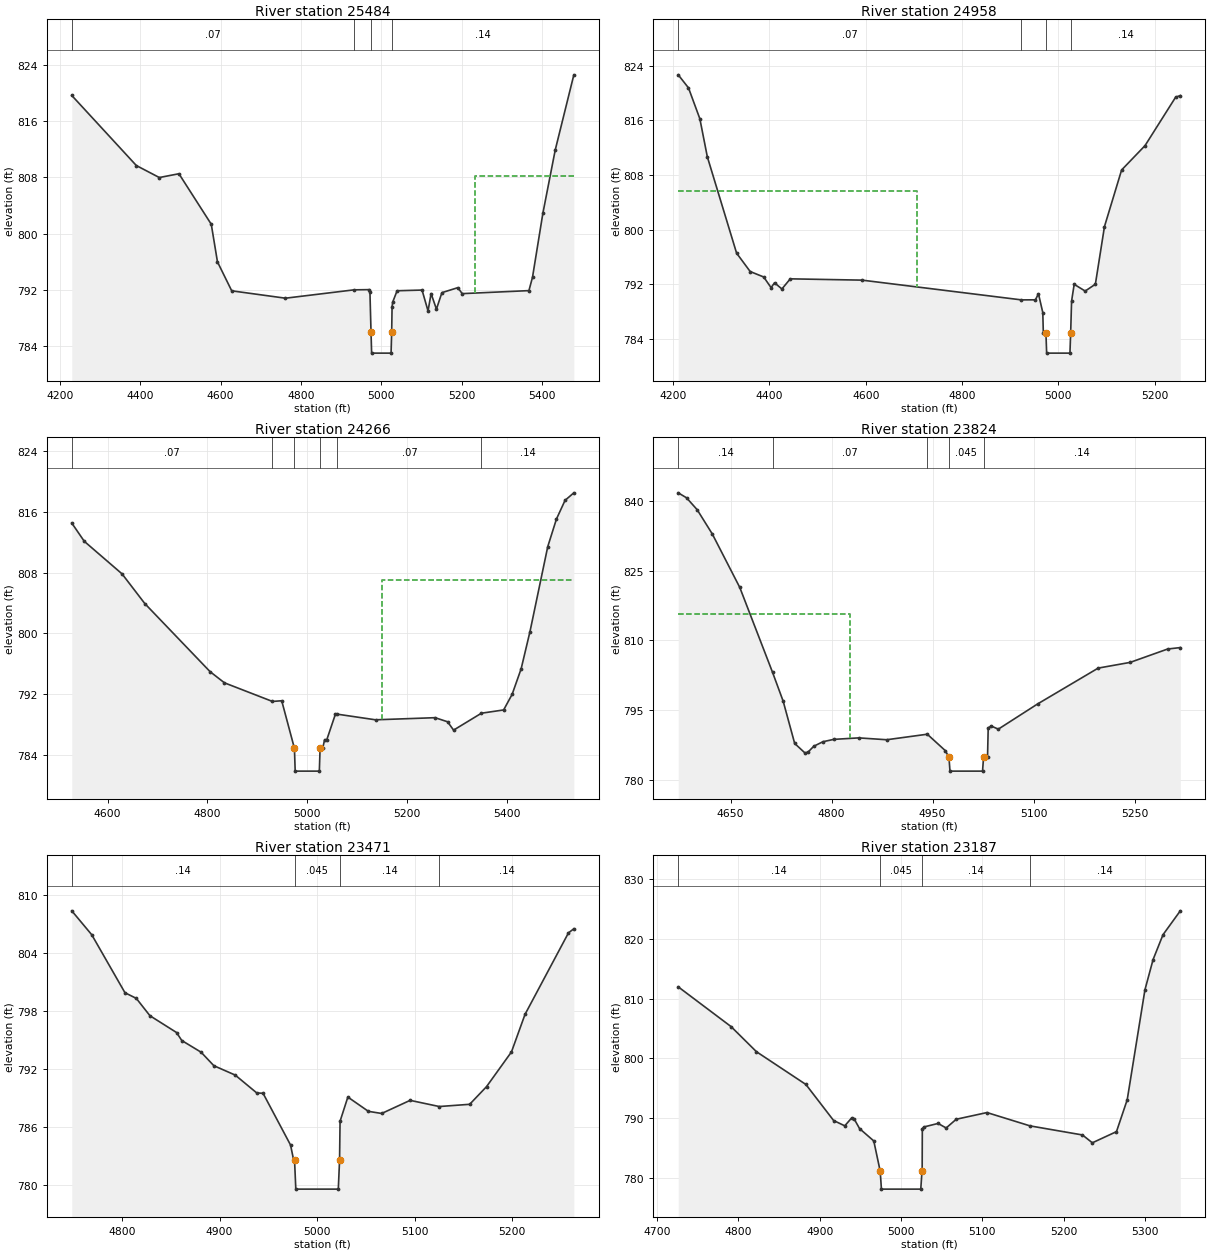
Type RM Length L Ch R = 1 ,25484   ,526,526,526
BEGIN DESCRIPTION:
North Deep Creek 71.0
END DESCRIPTION:
XS GIS Cut Line= 4
      1524350.16       868013.37      1524582.88       867835.19
      1524808.34       867464.28      1525022.88       866987.92
#Sta/Elev= 30
  4229.5  819.68  4390.2  809.69  4447.4  807.98  4496.2  808.52  4576.7  801.32
  4592.1  795.96  4627.6  791.83  4761.4  790.78    4932  791.97  4969.9     792
  4971.6  791.63  4974.3  785.95  4975.8  782.95  5024.2  782.95  5025.7  785.95
  5026.7  789.55  5028.2  790.22  5039.2  791.84  5101.3  791.94  5116.2  788.96
  5123.8  791.44  5137.1  789.22  5150.7  791.57  5190.3  792.28  5201.3  791.43
  5367.3  791.86  5376.2  793.76    5402  802.88  5432.8  811.91  5479.1  822.62
#Mann= 4 ,-1 , 0
  4229.5     .07       0    4932     .14       0  4974.3    .045       0
  5025.7     .14       0
#XS Ineff= 2 , 0
       0                  5233.8       0  808.26
Permanent Ineff=
       F       F
Bank Sta=4974.3,5025.7
Exp/Cntr=0.3,0.1

Type RM Length L Ch R = 1 ,24958   ,692,692,692
BEGIN DESCRIPTION:
North Deep Creek 70.0
END DESCRIPTION:
XS GIS Cut Line= 4
      1524528.33       868344.29      1525095.61       867838.83
      1525161.07       867773.37      1525332.02       867689.71
#Sta/Elev= 30
  4210.7  822.66    4232  820.75  4255.6  816.23  4271.1  810.67  4331.9  796.57
  4360.1  793.88  4388.2  793.08  4403.5  791.52  4410.7  792.23    4426  791.33
  4443.4  792.81  4592.4  792.62  4923.5  789.73  4952.5  789.74  4958.8  790.63
  4967.8  787.88  4968.9  784.94  4974.3  784.94  4975.8  781.94  5024.2  781.94
  5025.7  784.94  5027.6  789.55    5033  792.01  5055.8  791.02    5077  792.02
  5095.9  800.46  5131.5  808.74  5180.1   812.3  5243.7  819.39  5253.4  819.62
#Mann= 4 ,-1 , 0
  4210.7     .07       0  4923.5     .14       0  4974.3    .045       0
  5025.7     .14       0
#XS Ineff= 2 , 0
       0  4706.2  805.64               0
Permanent Ineff=
       F       F
Bank Sta=4974.3,5025.7
Exp/Cntr=0.3,0.1

Type RM Length L Ch R = 1 ,24266   ,442,442,442
BEGIN DESCRIPTION:
North Deep Creek 69.0
END DESCRIPTION:
XS GIS Cut Line= 5
      1525233.82       868675.16      1525408.34       868464.29
      1525684.71       868242.47      1525862.89       868140.65
      1525975.63       868009.72
#Sta/Elev= 30
  4528.1  814.54  4553.2  812.13  4628.9  807.84  4674.5  803.93  4805.3  794.96
  4834.1  793.49  4930.2  791.04  4948.8  791.13  4974.3  784.86  4975.8  781.86
  5024.2  781.86  5025.7  784.86  5030.9  784.86  5034.8  786.01  5038.8  785.93
  5056.5  789.38  5060.5  789.36  5136.8  788.62  5256.2   788.9  5281.2  788.36
  5293.2  787.26    5349  789.49  5393.5  789.92  5410.5  791.97  5428.6  795.34
  5446.3  800.24  5481.9  811.43  5499.3  815.06  5516.6  817.53  5534.2  818.52
#Mann= 6 ,-1 , 0
  4528.1     .07       0  4930.2     .14       0  4974.3    .045       0
  5025.7     .14       0  5060.5     .07       0    5349     .14       0
#XS Ineff= 2 , 0
       0                    5150       0     807
Permanent Ineff=
       F       F
Bank Sta=4974.3,5025.7
Exp/Cntr=0.3,0.1

Type RM Length L Ch R = 1 ,23824   ,353,353,353
BEGIN DESCRIPTION:
North Deep Creek 68.0
END DESCRIPTION:
XS GIS Cut Line= 5
      1525633.79       869075.22      1525691.98       868922.47
      1525801.07       868726.11      1525859.25        868635.2
      1525950.17       868402.45
#Sta/Elev= 30
  4572.1  841.76  4584.4  840.69  4600.2  838.13  4622.7   832.9  4663.5  821.39
  4712.2   803.1    4728  796.88  4745.1  787.78  4760.4  785.73    4765  785.93
  4773.5  787.18    4787  788.15  4803.2  788.66  4840.3  788.98  4881.8  788.58
  4942.1  789.77  4968.8  786.24  4974.3  784.82  4975.8  781.82  5024.2  781.82
  5025.7  784.82  5031.6  784.83  5032.6  791.13    5037  791.54  5047.6  790.86
    5106  796.29    5196  804.01  5243.5  805.24  5299.2  808.12    5318  808.43
#Mann= 5 ,-1 , 0
  4572.1     .14       0  4712.2     .07       0  4942.1     .14       0
  4974.3    .045       0  5025.7     .14       0
#XS Ineff= 2 , 0
       0  4826.8  815.66               0
Permanent Ineff=
       F       F
Bank Sta=4974.3,5025.7
Exp/Cntr=0.3,0.1

Type RM Length L Ch R = 1 ,23471   ,284,284,284
BEGIN DESCRIPTION:
North Deep Creek 67.0
END DESCRIPTION:
XS GIS Cut Line= 4
       1526342.9       868769.75       1526193.8       868671.56
      1526048.35       868504.29      1525982.88       868409.73
#Sta/Elev= 30
  4748.3  808.41  4768.8  805.93  4802.9  799.92  4814.5  799.34  4828.5  797.54
  4855.8   795.8  4861.2  794.97    4881  793.76  4894.1  792.36    4916  791.39
  4938.1  789.54  4944.6   789.5  4972.8  784.14    4976  782.57  4976.9  782.57
  4978.2  779.57  5021.8  779.57  5023.1  782.57  5023.6   786.6  5031.6  789.11
  5052.7  787.63  5066.3  787.41  5095.5  788.77  5125.4  788.13  5156.6  788.36
  5173.9  790.19  5199.5  793.79  5213.4  797.68    5258  806.13  5263.5  806.55
#Mann= 4 ,-1 , 0
  4748.3     .14       0  4976.9    .045       0  5023.1     .14       0
  5125.4     .14       0
Bank Sta=4976.9,5023.1
Exp/Cntr=0.3,0.1

Type RM Length L Ch R = 1 ,23187   ,215,215,215
BEGIN DESCRIPTION:
North Deep Creek 66.0
END DESCRIPTION:
XS GIS Cut Line= 4
      1526397.44       868722.49      1526408.35       868500.65
      1526342.89       868398.83      1526171.96       868184.25
#Sta/Elev= 30
  4725.9  811.98  4790.9  805.33  4822.1  801.13  4882.9  795.65    4917  789.62
  4930.7  788.73    4939  790.02  4942.6   789.8  4948.9  788.27  4966.4   786.2
  4974.3  781.14  4975.8  778.14  5024.2  778.14  5025.7  781.14  5025.9  781.21
  5026.1  788.25    5028  788.54  5045.5  789.13  5055.4  788.37  5067.8  789.83
  5105.6  790.95  5158.6  788.72  5223.1   787.2  5235.2  785.89  5264.9  787.76
  5278.1  793.09  5299.9  811.49  5309.9  816.54  5322.1   820.7  5343.4   824.7
#Mann= 4 ,-1 , 0
  4725.9     .14       0  4974.3    .045       0  5025.7     .14       0
  5158.6     .14       0
Bank Sta=4974.3,5025.7
Exp/Cntr=0.3,0.1