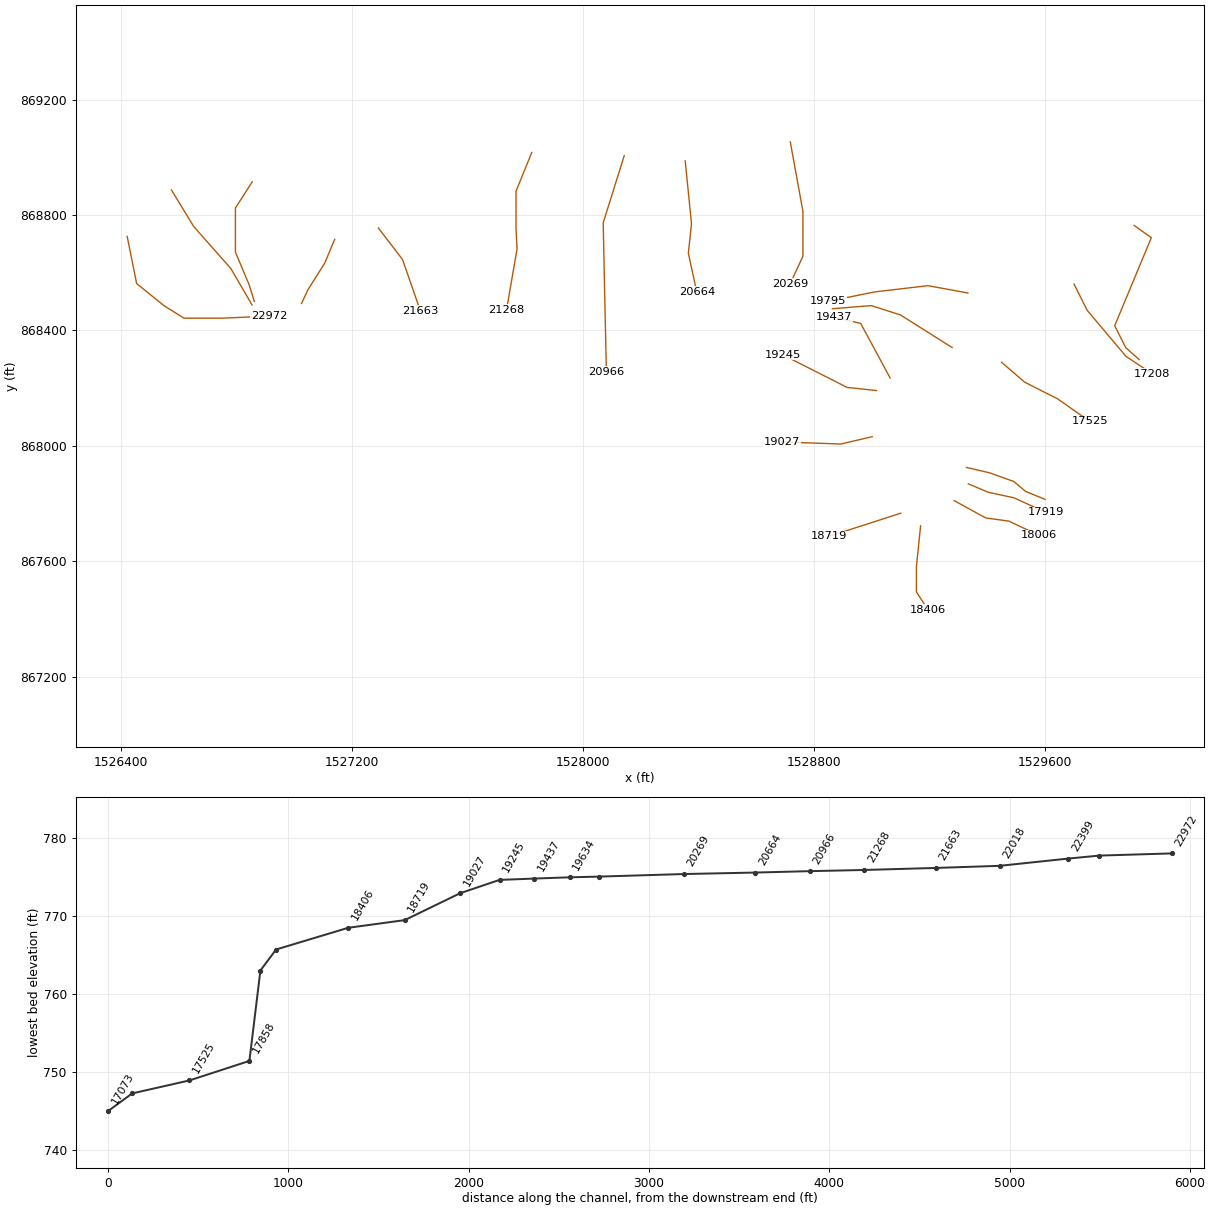
HEC-RAS study North Deep Creek.prj: North Deep Creek Limited Detail Study

--- North Deep Creek.g01 (geometry) --- (continued)

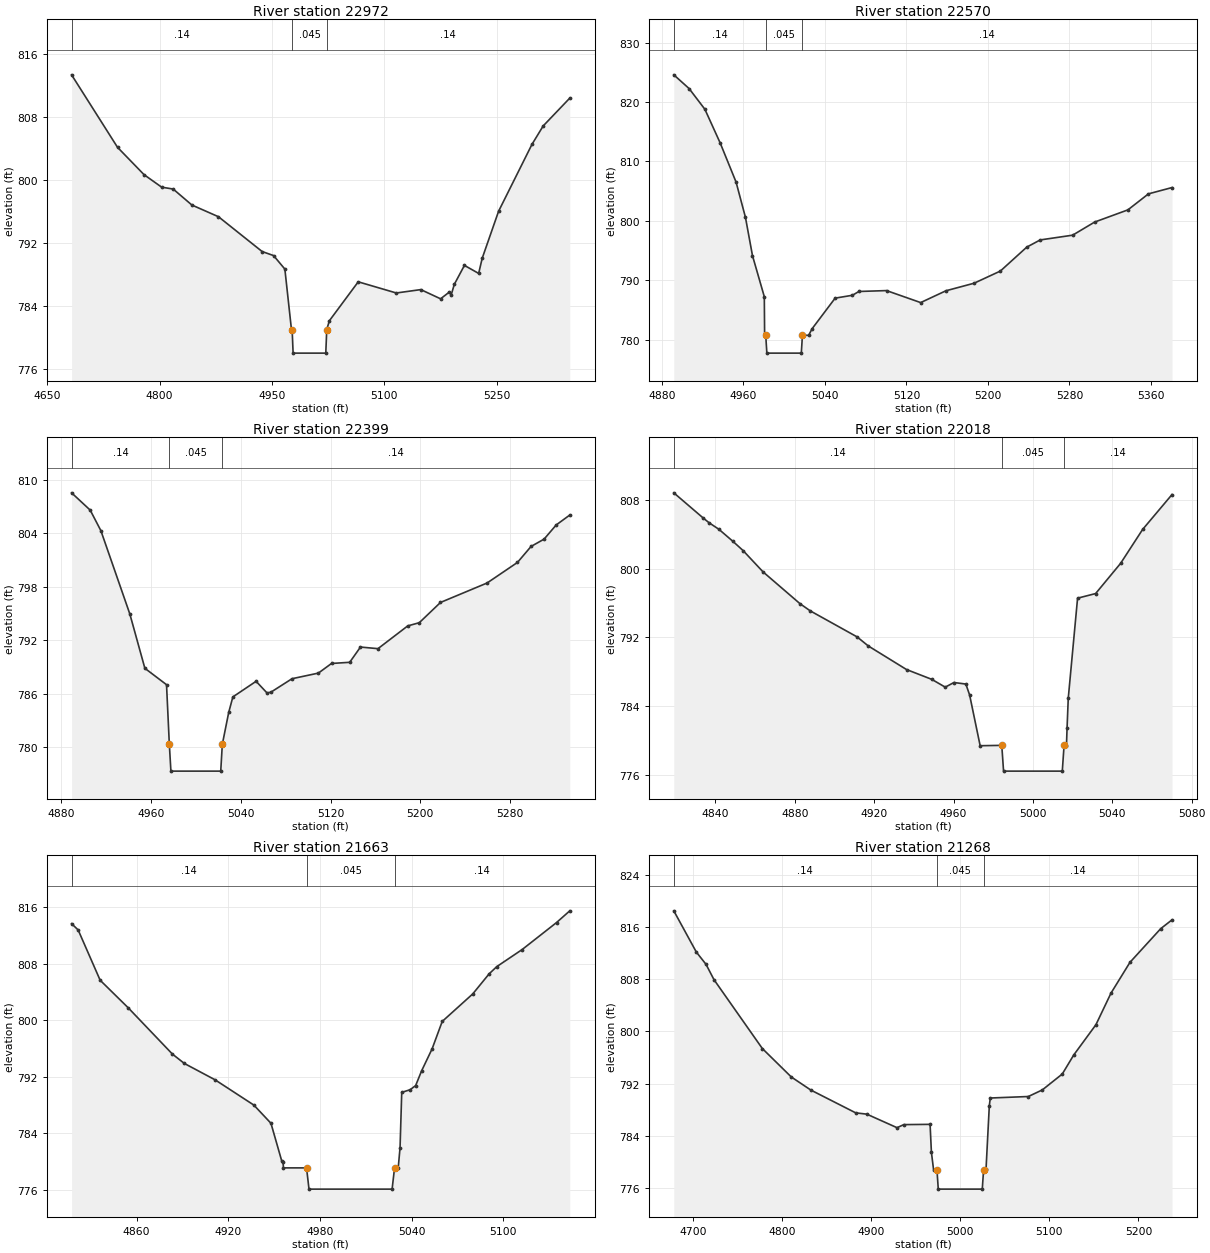
Type RM Length L Ch R = 1 ,22972   ,402,402,402
BEGIN DESCRIPTION:
North Deep Creek 65.0
END DESCRIPTION:
XS GIS Cut Line= 6
       1526422.9       868726.08      1526455.62       868562.47
      1526550.17        868486.1      1526619.26       868442.47
       1526753.8       868442.47      1526913.79       868449.74
#Sta/Elev= 30
  4682.6   813.4  4743.9  804.18  4779.3   800.7  4802.8  799.11  4818.2  798.87
  4843.1  796.84  4878.6  795.35  4936.9  790.92  4952.1  790.41  4967.2  788.69
    4976     781  4976.9     781  4978.2     778  5021.8     778  5023.1     781
  5026.6  782.12  5065.1  787.07  5115.9  785.65  5148.6  786.08    5175  784.91
  5186.7  785.77  5189.3  785.45  5193.3  786.75  5206.8  789.16  5225.8  788.14
  5230.5  790.06  5252.4  796.05  5296.9  804.55  5311.9   806.9  5347.4  810.44
#Mann= 3 ,-1 , 0
  4682.6     .14       0  4976.9    .045       0  5023.1     .14       0
Bank Sta=4976.9,5023.1
Exp/Cntr=0.3,0.1

Type RM Length L Ch R = 1 ,22570   ,171,171,171
BEGIN DESCRIPTION:
North Deep Creek 64.0
END DESCRIPTION:
XS GIS Cut Line= 4
      1526576.01       868887.12      1526653.05       868760.44
      1526781.44       868614.93      1526855.04       868488.28
#Sta/Elev= 30
  4891.8  824.58  4906.8  822.27  4922.3  818.78  4937.3  813.11  4952.9  806.52
  4962.1  800.58    4969  794.13  4980.6  787.22  4980.9  780.73    4982  780.72
  4983.1  777.72  5016.9  777.72    5018  780.72  5024.1  780.72  5027.5  781.83
  5050.1  786.98    5067  787.46  5073.4   788.1  5100.5  788.25    5134  786.23
  5158.8  788.22  5186.4  789.49  5212.2  791.54  5238.1  795.57  5251.3  796.78
  5283.1  797.58  5304.7  799.79  5337.3  801.84  5357.5  804.54  5380.6   805.6
#Mann= 3 ,-1 , 0
  4891.8     .14       0    4982    .045       0    5018     .14       0
Bank Sta=4982,5018
Exp/Cntr=0.3,0.1

Type RM Length L Ch R = 1 ,22399   ,381,381,381
BEGIN DESCRIPTION:
North Deep Creek 63.0
END DESCRIPTION:
XS GIS Cut Line= 5
      1526855.63       868915.21      1526797.44       868824.29
      1526797.44       868671.56      1526844.71       868558.83
       1526862.9       868500.62
#Sta/Elev= 30
  4889.3  808.54  4905.9   806.6  4915.4   804.3  4941.2  794.96  4954.6  788.87
  4973.9  787.03  4976.4  780.34  4977.8  777.34  5022.2  777.34  5023.6  780.34
  5029.3  783.92    5033  785.66  5053.7  787.41  5063.4  786.11  5066.9  786.19
  5085.7   787.7  5109.2  788.33  5120.9  789.41  5137.1  789.54  5146.7  791.25
  5162.3  791.07  5188.8  793.62  5199.1  793.98    5218  796.25  5259.5  798.43
  5286.6  800.74  5298.7  802.53  5310.3  803.35  5321.1  804.94  5333.2  806.05
#Mann= 3 ,-1 , 0
  4889.3     .14       0  4976.4    .045       0  5023.6     .14       0
Bank Sta=4976.4,5023.6
Exp/Cntr=0.3,0.1

Type RM Length L Ch R = 1 ,22018   ,355,355,355
BEGIN DESCRIPTION:
North Deep Creek 61.0
END DESCRIPTION:
XS GIS Cut Line= 4
      1527140.92       868715.89       1527106.7       868633.76
       1527048.5       868541.32      1527026.22       868493.35
#Sta/Elev= 30
    4819  808.82  4833.7  805.91  4836.8  805.33  4841.7  804.58  4848.6  803.21
  4853.9   802.1    4864  799.61  4882.6  795.91  4887.8  795.07  4911.4  792.04
    4917  790.99  4936.3  788.24    4949   787.1  4955.8  786.19  4960.2  786.73
  4966.2  786.55  4968.1  785.27  4973.4  779.37  4984.3  779.41  4985.2  776.41
  5014.8  776.41  5015.7  779.41  5016.9  779.37  5017.2  781.39  5017.8  784.88
  5022.5  796.55  5031.6  797.09  5044.2  800.61  5055.3  804.56  5070.1  808.62
#Mann= 3 ,-1 , 0
    4819     .14       0  4984.3    .045       0  5015.7     .14       0
Bank Sta=4984.3,5015.7
Exp/Cntr=0.3,0.1

Type RM Length L Ch R = 1 ,21663   ,395,395,395
BEGIN DESCRIPTION:
North Deep Creek 60.0
END DESCRIPTION:
XS GIS Cut Line= 3
        1527292.       868755.19      1527375.63        868646.1
      1527437.46       868467.88
#Sta/Elev= 30
  4817.4  813.63  4821.7  812.74  4836.1  805.64  4854.5  801.74  4883.4  795.21
  4891.2  793.89  4911.3  791.58  4936.7  788.01  4947.9  785.44  4954.9  780.16
  4955.8  779.93  4956.1  779.14  4971.2  779.14  4972.8  776.14  5027.2  776.14
  5028.8  779.14  5031.2  779.15  5032.4     782  5033.5   789.8    5039  790.18
  5042.6  790.76  5046.5  792.84  5053.4  795.96    5060  799.82    5080  803.71
  5090.7  806.54  5095.7  807.56  5112.3  809.97  5134.8  813.78  5143.5  815.44
#Mann= 3 ,-1 , 0
  4817.4     .14       0  4971.2    .045       0  5028.8     .14       0
Bank Sta=4971.2,5028.8
Exp/Cntr=0.3,0.1

Type RM Length L Ch R = 1 ,21268   ,302,302,302
BEGIN DESCRIPTION:
North Deep Creek 59.0
END DESCRIPTION:
XS GIS Cut Line= 5
      1527822.89         869017.      1527768.36       868882.47
      1527768.36       868751.56      1527771.99       868682.47
      1527735.62       868471.54
#Sta/Elev= 30
  4678.4  818.46  4703.7  812.15  4714.6  810.27  4723.5  807.93  4777.8  797.39
  4810.3  793.04  4832.2  791.04  4882.6  787.55  4895.1  787.35    4929  785.28
  4936.6  785.75  4966.1  785.79  4967.6  781.51    4970  778.88  4973.8  778.88
  4975.3  775.88  5024.7  775.88  5026.2  778.88  5028.9   778.9  5032.6  788.64
  5033.7  789.82  5076.4  790.05  5092.1  791.06  5114.5  793.49  5127.4  796.41
  5152.3  801.04  5169.2  805.87  5190.5  810.58    5225  815.73  5237.7  817.08
#Mann= 3 ,-1 , 0
  4678.4     .14       0  4973.8    .045       0  5026.2     .14       0
Bank Sta=4973.8,5026.2
Exp/Cntr=0.3,0.1

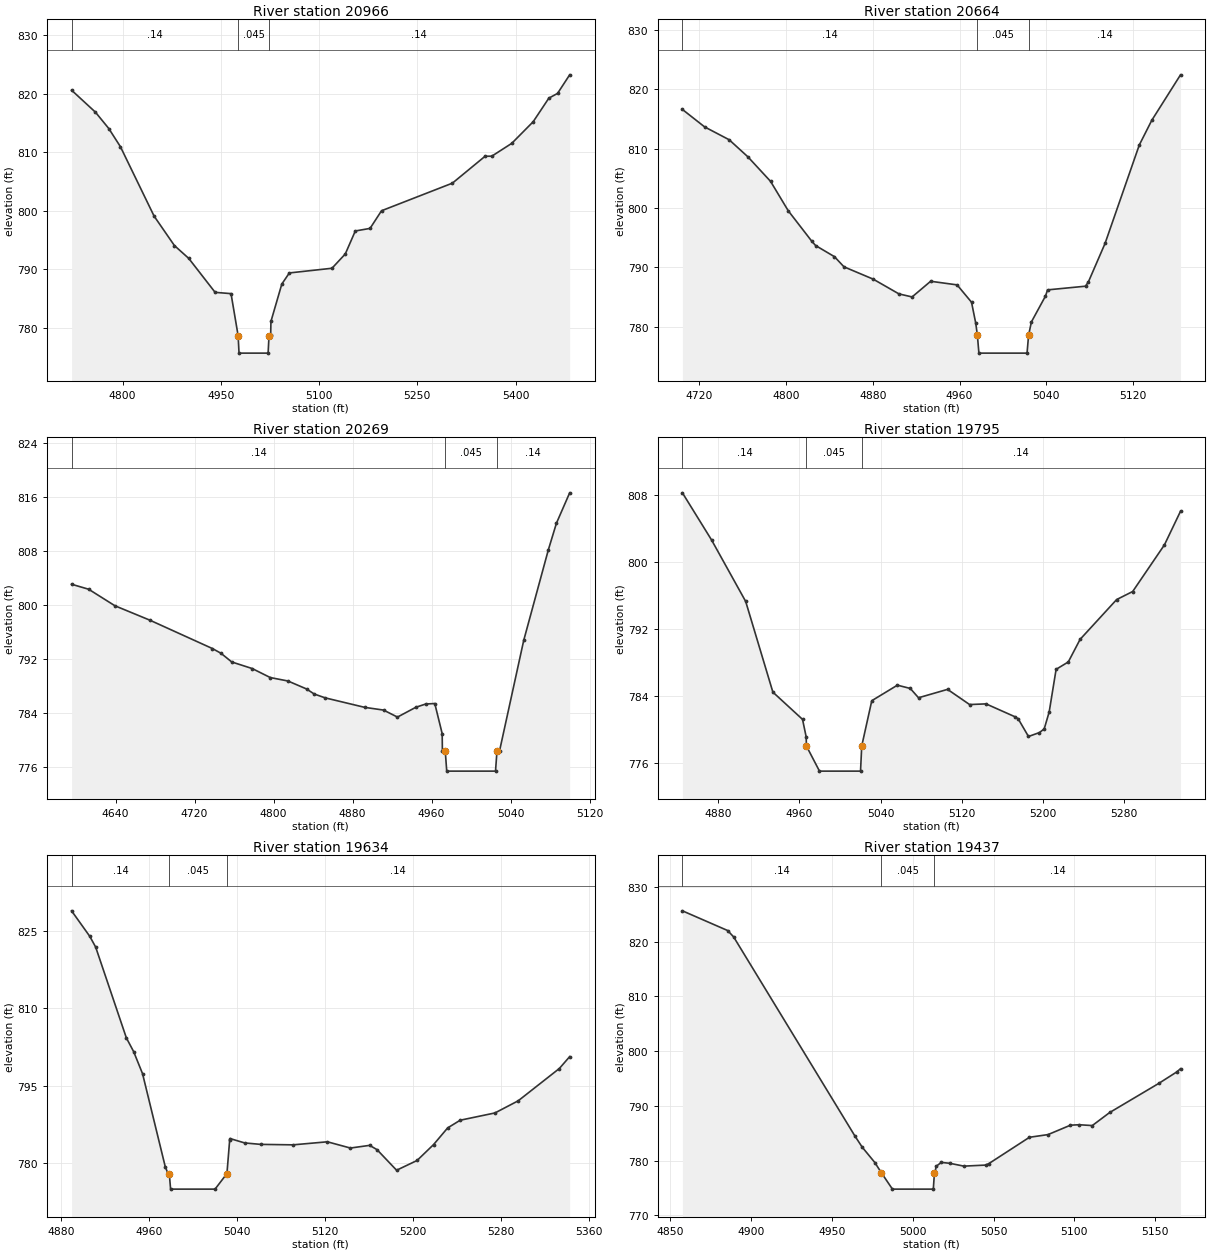
Type RM Length L Ch R = 1 ,20966   ,302,302,302
BEGIN DESCRIPTION:
North Deep Creek 58.0
END DESCRIPTION:
XS GIS Cut Line= 4
      1528142.91       869006.13      1528070.18       868773.38
      1528073.81       868591.56      1528081.08       868257.05
#Sta/Elev= 30
  4722.2  820.59  4758.7  816.83    4779  814.05  4796.7  810.96  4848.2   799.1
  4879.2  794.08    4901   791.9  4941.3   786.1  4965.6  785.88  4976.4  778.73
  4977.8  775.73  5022.2  775.73  5023.6  778.73  5026.1  778.74  5026.5  781.13
  5043.1  787.51  5054.6  789.41  5119.7  790.21    5140  792.65  5155.3  796.57
  5177.8  797.01  5195.3  800.02  5303.5  804.73  5353.4  809.32  5363.6  809.33
  5394.1  811.52  5426.8  815.21  5450.7  819.23    5464  820.04  5482.5  823.21
#Mann= 3 ,-1 , 0
  4722.2     .14       0  4976.4    .045       0  5023.6     .14       0
Bank Sta=4976.4,5023.6
Exp/Cntr=0.3,0.1

Type RM Length L Ch R = 1 ,20664   ,395,395,395
BEGIN DESCRIPTION:
North Deep Creek 57.0
END DESCRIPTION:
XS GIS Cut Line= 4
      1528353.82        868987.9      1528375.63       868769.74
      1528364.72       868667.92      1528393.81       868533.38
#Sta/Elev= 30
  4704.4  816.58  4724.9  813.64  4747.5  811.48  4764.8   808.6  4785.7  804.47
    4802  799.52  4823.7  794.39  4827.2  793.67  4844.6  791.79  4853.4  790.08
  4880.3  788.01  4904.1  785.52  4916.2  785.01  4933.3  787.65  4957.7  787.04
    4971  784.12  4974.9  780.58  4976.4  778.55  4977.8  775.55  5022.2  775.55
  5023.6  778.55  5026.2   780.8  5039.2  785.16  5041.1   786.2  5076.1  786.82
  5078.8  787.56  5094.1  794.01  5125.7   810.6  5137.2  814.75  5163.7  822.41
#Mann= 3 ,-1 , 0
  4704.4     .14       0  4976.4    .045       0  5023.6     .14       0
Bank Sta=4976.4,5023.6
Exp/Cntr=0.3,0.1

Type RM Length L Ch R = 1 ,20269   ,474,474,474
BEGIN DESCRIPTION:
North Deep Creek 56.0
END DESCRIPTION:
XS GIS Cut Line= 4
      1528717.45       869053.39      1528761.09       868813.38
      1528761.09       868657.01      1528717.47       868562.51
#Sta/Elev= 30
  4595.4  803.06  4612.7  802.32  4639.3  799.87  4674.6  797.74    4738  793.53
  4746.7  792.83  4757.6  791.54  4778.4  790.56  4796.6  789.23  4814.5  788.72
  4833.3  787.54  4841.1  786.79  4852.2  786.22  4892.3  784.81  4911.3  784.41
  4925.4  783.37  4944.1  784.83  4954.1  785.31  4963.2  785.38  4970.7  780.92
  4970.9  778.36  4973.8  778.36  4975.3  775.36  5024.7  775.36  5026.2  778.36
  5028.8  778.37  5053.3  794.76  5078.2  808.16  5086.4  812.11  5099.8  816.61
#Mann= 3 ,-1 , 0
  4595.4     .14       0  4973.8    .045       0  5026.2     .14       0
Bank Sta=4973.8,5026.2
Exp/Cntr=0.3,0.1

Type RM Length L Ch R = 1 ,19795   ,161,161,161
BEGIN DESCRIPTION:
North Deep Creek 55.0
END DESCRIPTION:
XS GIS Cut Line= 4
      1529331.98       868529.74      1529193.82       868555.19
      1529008.36       868533.38      1528848.39       868500.66
#Sta/Elev= 30
  4844.8  808.22  4873.5   802.6  4907.1  795.27  4933.9  784.45  4963.1   781.2
  4966.7   779.1  4966.9  778.03  4979.8  775.03  5020.2  775.03  5021.4  778.03
  5031.3  783.43  5056.5  785.28  5069.2  784.89  5077.3  783.78  5105.9  784.78
  5127.6  782.97  5143.8  783.05    5172  781.53  5175.4  781.28  5185.6  779.16
  5196.4  779.63  5201.1  780.07    5206   782.1  5212.8  787.17  5224.8  788.05
  5236.4  790.74  5272.4  795.49  5288.2  796.45  5319.5  802.02  5335.3  806.02
#Mann= 3 ,-1 , 0
  4844.8     .14       0  4966.9    .045       0  5021.4     .14       0
Bank Sta=4966.9,5021.4
Exp/Cntr=0.3,0.1

Type RM Length L Ch R = 1 ,19634   ,197,197,197
BEGIN DESCRIPTION:
North Deep Creek 54.0
END DESCRIPTION:
XS GIS Cut Line= 4
      1529277.42       868340.67      1529099.27       868453.38
      1528997.45        868486.1      1528862.95        868475.2
#Sta/Elev= 30
  4889.8  828.86  4906.4   823.9  4911.7  821.83  4939.6  804.24  4946.2  801.59
  4954.3  797.31  4974.9  779.32  4977.4  777.95  4978.6  777.94  4979.8  774.94
  5020.2  774.94    5031  777.95  5033.5  784.47  5033.8  784.74  5047.1  783.89
  5061.7  783.61  5091.1  783.52  5122.3  784.11  5143.2   782.9  5160.7  783.42
  5167.4  782.59  5185.2   778.6  5203.8  780.49  5218.8  783.57  5231.6   786.8
    5243  788.29  5274.6   789.7  5295.7  792.05  5333.1  798.31  5342.5  800.61
#Mann= 3 ,-1 , 0
  4889.8     .14       0  4978.6    .045       0    5031     .14       0
Bank Sta=4978.6,5031
Exp/Cntr=0.3,0.1

Type RM Length L Ch R = 1 ,19437   ,192,192,192
BEGIN DESCRIPTION:
North Deep Creek 53.0
END DESCRIPTION:
XS GIS Cut Line= 3
      1529062.92       868235.17      1528961.09       868424.29
      1528870.16       868446.11
#Sta/Elev= 26
  4857.4  825.61  4885.4  822.01  4889.1  820.85  4964.2  784.47  4968.7  782.44
  4976.5  779.64  4980.5  777.79  4987.4  774.78  5012.7  774.78  5013.4  777.78
  5013.8  777.78  5014.4  778.93  5017.6  779.66  5022.9   779.5  5031.6  778.98
    5045  779.17    5047  779.43  5072.2  784.25  5083.7  784.74  5097.6  786.46
  5102.9  786.54  5111.1  786.39  5121.9  788.78  5152.3   794.1  5163.3  796.17
  5165.7  796.77
#Mann= 3 ,-1 , 0
  4857.4     .14       0  4980.5    .045       0  5013.4     .14       0
Bank Sta=4980.5,5013.4
Exp/Cntr=0.3,0.1

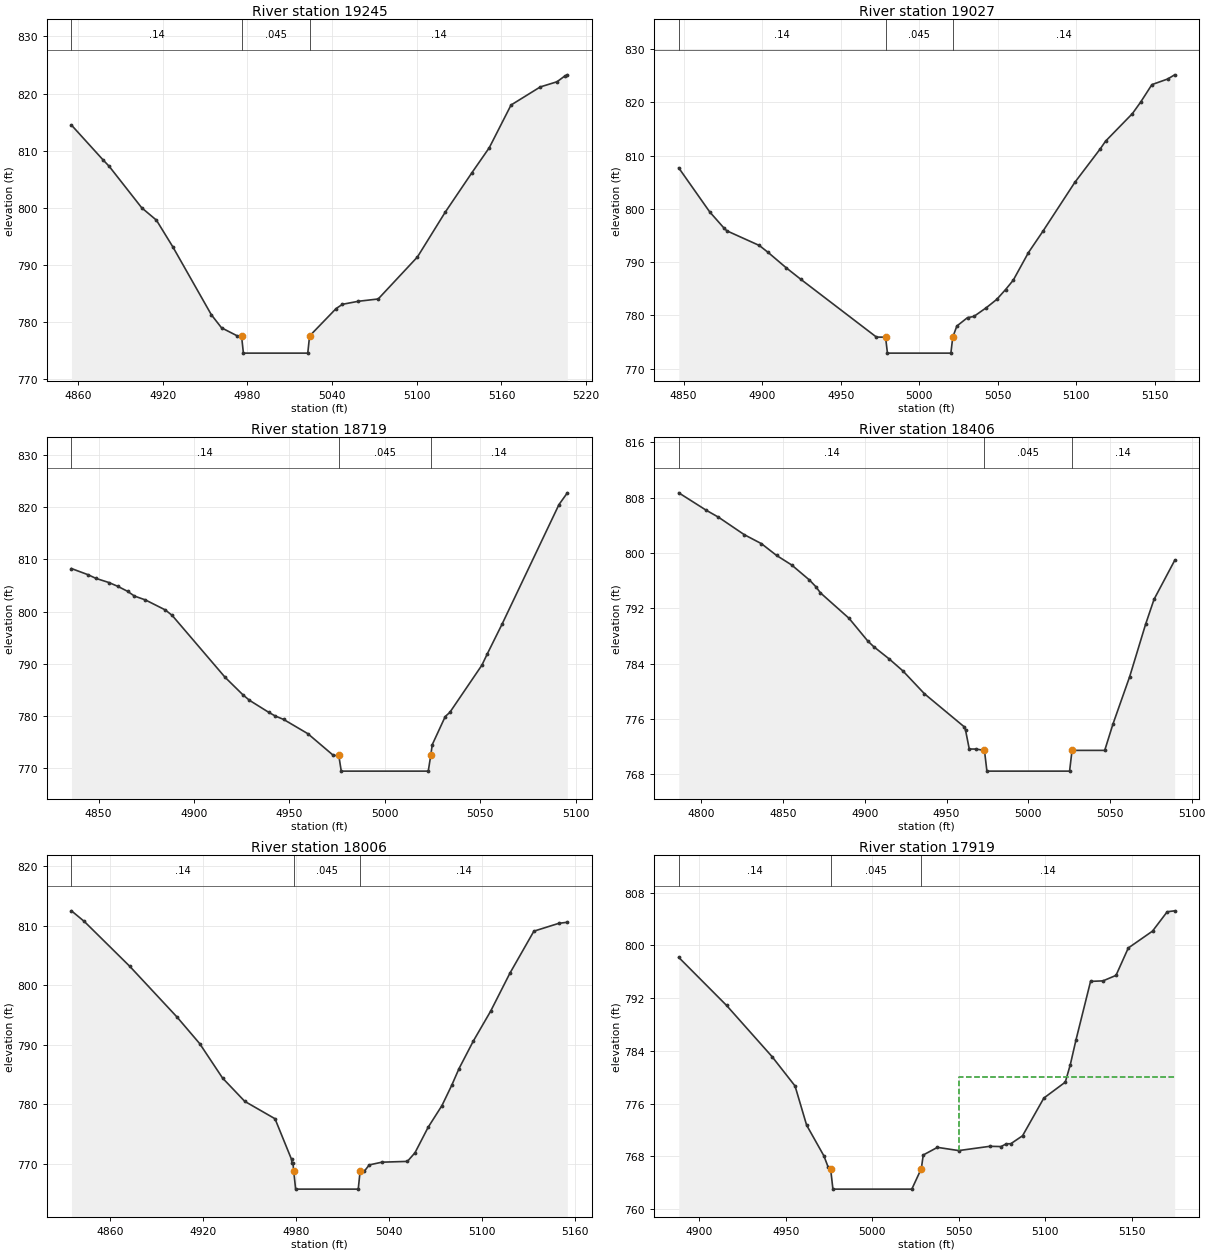
Type RM Length L Ch R = 1 ,19245   ,218,218,218
BEGIN DESCRIPTION:
North Deep Creek 52.0
END DESCRIPTION:
XS GIS Cut Line= 3
      1529015.68       868191.55      1528913.82       868202.47
      1528691.96       868315.21
#Sta/Elev= 26
  4855.4  814.49  4877.9  808.37  4882.1  807.29  4905.2  800.02  4915.6  797.86
  4927.2   793.2  4954.5  781.32  4961.7  779.04    4973  777.61  4975.9  777.61
  4977.2  774.61  5022.8  774.61  5024.1  777.61  5042.9  782.41  5047.4  783.15
  5058.7  783.68  5072.7  784.08  5100.5  791.43  5120.1  799.23  5138.8  806.06
  5151.4  810.54  5166.8     818  5187.5  821.16  5199.4  822.07  5204.7  823.04
  5206.7  823.28
#Mann= 3 ,-1 , 0
  4855.4     .14       0  4975.9    .045       0  5024.1     .14       0
Bank Sta=4975.9,5024.1
Exp/Cntr=0.3,0.1

Type RM Length L Ch R = 1 ,19027   ,308,308,308
BEGIN DESCRIPTION:
North Deep Creek 51.0
END DESCRIPTION:
XS GIS Cut Line= 3
      1529001.07       868031.55        1528892.        868006.1
      1528688.33       868013.37
#Sta/Elev= 30
  4846.9   807.7  4866.6  799.44  4875.8  796.37  4877.6  795.87  4898.2  793.13
  4903.8  791.83  4915.4  788.92  4924.7  786.76  4972.8  775.92  4978.6  775.91
  4979.8  772.91  5020.2  772.91  5021.4  775.91    5024     778  5030.8  779.58
  5034.8  779.79  5042.8  781.45  5049.4     783    5055  784.84  5059.9   786.6
  5069.6   791.8  5078.8   795.8  5099.1  804.97  5115.4  811.31  5118.7  812.72
  5135.8   817.9  5141.1  820.08  5148.2  823.34  5158.2  824.39  5162.7  825.18
#Mann= 3 ,-1 , 0
  4846.9     .14       0  4978.6    .045       0  5021.4     .14       0
Bank Sta=4978.6,5021.4
Exp/Cntr=0.3,0.1

Type RM Length L Ch R = 1 ,18719   ,313,313,313
BEGIN DESCRIPTION:
North Deep Creek 50.0
END DESCRIPTION:
XS GIS Cut Line= 2
      1529099.32       867766.11      1528852.04       867686.11
#Sta/Elev= 30
  4835.8  808.22  4844.5  807.04  4848.7  806.33  4855.4  805.55    4860  804.83
  4865.2  803.87  4868.8  802.96  4874.6  802.21    4885   800.3  4888.6  799.25
  4916.3  787.42  4925.7  784.05  4929.1  783.01  4939.2  780.71  4942.7  779.99
    4947  779.35  4959.7  776.62  4973.1  772.46  4975.9  772.46  4977.2  769.46
  5022.8  769.46  5024.1  772.46  5024.9  774.53  5031.7  779.91  5034.1   780.7
  5050.9  789.73  5053.8  791.94  5061.5   797.6  5091.3  820.46  5095.7  822.71
#Mann= 3 ,-1 , 0
  4835.8     .14       0  4975.9    .045       0  5024.1     .14       0
Bank Sta=4975.9,5024.1
Exp/Cntr=0.3,0.1

Type RM Length L Ch R = 1 ,18406   ,400,400,400
BEGIN DESCRIPTION:
North Deep Creek 49.0
END DESCRIPTION:
XS GIS Cut Line= 4
      1529168.37       867722.49      1529153.82       867580.64
      1529153.82       867493.37      1529193.82       867431.55
#Sta/Elev= 30
  4786.1  808.72    4803  806.19  4810.4   805.2  4826.2  802.67  4836.7  801.37
    4846  799.66  4855.2  798.29  4866.1  796.11    4870  795.15  4872.8  794.26
  4890.3  790.58  4901.8  787.29  4905.5  786.46  4914.8  784.72  4923.2  782.99
  4936.5  779.66  4960.8  774.89  4961.6  774.43  4963.9  771.68    4968  771.67
  4973.2  771.48  4974.7  768.48  5025.3  768.48  5026.8  771.48  5046.8  771.48
  5051.8  775.26  5062.1  782.16  5071.8   789.7    5077  793.33  5089.6  798.94
#Mann= 3 ,-1 , 0
  4786.1     .14       0  4973.2    .045       0  5026.8     .14       0
Bank Sta=4973.2,5026.8
Exp/Cntr=0.3,0.1

Type RM Length L Ch R = 1 ,18006   ,87,87,87
BEGIN DESCRIPTION:
North Deep Creek 48.0
END DESCRIPTION:
XS GIS Cut Line= 4
      1529284.71       867809.75      1529393.82       867749.74
      1529473.82       867738.83      1529577.42       867689.75
#Sta/Elev= 30
  4835.2  812.47  4843.5  810.68  4872.9  803.12  4903.3  794.62  4917.9  790.16
  4932.7  784.36    4947  780.45  4966.5  777.53  4977.2  770.68  4977.4  770.06
  4978.1  770.05  4978.6   768.7  4979.8   765.7  5020.2   765.7  5021.4   768.7
  5024.1   768.7  5027.3  769.77  5035.5  770.23  5051.9  770.36  5056.8  771.81
  5065.3   776.1  5074.2  779.74  5080.5  783.15  5085.2  785.95  5094.4  790.57
  5105.6   795.6    5118  801.97  5133.5  809.05  5149.6  810.37  5155.1  810.55
#Mann= 3 ,-1 , 0
  4835.2     .14       0  4978.6    .045       0  5021.4     .14       0
Bank Sta=4978.6,5021.4
Exp/Cntr=0.3,0.1

Type RM Length L Ch R = 1 ,17919   ,61,61,61
BEGIN DESCRIPTION:
North Deep Creek 47.5
END DESCRIPTION:
XS GIS Cut Line= 4
      1529333.48       867868.11        1529403.       867838.62
      1529491.47       867819.66      1529600.98       867769.12
#Sta/Elev= 30
  4888.1  798.18  4915.7   790.9    4942  783.13  4955.3  778.67    4962  772.72
    4972  768.05  4974.5  766.31  4975.9  766.01  4977.2  763.01  5022.8  763.01
  5028.3  766.13  5029.4  768.19  5037.6  769.35  5049.9  768.86  5067.9  769.51
  5074.4  769.47  5077.4  769.89    5080   769.9  5086.8  771.11  5099.1  776.83
  5111.5  779.25  5114.4  781.91  5117.7  785.68  5126.1  794.54  5133.3  794.62
  5140.8  795.45  5147.9  799.61  5161.9  802.17  5170.4  805.11  5174.7  805.25
#Mann= 3 ,-1 , 0
  4888.1     .14       0  4975.9    .045       0  5028.3     .14       0
#XS Ineff= 2 , 0
       0                    5050       0     780
Permanent Ineff=
       F       F
Bank Sta=4975.9,5028.3
Exp/Cntr=0.3,0.1

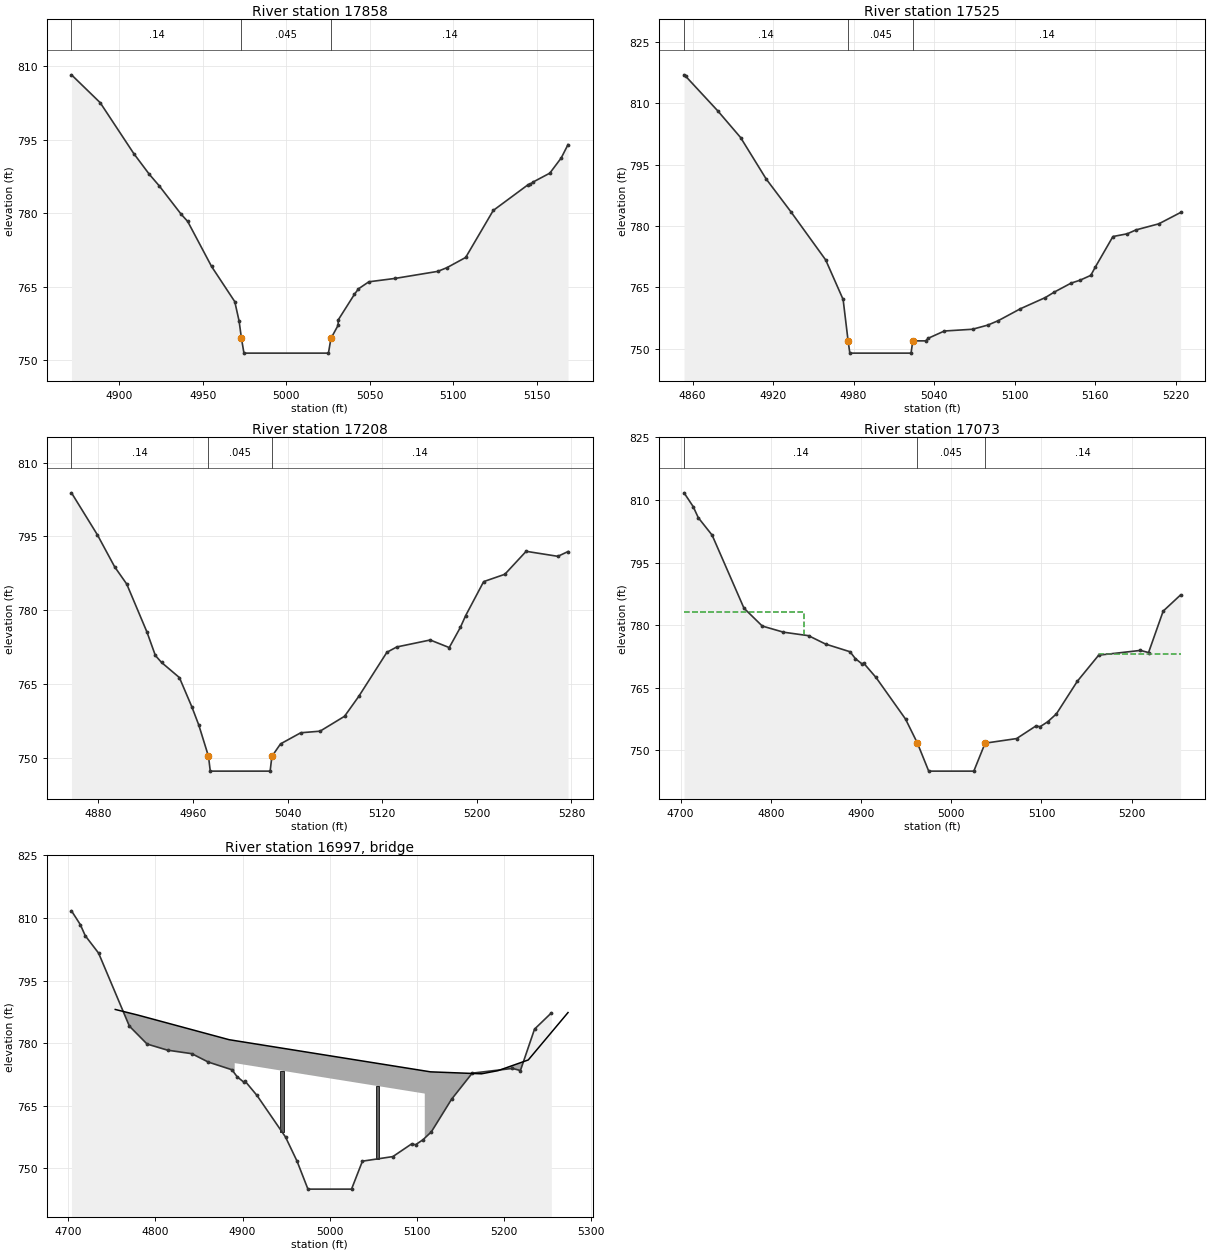
Type RM Length L Ch R = 1 ,17858   ,333,333,333
BEGIN DESCRIPTION:
North Deep Creek 47.0
END DESCRIPTION:
XS GIS Cut Line= 5
        1529327.        867924.9      1529408.65       867905.91
      1529490.89       867876.18      1529531.38       867842.02
      1529599.03        867814.2
#Sta/Elev= 30
  4871.4  808.25  4888.6  802.56  4908.7  792.18    4918  787.95    4924  785.57
    4937  779.83    4941  778.32  4955.3  769.13  4969.2  761.95  4971.8  757.97
  4973.2  754.44  4974.7  751.44  5025.3  751.44  5026.8  754.44  5031.1  757.13
  5031.2  758.24  5040.8  763.41  5043.3  764.57  5049.5     766  5065.4   766.7
  5090.8  768.13  5096.3  768.89  5107.5  770.97    5124  780.56    5145  785.85
  5146.3  785.94    5148  786.39  5157.9  788.18  5164.7  791.27  5168.8  794.01
#Mann= 3 ,-1 , 0
  4871.4     .14       0  4973.2    .045       0  5026.8     .14       0
Bank Sta=4973.2,5026.8
Exp/Cntr=0.3,0.1

Type RM Length L Ch R = 1 ,17525   ,317,317,317
BEGIN DESCRIPTION:
North Deep Creek 46.0
END DESCRIPTION:
XS GIS Cut Line= 4
      1529448.35       868289.75      1529528.36       868220.65
      1529642.91       868162.47      1529753.82       868084.28
#Sta/Elev= 30
  4853.7  817.01  4854.8   816.7  4878.8   808.2  4895.8  801.68  4914.9  791.52
  4933.3  783.51  4959.2  771.74  4972.2  762.06  4975.9  751.94  4977.2  748.94
  5022.8  748.94  5024.1  751.94  5033.6  751.94  5035.7  752.59  5047.6  754.35
  5068.6  754.78    5080   755.8  5087.9   756.9  5104.3   759.8  5122.9  762.54
  5129.4  763.85    5142  766.06  5148.7  766.78  5156.7  767.96  5159.9  769.89
  5173.2  777.46  5183.9  778.13  5190.4  779.08  5207.4  780.57  5223.6  783.34
#Mann= 3 ,-1 , 0
  4853.7     .14       0  4975.9    .045       0  5024.1     .14       0
Bank Sta=4975.9,5024.1
Exp/Cntr=0.3,0.1

Type RM Length L Ch R = 1 ,17208   ,135,135,135
BEGIN DESCRIPTION:
North Deep Creek 45.0
END DESCRIPTION:
XS GIS Cut Line= 4
      1529699.26       868560.69      1529744.73       868469.74
      1529879.28       868309.74      1529970.22       868249.72
#Sta/Elev= 30
  4857.4  803.86  4879.3  795.32  4893.9  788.81  4904.1  785.31  4921.2  775.55
  4928.3  770.79  4933.5  769.38  4948.6   766.3  4959.1  760.37    4965  756.65
  4973.2  750.28  4974.7  747.28  5025.3  747.28  5026.8  750.28  5034.1  752.82
  5051.2  755.08  5067.5   755.4  5088.2  758.43  5100.2  762.47    5124  771.44
  5132.3  772.52  5160.6  773.94  5176.7   772.4  5186.1   776.5  5190.6  778.91
  5205.8  785.81  5223.7   787.3  5241.7  791.97  5268.5  790.95  5277.1  791.92
#Mann= 3 ,-1 , 0
  4857.4     .14       0  4973.2    .045       0  5026.8     .14       0
Bank Sta=4973.2,5026.8
Exp/Cntr=0.5,0.3

Type RM Length L Ch R = 1 ,17073   ,127,127,127
BEGIN DESCRIPTION:
Styers Mill Rd (NDC) us
END DESCRIPTION:
XS GIS Cut Line= 5
      1529907.63       868763.73      1529966.77       868721.49
      1529840.05       868416.31      1529878.06       868340.28
      1529924.73       868299.04
#Sta/Elev= 30
  4703.8   811.7  4713.9   808.4  4719.6  805.73  4734.9  801.56  4770.2  784.06
  4790.5  779.77    4814   778.3  4841.8  777.46  4860.7  775.45  4887.8  773.61
  4893.7  771.96  4901.3  770.66  4902.9  770.88  4916.6  767.44  4949.3  757.48
  4962.5   751.7    4975     745    5025     745  5037.5   751.7  5072.4   752.8
  5093.8  755.82  5098.5  755.65  5106.9  756.83  5116.5  758.71  5139.7  766.53
  5163.4  772.79  5209.6  773.93  5218.7  773.42  5234.9  783.35  5254.2  787.23
#Mann= 3 ,-1 , 0
  4703.8     .14       0  4962.5    .045       0  5037.5     .14       0
#XS Ineff= 2 , 0
       0  4836.5  783.06  5163.5       0  772.99
Permanent Ineff=
       F       F
Bank Sta=4962.5,5037.5
Exp/Cntr=0.5,0.3

Type RM Length L Ch R = 3 ,16997   ,,,
BEGIN DESCRIPTION:
Styers Mill Rd (NDC) tor
Structure ID: LDS_NDC_04
Approximate Survey Structure
END DESCRIPTION:
Bridge Culvert--1,0,-1,-1, 0
Deck Dist Width WeirC Skew NumUp NumDn MinLoCord MaxHiCord MaxSubmerge Is_Ogee
54.5,43,3,0, 12, 12, , , 0.95, 0, 1,1,,
    4754  4780.2  4884.5    4891    4891    5109    5109  5115.6  5174.1  5193.1
  5227.7  5273.3
  788.06   786.7  780.82   780.6   780.6  773.33  773.33  773.11  772.64   773.4
  775.96  787.32
     725     725     725     725   775.2   767.9     725     725     725     725
     725     725
    4754  4780.2  4884.5    4891    4891    5109    5109  5115.6  5174.1  5193.1
  5227.7  5273.3
  788.06   786.7  780.82   780.6   780.6  773.33  773.33  773.11  772.64   773.4
  775.96  787.32
     725     725     725     725   775.2   767.9     725     725     725     725
     725     725
Pier Skew, UpSta & Num, DnSta & Num=  ,4945.5, 2 ,4945.5, 2 , 0 , 0 , 0 ,0,0
       4       4
   758.3     775
       4       4
  759.29     775
Pier Skew, UpSta & Num, DnSta & Num=  ,5054.5, 2 ,5054.5, 2 , 0 , 0 , 0 ,0,0
       4       4
  750.75     772
       4       4
  753.45     772
Abutment Skew #Up #Dn= , 2 , 2
    4891    4923
   775.2   765.4
    4891    4923
   775.2  768.66
Abutment Skew #Up #Dn= , 2 , 2
    5077    5109
  753.69   767.9
    5077    5109
  752.84  767.89
BR Coef= 1 , 1 , 0 ,1.25, 0 ,,,0.8,0,2,0,
WSPro=,,,, 1 ,,,, 0 ,,,, 0 ,,,,-1 ,-1 ,-1 , 0 , 0 , 0 , 0 , 0
BC Design=,, 0 ,, 0 ,,,,,,
BC HTab HWMax=811.7