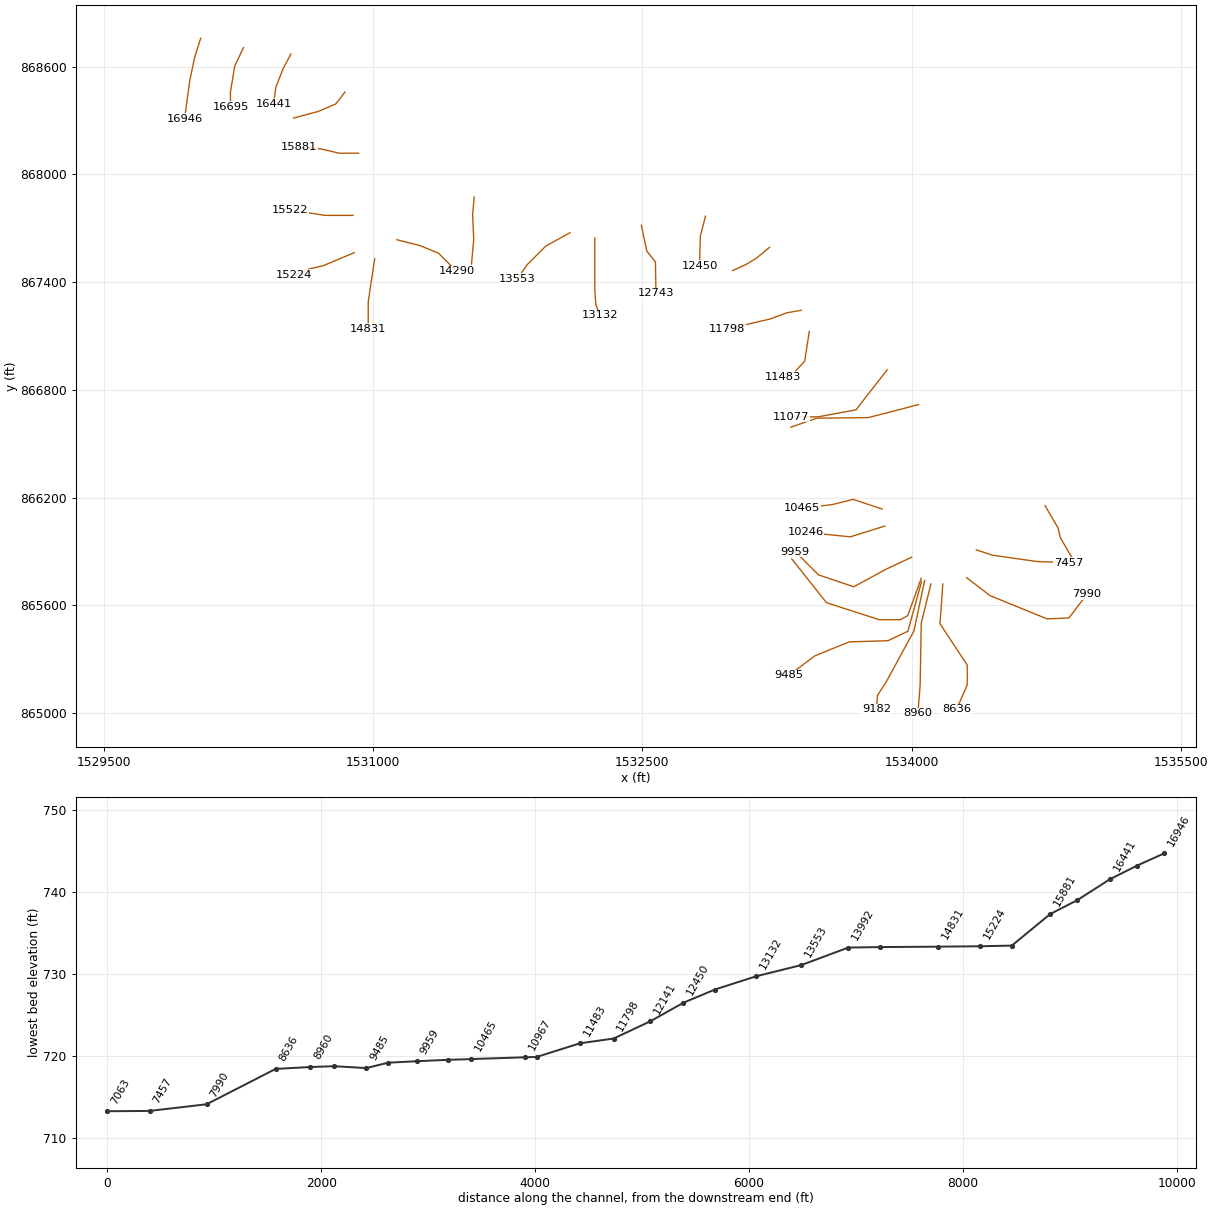
HEC-RAS study North Deep Creek.prj: North Deep Creek Limited Detail Study

--- North Deep Creek.g01 (geometry) --- (continued)

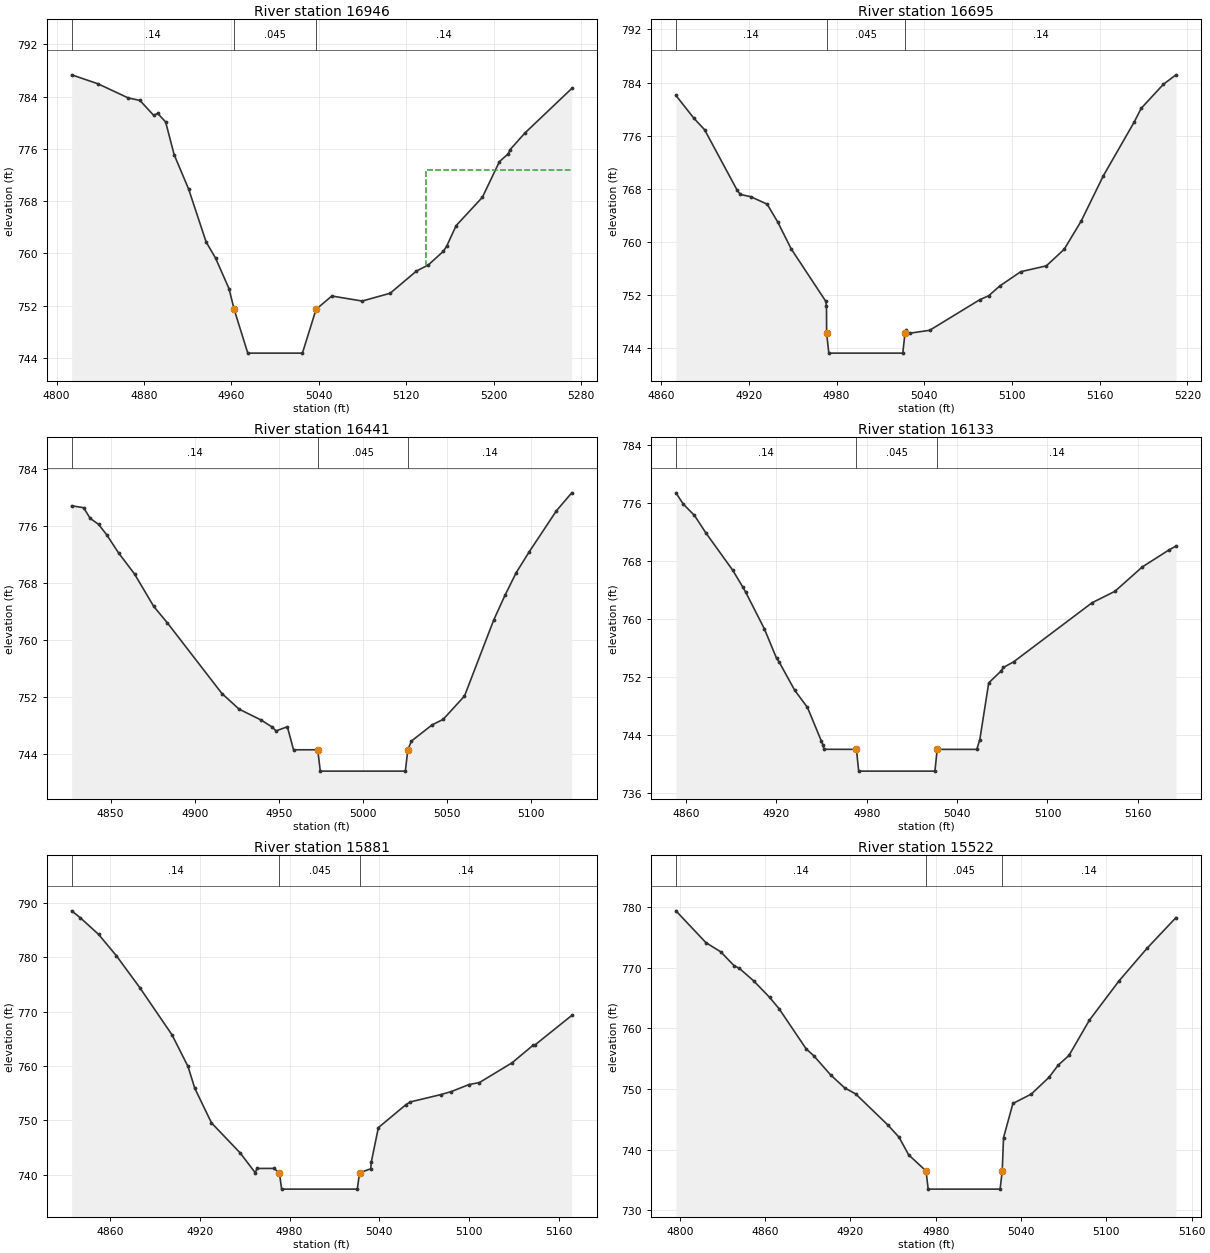
Type RM Length L Ch R = 1 ,16946   ,251,251,251
BEGIN DESCRIPTION:
Styers Mill Rd (NDC) ds
END DESCRIPTION:
XS GIS Cut Line= 4
      1530040.68       868757.37      1530006.97       868650.96
      1529979.87       868521.48      1529950.93       868309.65
#Sta/Elev= 30
  4813.8  787.33  4837.7  785.97  4865.5   783.8  4876.3  783.41  4888.9  781.12
  4892.5  781.44  4899.8  780.12  4907.6  775.11  4920.8  769.87  4936.9  761.74
  4945.5  759.29  4957.8  754.62  4962.5  751.45    4975  744.75    5025  744.75
  5037.5  751.45  5051.9  753.49  5079.7  752.72  5105.3  753.91  5129.3   757.3
  5140.2  758.24    5154  760.33    5157   761.1  5165.7  764.26  5189.7  768.59
  5205.3  774.05  5213.4  775.25    5215  775.87  5228.6  778.42  5271.5  785.24
#Mann= 3 ,-1 , 0
  4813.8     .14       0  4962.5    .045       0  5037.5     .14       0
#XS Ineff= 2 , 0
       0  4861.5  782.07  5138.5       0  772.76
Permanent Ineff=
       F       F
Bank Sta=4962.5,5037.5
Exp/Cntr=0.5,0.3

Type RM Length L Ch R = 1 ,16695   ,254,254,254
BEGIN DESCRIPTION:
North Deep Creek 44.0
END DESCRIPTION:
XS GIS Cut Line= 4
      1530279.28       868706.12      1530230.19       868602.47
      1530206.55       868458.83      1530206.55       868376.99
#Sta/Elev= 30
  4870.1  782.07  4882.4  778.63  4889.7  776.91    4912  767.79  4914.2  767.16
  4921.3  766.82  4932.5   765.7  4939.7  763.03    4949  758.95  4972.6  751.08
  4973.1  750.32  4973.2  746.27  4974.7  743.27  5025.3  743.27  5026.8  746.27
  5027.6  746.72  5030.1  746.27  5043.7  746.71    5078  751.32    5084   751.9
  5091.6  753.37    5106  755.53  5123.5  756.41  5135.7   758.9  5147.3  763.14
  5162.5  769.97  5183.6  778.06  5188.4  780.13  5203.6  783.75  5212.2  785.17
#Mann= 3 ,-1 , 0
  4870.1     .14       0  4973.2    .045       0  5026.8     .14       0
Bank Sta=4973.2,5026.8
Exp/Cntr=0.3,0.1

Type RM Length L Ch R = 1 ,16441   ,308,308,308
BEGIN DESCRIPTION:
North Deep Creek 43.0
END DESCRIPTION:
XS GIS Cut Line= 4
      1530542.93       868669.78       1530501.1       868591.56
      1530459.28        868486.1      1530446.56        868391.6
#Sta/Elev= 30
  4826.8  778.89  4833.9  778.62  4837.8  777.13  4842.8  776.28  4847.6  774.83
  4854.7  772.27  4864.2  769.31  4875.6  764.76  4883.8  762.42  4916.2  752.51
  4926.4  750.32  4939.5  748.79  4946.1   747.8  4948.4  747.26  4955.1  747.85
  4958.8  744.61  4973.2  744.61  4974.7  741.61  5025.3  741.61  5026.8  744.61
  5028.9  745.83  5041.3  748.12  5047.8  748.88  5060.5  752.16  5077.9  762.85
  5084.6  766.32  5091.3  769.51  5099.1  772.46  5115.2  778.19  5124.3  780.71
#Mann= 3 ,-1 , 0
  4826.8     .14       0  4973.2    .045       0  5026.8     .14       0
Bank Sta=4973.2,5026.8
Exp/Cntr=0.3,0.1

Type RM Length L Ch R = 1 ,16133   ,252,252,252
BEGIN DESCRIPTION:
North Deep Creek 42.0
END DESCRIPTION:
XS GIS Cut Line= 4
      1530844.09       868458.27      1530792.88         868392.
      1530693.51       868349.85      1530558.04       868313.72
#Sta/Elev= 30
  4853.4  777.39  4858.3  775.83  4865.7  774.28  4873.1  771.92  4891.2  766.69
  4897.9  764.36  4899.7   763.7  4912.1  758.64  4920.2  754.58  4921.9  754.08
  4932.2  750.19  4940.7  747.81  4949.9  743.19  4950.9  742.66  4951.8  742.04
  4973.2  742.03  4974.7  739.03  5025.3  739.03  5026.8  742.03  5053.1  742.03
  5055.1  743.38    5061  751.19  5069.1  752.81  5070.8  753.33  5077.5  754.09
  5129.6  762.24  5144.8  763.82  5162.9  767.17  5180.5   769.5  5185.3  770.05
#Mann= 3 ,-1 , 0
  4853.4     .14       0  4973.2    .045       0  5026.8     .14       0
Bank Sta=4973.2,5026.8
Exp/Cntr=0.3,0.1

Type RM Length L Ch R = 1 ,15881   ,359,359,359
BEGIN DESCRIPTION:
North Deep Creek 41.0
END DESCRIPTION:
XS GIS Cut Line= 4
      1530919.39       868117.99      1530810.94       868117.99
      1530708.56       868142.08      1530588.13       868151.11
#Sta/Elev= 30
  4834.3  788.52  4840.1  787.24  4852.3  784.19  4864.2  780.26  4879.8  774.42
  4901.4  765.72  4912.1   759.9  4916.6  755.91  4927.8  749.53    4947     744
  4957.1  740.35  4958.2  741.15  4969.5  741.16  4973.2  740.35  4974.7  737.35
  5025.3  737.35  5026.8  740.35  5034.3  741.09  5034.7  742.37  5039.4  748.66
  5057.9   752.9  5060.7  753.38  5081.3  754.74  5088.2  755.29    5100  756.58
    5107  756.95  5128.8  760.58  5142.7  763.77  5144.2  763.88  5168.7  769.28
#Mann= 3 ,-1 , 0
  4834.3     .14       0  4973.2    .045       0  5026.8     .14       0
Bank Sta=4973.2,5026.8
Exp/Cntr=0.3,0.1

Type RM Length L Ch R = 1 ,15522   ,298,298,298
BEGIN DESCRIPTION:
North Deep Creek 40.0
END DESCRIPTION:
XS GIS Cut Line= 3
      1530889.26       867771.71      1530732.65       867771.71
       1530539.9       867801.83
#Sta/Elev= 30
  4797.3  779.41  4818.4  774.16  4828.8  772.65  4838.2  770.36  4841.9  769.92
    4852  767.85  4863.2  765.13  4869.9  763.24  4888.9  756.63  4894.2  755.51
  4906.1  752.34    4916  750.19  4923.7   749.2  4946.2  744.11  4954.2  742.06
    4961  739.14  4973.2  736.49  4974.7  733.49  5025.3  733.49  5026.8  736.49
  5027.7  741.97  5034.3  747.62  5047.2  749.17  5059.7  751.94  5066.2  753.96
  5073.7  755.54  5088.1  761.37    5109  767.87  5128.6  773.22    5149   778.3
#Mann= 3 ,-1 , 0
  4797.3     .14       0  4973.2    .045       0  5026.8     .14       0
Bank Sta=4973.2,5026.8
Exp/Cntr=0.3,0.1

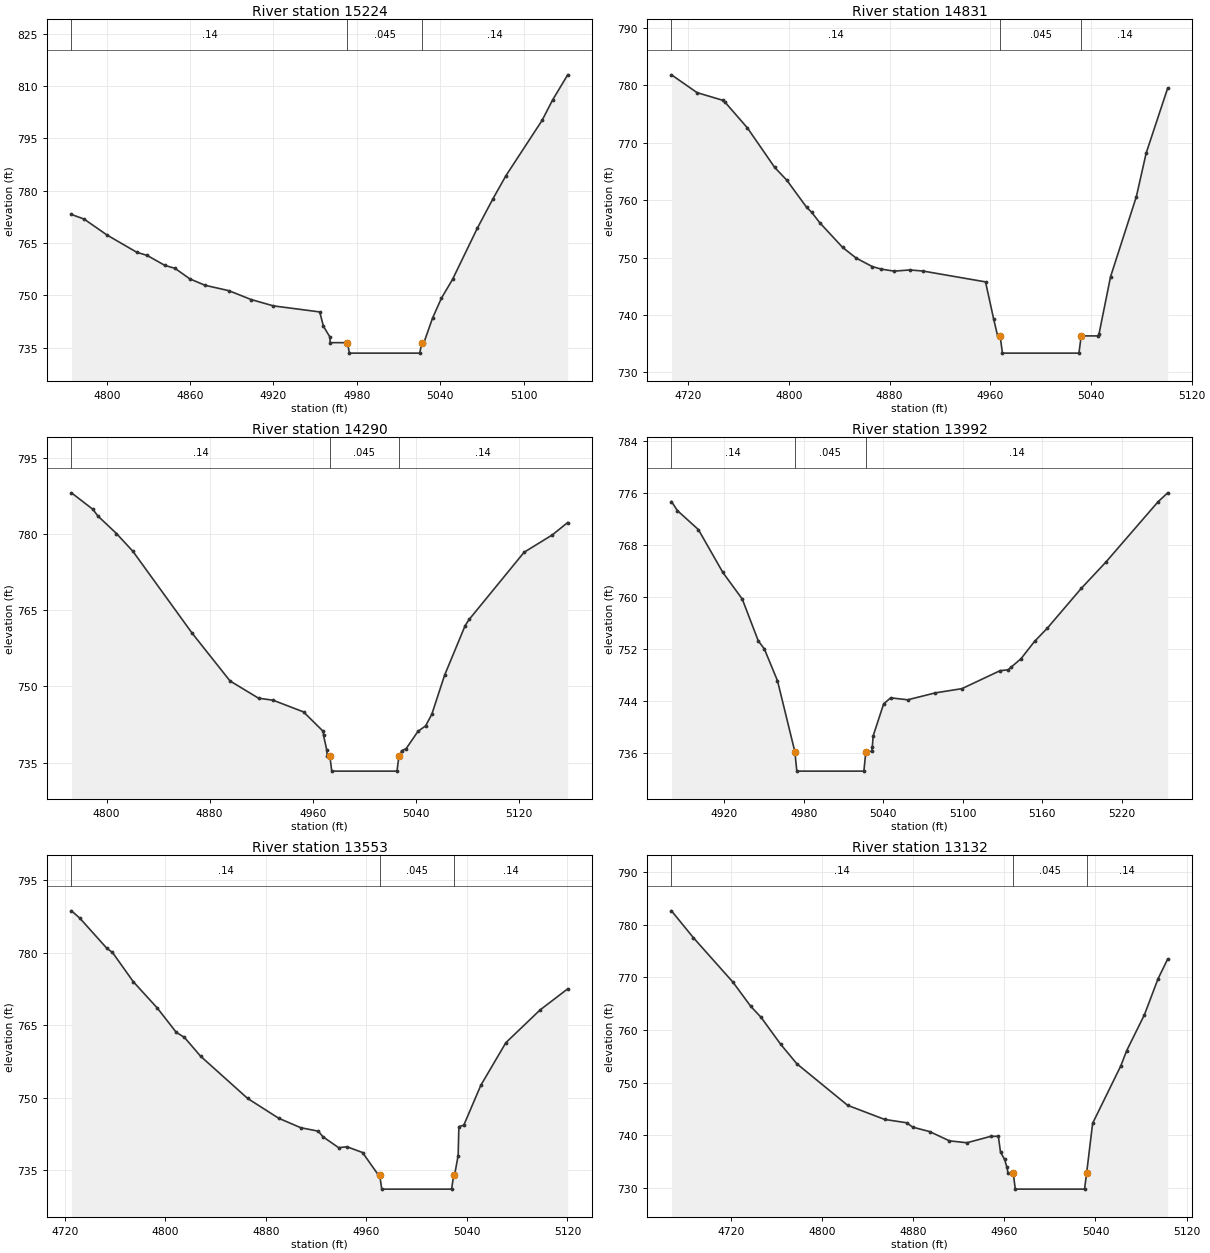
Type RM Length L Ch R = 1 ,15224   ,393,393,393
BEGIN DESCRIPTION:
North Deep Creek 39.0
END DESCRIPTION:
XS GIS Cut Line= 4
      1530895.25       867563.93      1530723.62       867491.67
      1530645.33        867473.6      1530560.97       867440.46
#Sta/Elev= 30
  4774.6  773.19  4783.7  771.87  4800.3  767.27  4821.6  762.35  4829.1  761.44
  4841.8  758.59  4849.1  757.74  4859.8  754.72  4870.7  752.88  4887.9  751.33
  4903.9  748.79  4919.9  746.97  4953.3  745.23    4956   741.1  4960.6  738.06
  4960.8  736.42  4973.2  736.41  4974.7  733.41  5025.3  733.41  5026.8  736.41
  5028.3  736.41  5034.5  743.44  5040.9  749.17  5048.9  754.56  5066.8  769.29
  5078.1  777.77  5087.4  784.35  5113.4  800.21  5120.9  806.01  5131.8  813.26
#Mann= 3 ,-1 , 0
  4774.6     .14       0  4973.2    .045       0  5026.8     .14       0
Bank Sta=4973.2,5026.8
Exp/Cntr=0.3,0.1

Type RM Length L Ch R = 1 ,14831   ,541,541,541
BEGIN DESCRIPTION:
North Deep Creek 38.0
END DESCRIPTION:
XS GIS Cut Line= 3
      1531009.68       867530.85      1530973.55       867289.92
      1530973.55       867139.34
#Sta/Elev= 30
  4706.7  781.84    4727  778.74  4747.5   777.4  4748.9  777.16    4767   772.6
  4788.7  765.71  4798.3  763.49    4814  758.78    4818  757.91  4824.6  756.05
  4842.7  751.77  4853.4  749.92  4866.3  748.43  4873.3     748  4883.6  747.64
    4896  747.85  4906.5  747.66  4956.2  745.77  4962.6  739.35  4965.8  736.36
  4967.8  736.36  4969.6  733.36  5030.4  733.36  5032.2  736.36  5045.8  736.36
  5046.4  736.76  5055.5  746.66    5076  760.61  5083.8   768.2  5100.9  779.53
#Mann= 3 ,-1 , 0
  4706.7     .14       0  4967.8    .045       0  5032.2     .14       0
Bank Sta=4967.8,5032.2
Exp/Cntr=0.3,0.1

Type RM Length L Ch R = 1 ,14290   ,298,298,298
BEGIN DESCRIPTION:
North Deep Creek 37.0
END DESCRIPTION:
XS GIS Cut Line= 4
      1531133.16        867636.2      1531262.62       867603.08
      1531364.99       867560.93      1531464.39       867461.54
#Sta/Elev= 30
  4772.8   788.1  4789.5  784.83  4793.2  783.56  4807.7  780.09  4820.5  776.57
  4866.3   760.5  4895.8  751.06  4917.9  747.67  4929.2  747.27  4952.8  744.97
  4968.1  741.13  4968.3  740.37  4970.8  737.49  4971.2  736.31  4973.2  736.31
  4974.7  733.31  5025.3  733.31  5026.8  736.31  5027.8  736.31  5028.8  737.31
  5032.4  737.74  5041.6  741.15  5047.5  742.22  5052.3   744.5  5062.2  752.18
  5078.2  761.98  5081.3  763.18  5123.9   776.4  5145.8  779.82  5157.7  782.25
#Mann= 3 ,-1 , 0
  4772.8     .14       0  4973.2    .045       0  5026.8     .14       0
Bank Sta=4973.2,5026.8
Exp/Cntr=0.3,0.1

Type RM Length L Ch R = 1 ,13992   ,439,439,439
BEGIN DESCRIPTION:
North Deep Creek 36.0
END DESCRIPTION:
XS GIS Cut Line= 4
      1531563.73        867874.1       1531554.7       867777.73
      1531560.72       867639.22      1531548.67       867500.67
#Sta/Elev= 30
  4880.1  774.63  4884.6  773.24  4900.4  770.33  4918.9  763.74  4933.5  759.67
  4945.6  753.25  4950.2     752  4960.1  747.13  4973.2  736.25  4974.7  733.25
  5025.3  733.25  5026.8  736.25  5031.3  736.29  5031.7  737.01  5032.3  738.65
  5040.2  743.56  5045.5   744.5  5058.4   744.2  5079.2  745.26  5099.3  745.91
  5128.1  748.67  5134.1   748.8  5136.4   749.2  5143.9  750.51  5154.1  753.16
  5163.6  755.16  5189.4  761.31  5207.7  765.28  5247.3  774.59  5254.6  775.97
#Mann= 3 ,-1 , 0
  4880.1     .14       0  4973.2    .045       0  5026.8     .14       0
Bank Sta=4973.2,5026.8
Exp/Cntr=0.3,0.1

Type RM Length L Ch R = 1 ,13553   ,421,421,421
BEGIN DESCRIPTION:
North Deep Creek 35.0
END DESCRIPTION:
XS GIS Cut Line= 4
      1532096.67       867675.33       1531961.2       867600.07
      1531858.82       867497.69      1531804.61       867419.39
#Sta/Elev= 30
  4725.2  788.65  4731.9  787.12  4753.4  780.89  4757.8  780.06  4774.4     774
  4793.6  768.53  4808.6  763.53  4815.1  762.49    4828  758.59  4865.4  749.87
  4890.1  745.77  4907.7  743.81  4921.7  743.09  4925.4  741.93  4937.9  739.68
  4944.5  739.87  4956.9  738.68  4969.3  734.11  4970.5  734.11  4972.2  731.11
  5027.8  731.11  5029.5  734.11  5030.3   734.2    5033  738.06  5033.6  744.03
  5037.5  744.33  5051.1   752.6    5071  761.39  5098.2  768.15  5120.2  772.52
#Mann= 3 ,-1 , 0
  4725.2     .14       0  4970.5    .045       0  5029.5     .14       0
Bank Sta=4970.5,5029.5
Exp/Cntr=0.3,0.1

Type RM Length L Ch R = 1 ,13132   ,389,389,389
BEGIN DESCRIPTION:
North Deep Creek 34.0
END DESCRIPTION:
XS GIS Cut Line= 4
      1532235.21       867645.26      1532235.21       867350.15
      1532241.24       867271.86      1532265.32       867214.66
#Sta/Elev= 30
  4667.7  782.62    4687   777.5  4721.7  769.06  4737.3  764.48  4746.4  762.38
  4763.6  757.26  4777.8  753.56  4822.4  745.67  4854.9  742.99  4874.1  742.36
  4879.6  741.52  4894.4  740.68  4911.8  738.92  4927.1  738.56  4947.9  739.77
  4954.7   739.8  4956.6  736.79  4960.2  735.38  4962.3  733.87  4963.2  732.78
  4967.8  732.75  4969.6  729.75  5030.4  729.75  5032.2  732.75  5037.5  742.26
  5062.2  753.15  5067.4  756.06    5083  762.89  5094.9  769.69  5103.4  773.46
#Mann= 3 ,-1 , 0
  4667.7     .14       0  4967.8    .045       0  5032.2     .14       0
Bank Sta=4967.8,5032.2
Exp/Cntr=0.3,0.1

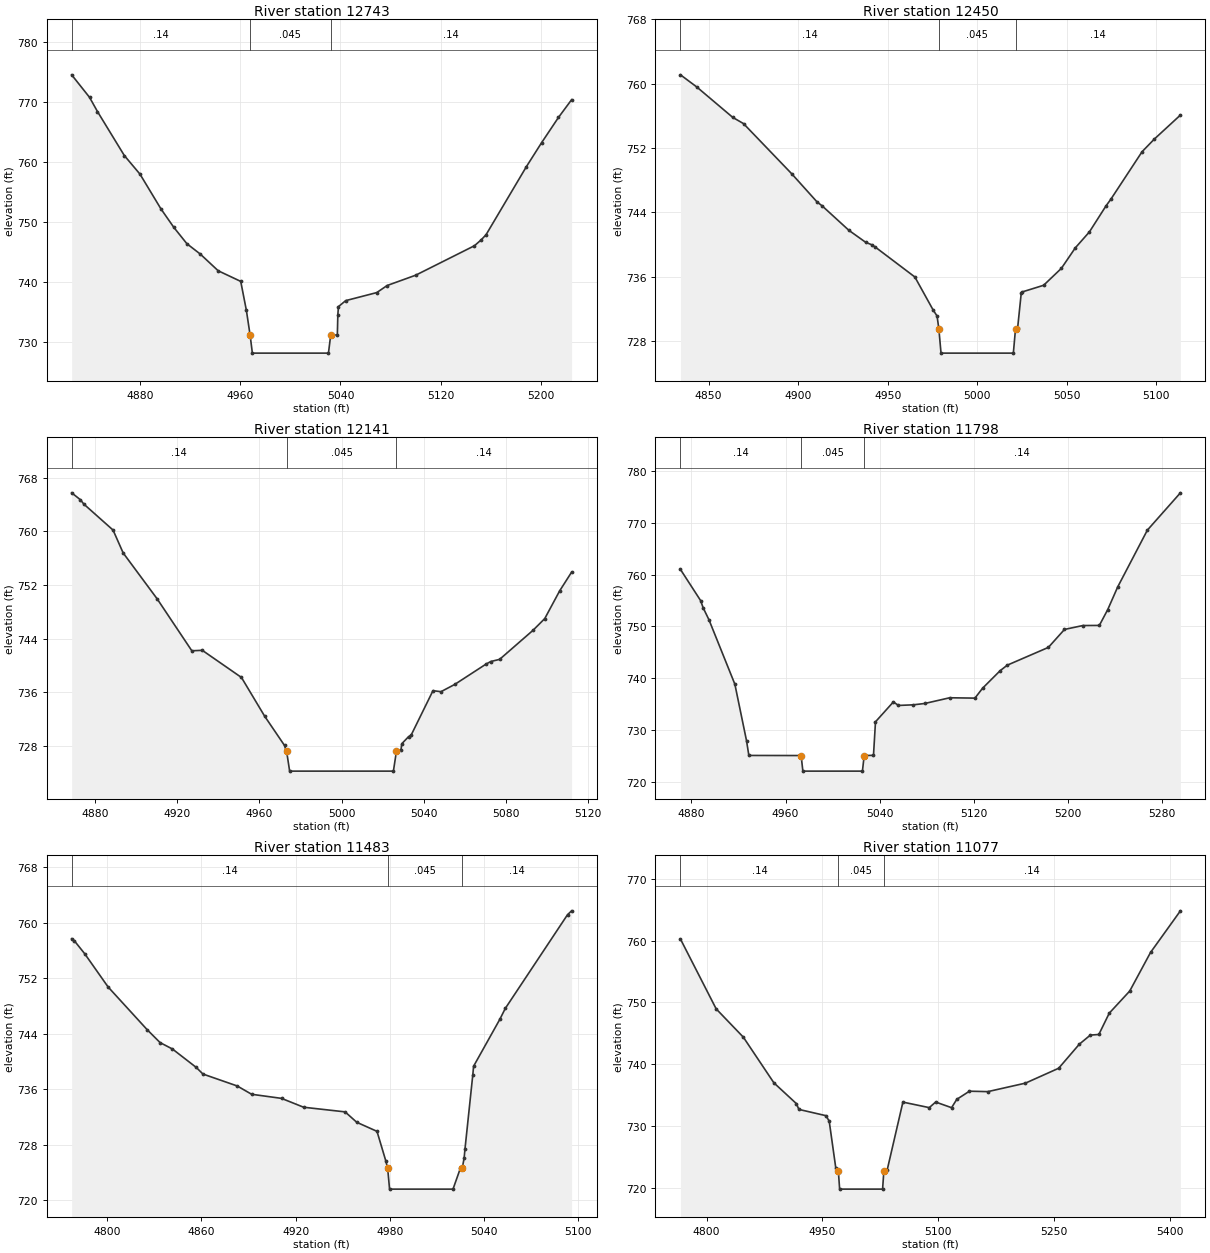
Type RM Length L Ch R = 1 ,12743   ,293,293,293
BEGIN DESCRIPTION:
North Deep Creek 33.0
END DESCRIPTION:
XS GIS Cut Line= 4
      1532494.16       867717.55      1532524.28       867572.97
      1532572.46       867512.75      1532575.47       867338.08
#Sta/Elev= 30
  4825.2  774.55  4839.5  770.79  4845.8  768.43  4867.3  761.08  4879.8  757.98
  4896.5   752.2  4906.8  749.11  4917.3  746.37  4927.9  744.66  4942.3  741.86
  4960.3  740.09  4964.8  735.28  4967.8  731.12  4969.6  728.12  5030.4  728.12
  5032.2  731.12  5037.5  731.12  5037.9  734.54  5038.4  735.88  5044.2  736.88
    5069  738.22  5077.3   739.4  5100.1  741.12  5147.1  746.04  5152.4  747.01
  5156.3  747.86  5188.6  759.24  5200.7  763.22  5214.2  767.44  5224.7   770.4
#Mann= 3 ,-1 , 0
  4825.2     .14       0  4967.8    .045       0  5032.2     .14       0
Bank Sta=4967.8,5032.2
Exp/Cntr=0.3,0.1

Type RM Length L Ch R = 1 ,12450   ,309,309,309
BEGIN DESCRIPTION:
North Deep Creek 32.0
END DESCRIPTION:
XS GIS Cut Line= 3
        1532851.       867767.22      1532822.39       867655.78
      1532817.87        867491.7
#Sta/Elev= 30
  4834.3  761.09  4843.4  759.58  4863.5   755.8  4869.5  755.03  4896.4   748.8
  4910.6  745.29  4913.4  744.81  4928.4  741.76  4937.8  740.27  4941.2  739.97
  4943.2  739.67  4965.2  735.97  4975.4  731.87  4977.6  731.12  4978.6  729.51
  4979.8  726.51  5020.2  726.51  5021.4  729.51  5022.6  729.66  5024.6  733.95
  5025.1  734.11  5037.1  734.94    5047  737.04  5054.8  739.59  5062.7  741.58
  5071.9  744.79  5074.7  745.65  5092.1  751.54  5098.9   753.1  5113.5  756.09
#Mann= 3 ,-1 , 0
  4834.3     .14       0  4978.6    .045       0  5021.4     .14       0
Bank Sta=4978.6,5021.4
Exp/Cntr=0.3,0.1

Type RM Length L Ch R = 1 ,12141   ,343,343,343
BEGIN DESCRIPTION:
North Deep Creek 31.0
END DESCRIPTION:
XS GIS Cut Line= 4
       1533207.8       867594.04      1533135.55       867533.83
      1533075.32       867497.69      1533003.04       867464.57
#Sta/Elev= 30
  4868.4  765.76  4872.7  764.72  4874.3  764.09  4888.6   760.2  4893.5   756.8
  4910.1  749.94    4927   742.2  4932.1  742.27  4951.2  738.22  4962.5  732.45
  4972.2  728.08  4972.9  727.38  4973.2  727.25  4974.7  724.25  5025.3  724.25
  5026.8  727.25    5029  727.43  5029.4  728.34  5032.7  729.39  5033.9  729.59
  5044.6  736.25  5048.5   736.1  5055.2  737.18  5070.5  740.22  5072.8   740.6
  5077.1  740.92  5093.4  745.26  5099.1     747  5106.4  751.15  5112.2  753.93
#Mann= 3 ,-1 , 0
  4868.4     .14       0  4973.2    .045       0  5026.8     .14       0
Bank Sta=4973.2,5026.8
Exp/Cntr=0.3,0.1

Type RM Length L Ch R = 1 ,11798   ,315,315,315
BEGIN DESCRIPTION:
North Deep Creek 30.0
END DESCRIPTION:
XS GIS Cut Line= 4
      1533383.94       867243.25      1533305.68        867229.7
      1533212.33       867195.07      1532972.92       867139.36
#Sta/Elev= 30
  4870.7  760.98  4887.8  754.99    4890  753.58  4894.9  751.29  4916.9  738.89
  4926.8  728.02  4928.8  725.16  4973.2  725.14  4974.7  722.14  5025.3  722.14
  5026.8  725.14  5034.7  725.18  5036.4  731.64  5051.6  735.47  5055.9  734.79
  5068.6  734.91  5078.3  735.17  5099.5  736.27  5120.9   736.2  5127.4  738.11
  5142.3  741.48  5148.4  742.55  5183.3  745.97    5197  749.43  5212.6  750.18
  5226.6   750.2  5233.7  753.23  5242.2  757.61  5267.4  768.55  5295.5  775.74
#Mann= 3 ,-1 , 0
  4870.7     .14       0  4973.2    .045       0  5026.8     .14       0
Bank Sta=4973.2,5026.8
Exp/Cntr=0.3,0.1

Type RM Length L Ch R = 1 ,11483   ,406,406,406
BEGIN DESCRIPTION:
North Deep Creek 28.0
END DESCRIPTION:
XS GIS Cut Line= 4
      1533429.13       867125.81      1533403.54        866960.2
      1533349.34       866901.49      1533284.56       866872.86
#Sta/Elev= 30
  4777.4   757.7  4779.2  757.38  4785.7  755.54  4800.6  750.74  4825.4  744.59
  4833.7  742.71  4841.6  741.78  4856.7  739.13    4861  738.17  4882.8  736.45
    4892  735.25    4911  734.66  4925.1  733.38  4951.5  732.71  4958.9  731.21
  4971.8   729.9  4977.4  725.64  4978.6  724.56  4979.8  721.56  5020.2  721.56
  5024.9  724.58  5026.1  724.59  5027.3  726.09  5027.8  727.31  5032.8  738.07
  5033.3   739.3    5050  746.07  5053.5  747.65  5093.1  761.17  5095.7  761.73
#Mann= 3 ,-1 , 0
  4777.4     .14       0  4978.6    .045       0  5026.1     .14       0
Bank Sta=4978.6,5026.1
Exp/Cntr=0.3,0.1

Type RM Length L Ch R = 1 ,11077   ,110,110,110
BEGIN DESCRIPTION:
North Deep Creek 27.0
END DESCRIPTION:
XS GIS Cut Line= 5
      1533862.74       866912.03      1533739.28       866753.94
       1533689.6        866689.2      1533477.31       866650.06
      1533328.27       866650.06
#Sta/Elev= 30
  4766.2  760.23  4812.4  748.97  4847.6   744.4  4887.1  737.04  4916.1   733.7
  4919.5  732.75  4954.5  731.74  4958.7  730.86  4967.2  723.32  4970.5  722.89
  4972.2  719.89  5027.8  719.89  5029.5  722.89  5033.6   722.9  5054.1  733.93
  5088.2  733.04  5096.5  733.94  5117.1  733.03  5123.8  734.37  5140.2  735.69
    5164  735.62  5212.7  736.99  5255.7  739.39  5282.5  743.28  5296.7  744.74
  5307.7  744.84  5321.2  748.28  5347.7  751.85  5374.6  758.07  5413.3  764.79
#Mann= 3 ,-1 , 0
  4766.2     .14       0  4970.5    .045       0  5029.5     .14       0
Bank Sta=4970.5,5029.5
Exp/Cntr=0.3,0.1

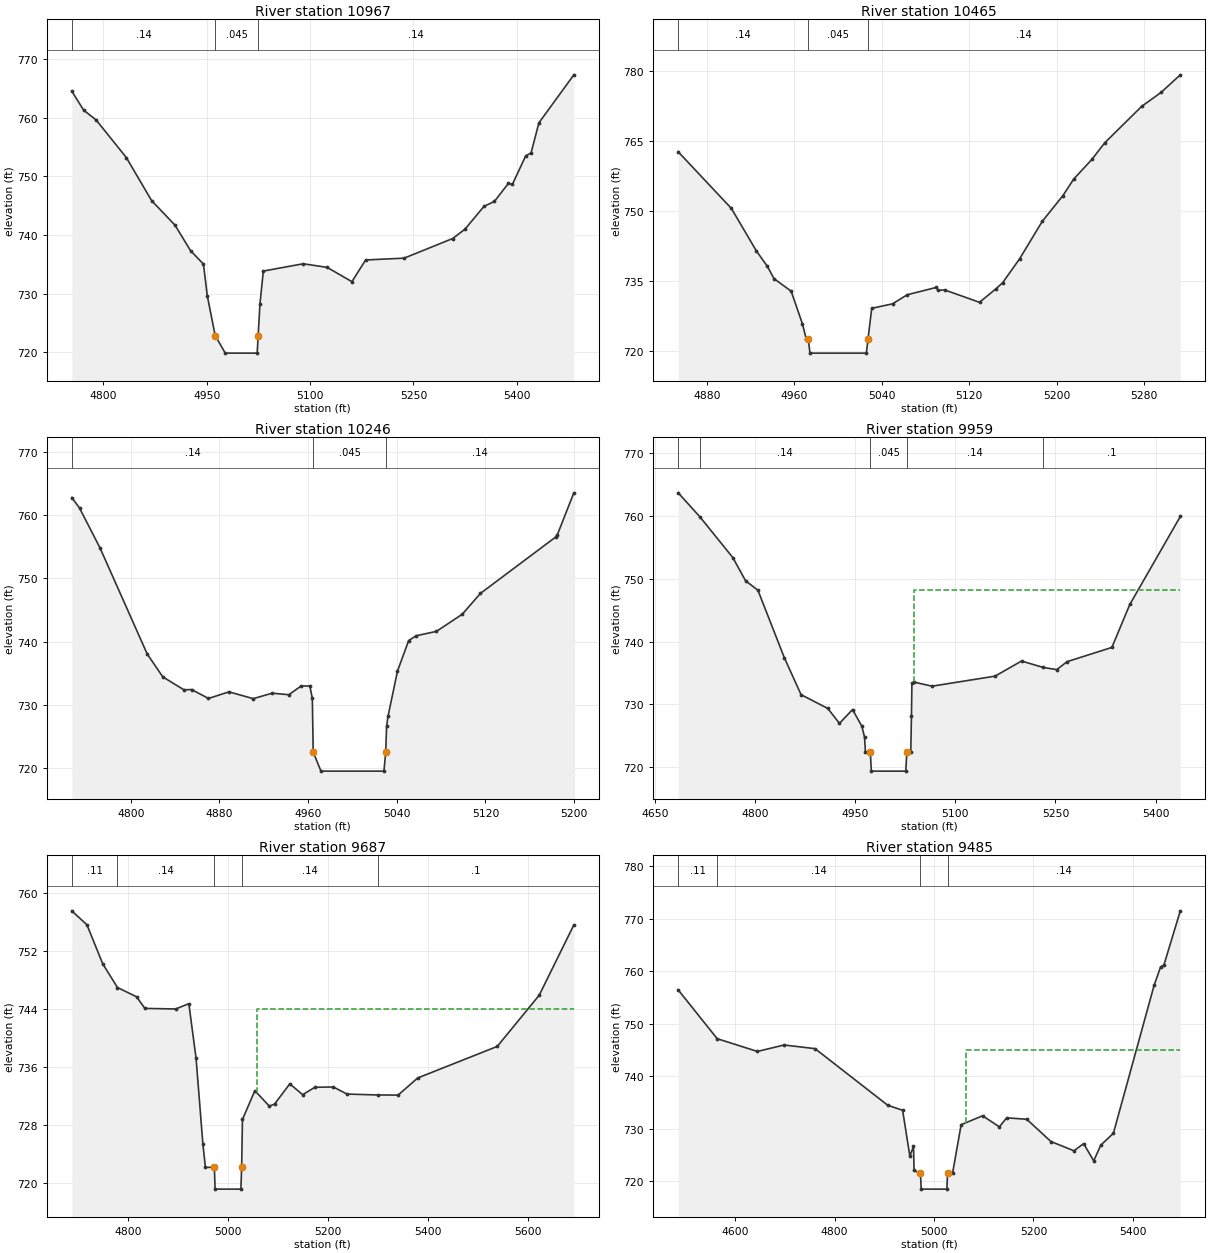
Type RM Length L Ch R = 1 ,10967   ,502,502,502
BEGIN DESCRIPTION:
North Deep Creek 26.0
END DESCRIPTION:
XS GIS Cut Line= 5
      1534036.65       866718.47      1533869.18       866674.24
       1533755.4       866645.79      1533470.95       866642.63
      1533325.55       866592.06
#Sta/Elev= 30
    4754  764.52  4771.2  761.27  4789.5  759.58  4833.2  753.19  4869.9  745.85
  4903.9  741.66  4926.5  737.31  4945.2  735.02  4950.7  729.65  4962.2  722.85
  4976.8  719.85  5023.2  719.85  5024.6  722.85  5027.2  728.22  5032.1  733.84
    5090  735.08  5124.7  734.47  5160.7  732.03  5180.6  735.73  5236.5  736.04
  5306.9  739.38  5324.9  740.98  5352.5  744.88  5367.5   745.7  5387.9  748.78
  5393.7  748.62    5413  753.47  5420.8  753.98  5432.2  759.11  5482.9  767.29
#Mann= 3 ,-1 , 0
    4754     .14       0  4962.2    .045       0  5024.6     .14       0
Bank Sta=4962.2,5024.6
Exp/Cntr=0.3,0.1

Type RM Length L Ch R = 1 ,10465   ,219,219,219
BEGIN DESCRIPTION:
North Deep Creek 25.0
END DESCRIPTION:
XS GIS Cut Line= 4
      1533834.44       866136.93      1533673.22       866190.67
      1533559.44       866162.23      1533388.79       866140.11
#Sta/Elev= 30
  4853.7  762.69  4902.3  750.59  4925.2  741.49  4935.3  738.17  4941.3  735.57
    4957  732.88  4967.3   725.9  4970.8  722.64  4972.7  722.63  4974.2  719.63
  5025.8  719.63  5027.3  722.63  5030.7  729.21  5049.8  730.18  5063.2  732.12
  5089.5  733.67  5091.5  733.08  5097.5  733.14  5129.3   730.5  5144.5  733.42
  5150.4  734.68  5165.9  739.77  5186.8  747.85  5205.5  753.29  5215.5  756.87
  5232.2  761.09  5243.8   764.6  5277.6   772.4  5295.3  775.38    5313  779.16
#Mann= 3 ,-1 , 0
  4853.7     .14       0  4972.7    .045       0  5027.3     .14       0
Bank Sta=4972.7,5027.3
Exp/Cntr=0.3,0.1

Type RM Length L Ch R = 1 ,10246   ,287,287,287
BEGIN DESCRIPTION:
North Deep Creek 24.0
END DESCRIPTION:
XS GIS Cut Line= 3
      1533850.25       866042.14      1533657.42       865982.08
      1533407.76       866007.36
#Sta/Elev= 30
  4746.8  762.76  4753.8   761.1  4772.3  754.79  4814.8  738.06  4828.9  734.43
  4847.9  732.39    4855  732.42  4870.1  731.02  4888.6  732.06  4910.5  730.99
  4927.6  731.85  4942.6  731.61  4953.8     733  4961.6  732.98  4963.8  731.02
  4964.6  722.54  4971.6  719.54  5028.4  719.54    5030  722.54  5030.8  726.66
  5032.1  728.22  5040.6  735.33  5050.7  740.17  5057.4  740.92  5075.8  741.62
  5099.1  744.33  5115.4  747.61  5183.2   756.5  5184.8  756.87  5199.7   763.5
#Mann= 3 ,-1 , 0
  4746.8     .14       0  4964.6    .045       0    5030     .14       0
Bank Sta=4964.6,5030
Exp/Cntr=0.3,0.1

Type RM Length L Ch R = 1 ,9959    ,272,272,272
BEGIN DESCRIPTION:
North Deep Creek 23.0
END DESCRIPTION:
XS GIS Cut Line= 5
       1533998.8       865868.32      1533862.86       865805.09
      1533676.39       865703.95      1533480.43       865770.32
      1533350.85        865899.9
#Sta/Elev= 30
  4684.9  763.73  4717.6  759.87  4766.6  753.42  4785.8  749.71  4804.3   748.2
  4843.8  737.46  4868.9  731.56    4909  729.36  4926.4  726.98    4946  729.18
    4960  726.53    4964  724.79  4965.4  722.38  4972.7  722.37  4974.2  719.37
  5025.8  719.37  5027.3  722.37  5033.3  722.38  5034.3  728.18    5035  733.34
  5038.1  733.56  5065.2  732.91  5159.6  734.51  5199.2  736.92  5231.5   735.9
    5252  735.55  5267.5  736.82  5334.6  739.09  5361.4  745.93  5437.1  759.96
#Mann= 5 ,-1 , 0
  4684.9     .11       0  4717.6     .14       0  4972.7    .045       0
  5027.3     .14       0  5231.5      .1       0
#XS Ineff= 2 , 0
       0                  5038.2       0  748.29
Permanent Ineff=
       F       F
Bank Sta=4972.7,5027.3
Exp/Cntr=0.3,0.1

Type RM Length L Ch R = 1 ,9687    ,202,202,202
BEGIN DESCRIPTION:
North Deep Creek 22.0
END DESCRIPTION:
XS GIS Cut Line= 6
       1534052.5       865751.38      1533976.64       865542.76
      1533935.55       865520.64      1533818.61       865520.64
      1533524.68       865615.45      1533331.89       865858.81
#Sta/Elev= 30
  4687.3  757.55  4717.7  755.62  4749.3  750.24  4778.8  746.98    4817   745.7
  4833.6   744.1  4895.3  744.02  4921.6  744.75  4936.1  737.22  4949.7  725.43
  4954.8  722.19  4972.7  722.19  4974.2  719.19  5025.8  719.19  5027.3  722.19
  5028.9  728.79  5053.8  732.76  5082.7  730.63  5093.1  730.91  5123.7   733.7
  5149.4  732.21  5173.9  733.23  5210.8  733.27  5238.3  732.29  5299.5  732.17
  5340.5  732.15  5379.6  734.51  5538.9  738.86  5622.9  745.92  5692.2  755.61
#Mann= 5 ,-1 , 0
  4687.3     .11       0  4778.8     .14       0  4972.7    .045       0
  5027.3     .14       0  5299.5      .1       0
#XS Ineff= 2 , 0
       0                  5057.5       0  743.95
Permanent Ineff=
       F       F
Bank Sta=4972.7,5027.3
Exp/Cntr=0.3,0.1

Type RM Length L Ch R = 1 ,9485    ,303,303,303
BEGIN DESCRIPTION:
North Deep Creek 21.5
END DESCRIPTION:
XS GIS Cut Line= 6
      1534053.88        865732.2      1533978.06        865456.3
      1533866.42       865403.64      1533651.57       865397.32
      1533459.89       865319.39      1533316.63       865211.94
#Sta/Elev= 30
  4485.2  756.45  4563.6  747.17  4644.5  744.74  4698.3  745.97  4760.6  745.27
  4906.8   734.5  4936.8  733.54  4951.4  724.81  4958.7   726.7  4959.9  722.08
  4972.7  721.53  4974.2  718.53  5025.8  718.53  5027.3  721.53  5037.3  721.54
  5054.6   730.8  5097.8  732.49  5131.5  730.39  5146.2   732.1  5186.7  731.83
  5235.3  727.59  5281.6  725.83  5301.1  727.19  5321.4  723.91  5335.7  726.91
    5361  729.16  5442.9   757.3    5456  760.82  5462.7  761.19  5495.7  771.51
#Mann= 4 ,-1 , 0
  4485.2     .11       0  4563.6     .14       0  4972.7    .045       0
  5027.3     .14       0
#XS Ineff= 2 , 0
       0                  5063.8       0  745.11
Permanent Ineff=
       F       F
Bank Sta=4972.7,5027.3
Exp/Cntr=0.3,0.1

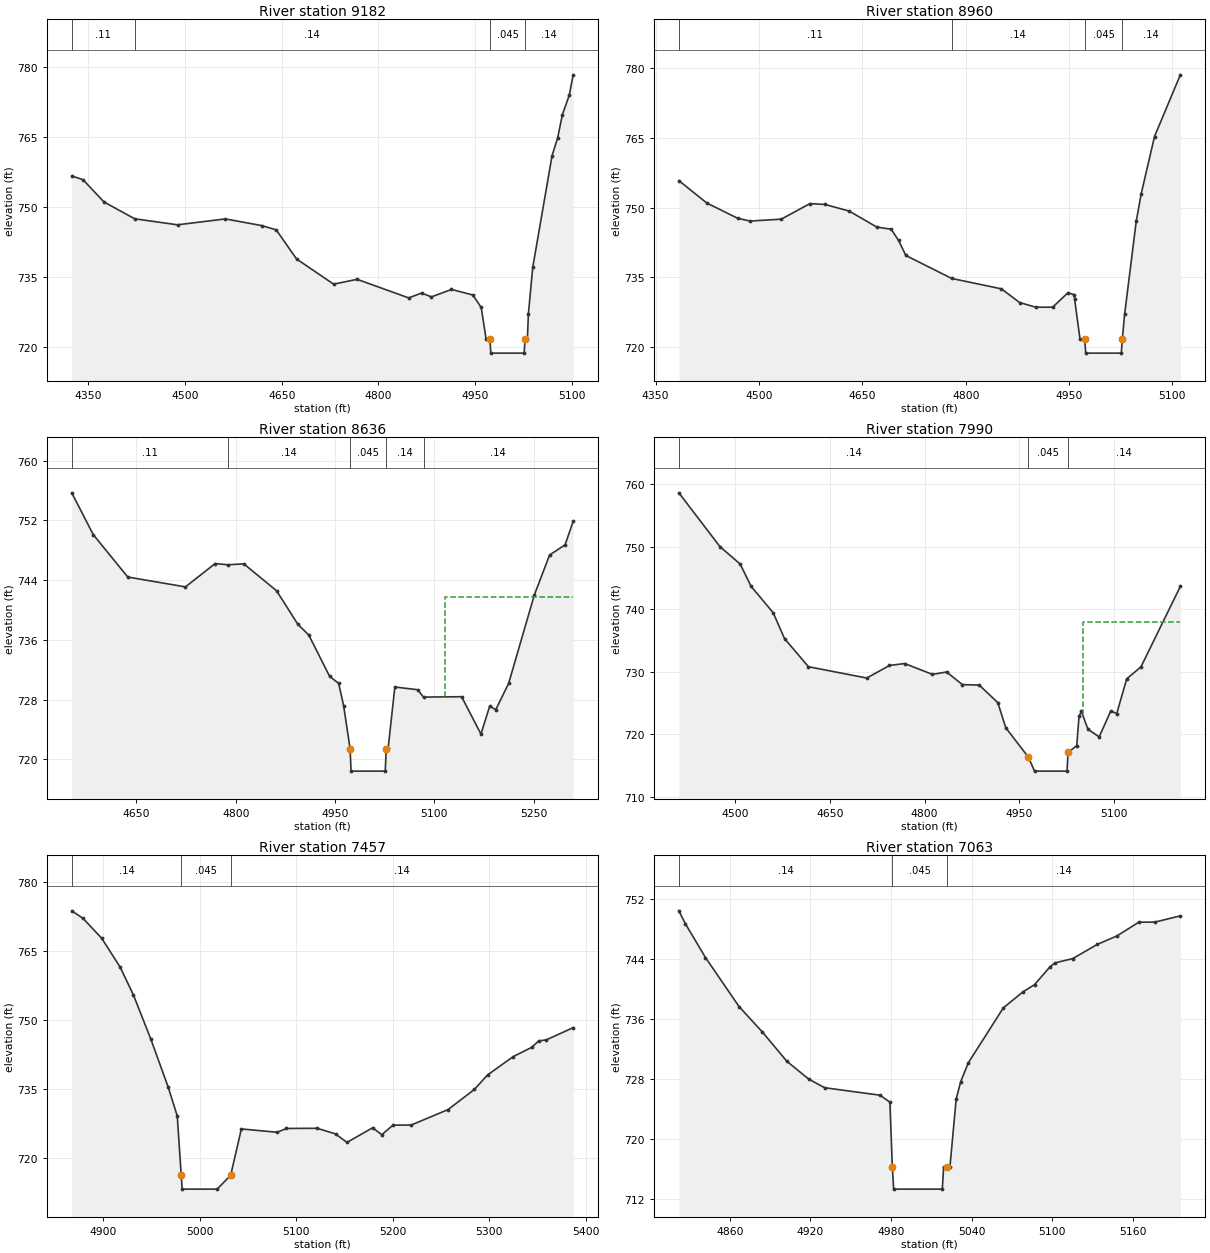
Type RM Length L Ch R = 1 ,9182    ,222,222,222
BEGIN DESCRIPTION:
North Deep Creek 21.0
END DESCRIPTION:
XS GIS Cut Line= 5
      1534071.45       865738.68       1534011.4       865457.43
      1533856.54       865172.98      1533809.13       865100.28
      1533802.81       865021.29
#Sta/Elev= 30
  4324.4  756.72    4342   755.9  4374.4  751.14    4422  747.54  4488.4  746.25
  4562.6  747.51  4618.7  746.09  4641.4  745.17    4673  738.93  4730.4  733.54
  4766.9  734.57  4846.9  730.59  4866.7  731.63  4882.1  730.81  4913.2   732.4
  4946.2  731.22  4959.3  728.54  4966.9  721.76  4972.7  721.76  4974.2  718.76
  5025.8  718.76  5027.3  721.76  5030.9  721.76  5032.4  727.14  5039.2  737.15
  5069.1  761.04  5077.8  764.86  5085.1  769.82  5095.7  773.97  5101.9  778.38
#Mann= 4 ,-1 , 0
  4324.4     .11       0    4422     .14       0  4972.7    .045       0
  5027.3     .14       0
Bank Sta=4972.7,5027.3
Exp/Cntr=0.3,0.1

Type RM Length L Ch R = 1 ,8960    ,324,324,324
BEGIN DESCRIPTION:
North Deep Creek 20.0
END DESCRIPTION:
XS GIS Cut Line= 4
      1534106.23       865719.79      1534052.49       865501.67
      1534046.17       865154.01      1534033.53       864999.19
#Sta/Elev= 30
  4383.8  755.81  4424.3  750.99  4469.1   747.7  4487.2   747.1  4532.4  747.51
    4574  750.86    4596  750.67  4630.9  749.25  4671.1   745.8  4691.9  745.34
  4702.6  742.93  4713.2  739.69  4779.7  734.74  4851.9   732.5  4878.2  729.56
  4901.6  728.55  4926.2  728.55  4948.3  731.65  4957.8  731.23  4958.1  730.25
  4965.9  721.67  4972.7  721.66  4974.2  718.66  5025.8  718.66  5027.3  721.66
  5030.6  726.99  5047.5  747.06  5054.8  753.03    5074   765.3  5111.5  778.59
#Mann= 4 ,-1 , 0
  4383.8     .11       0  4779.7     .14       0  4972.7    .045       0
  5027.3     .14       0
Bank Sta=4972.7,5027.3
Exp/Cntr=0.3,0.1

Type RM Length L Ch R = 1 ,8636    ,646,646,646
BEGIN DESCRIPTION:
North Deep Creek 19.0
END DESCRIPTION:
XS GIS Cut Line= 5
      1534172.59       865719.79      1534156.79       865498.51
       1534308.5       865267.79       1534308.5       865157.17
      1534248.43       865021.24
#Sta/Elev= 30
  4552.4  755.68    4585  750.07    4637  744.41  4724.1  743.09  4768.9  746.21
    4788  746.05  4812.3  746.17  4861.7  742.57  4893.8  738.09  4910.3  736.65
  4941.8  731.12  4955.4  730.17  4962.9  727.21  4972.7  721.43  4974.2  718.43
  5025.8  718.43  5027.3  721.43  5030.2  721.52  5040.3  729.69  5074.5  729.33
  5083.6  728.34  5141.1  728.39  5170.3  723.39  5183.6  727.15  5192.6  726.64
  5212.1  730.17  5250.9     742  5273.9  747.35  5297.4  748.73  5309.6  751.87
#Mann= 5 ,-1 , 0
  4552.4     .11       0    4788     .14       0  4972.7    .045       0
  5027.3     .14       0  5083.6     .14       0
#XS Ineff= 2 , 0
       0                  5116.2       0  741.67
Permanent Ineff=
       F       F
Bank Sta=4972.7,5027.3
Exp/Cntr=0.3,0.1

Type RM Length L Ch R = 1 ,7990    ,533,533,533
BEGIN DESCRIPTION:
North Deep Creek 17.0
END DESCRIPTION:
XS GIS Cut Line= 5
      1534305.33       865754.52      1534434.92       865654.96
      1534752.55       865525.38      1534874.23       865530.12
      1534975.35       865662.84
#Sta/Elev= 30
  4410.3   758.6  4475.3  750.01  4507.5  747.21  4524.8  743.65  4559.7  739.45
  4577.8   735.3  4615.7   730.8  4708.2  728.99  4744.2     731  4768.3  731.31
  4812.4  729.57  4834.8  729.96  4859.8  727.94  4886.4  727.87    4916  725.06
  4928.6  721.05  4964.5  716.34  4974.2  714.11  5025.8  714.11  5027.3  717.11
  5041.1  718.17  5044.8  722.89  5048.5  723.65  5058.9  720.81  5076.7  719.58
  5095.1  723.73  5104.5   723.3  5120.4  728.87  5142.9  730.77  5205.4  743.64
#Mann= 3 ,-1 , 0
  4410.3     .14       0  4964.5    .045       0  5027.3     .14       0
#XS Ineff= 2 , 0
       0                  5050.6       0  737.98
Permanent Ineff=
       F       F
Bank Sta=4964.5,5027.3
Exp/Cntr=0.3,0.1

Type RM Length L Ch R = 1 ,7457    ,394,394,394
BEGIN DESCRIPTION:
North Deep Creek 16.0
END DESCRIPTION:
XS GIS Cut Line= 4
      1534359.02        865909.4      1534450.72       865879.36
      1534697.24       865844.59      1534871.07       865838.27
#Sta/Elev= 30
  4867.5  773.82  4879.2  772.18  4898.6  767.83  4917.6  761.59  4931.3  755.57
  4949.4  745.93  4967.4  735.49  4976.8  729.21  4980.9   716.3  4981.9   713.3
  5018.1   713.3  5032.1   716.3  5043.2  726.39  5080.3  725.66  5089.9  726.49
  5121.7  726.53  5140.7  725.31  5152.6  723.46  5179.2  726.65  5188.6  725.13
  5200.2  727.21  5219.2  727.24  5257.3   730.6  5284.5  734.97  5298.2  738.13
  5324.8  742.12  5343.9  744.13  5351.2  745.54  5358.9  745.74  5386.9  748.42
#Mann= 3 ,-1 , 0
  4867.5     .14       0  4980.9    .045       0  5032.1     .14       0
Bank Sta=4980.9,5032.1
Exp/Cntr=0.3,0.1

Type RM Length L Ch R = 1 ,7063    ,202,202,202
BEGIN DESCRIPTION:
North Deep Creek 15.0
END DESCRIPTION:
XS GIS Cut Line= 4
      1534741.51       866155.87      1534814.18       866031.07
      1534826.83       865977.34      1534913.75        865827.2
#Sta/Elev= 30
  4822.1  750.36    4827  748.62  4841.9  744.13  4866.9  737.59  4884.2  734.21
  4902.4  730.31  4918.6  727.94  4930.5  726.78  4971.8  725.78  4979.1  724.85
  4980.9  716.26  4981.9  713.26  5018.1  713.26  5019.1  716.26  5021.7  716.27
  5023.8  716.27  5028.4  725.25  5031.7  727.54  5037.4  730.09  5063.5  737.42
  5077.9  739.53  5086.7  740.52  5098.3  742.91  5102.1  743.43  5115.1  743.99
  5133.5  745.89  5148.1  747.02  5164.3  748.84  5176.3  748.86  5195.2  749.69
#Mann= 3 ,-1 , 0
  4822.1     .14       0  4980.9    .045       0  5021.7     .14       0
Bank Sta=4980.9,5021.7
Exp/Cntr=0.3,0.1