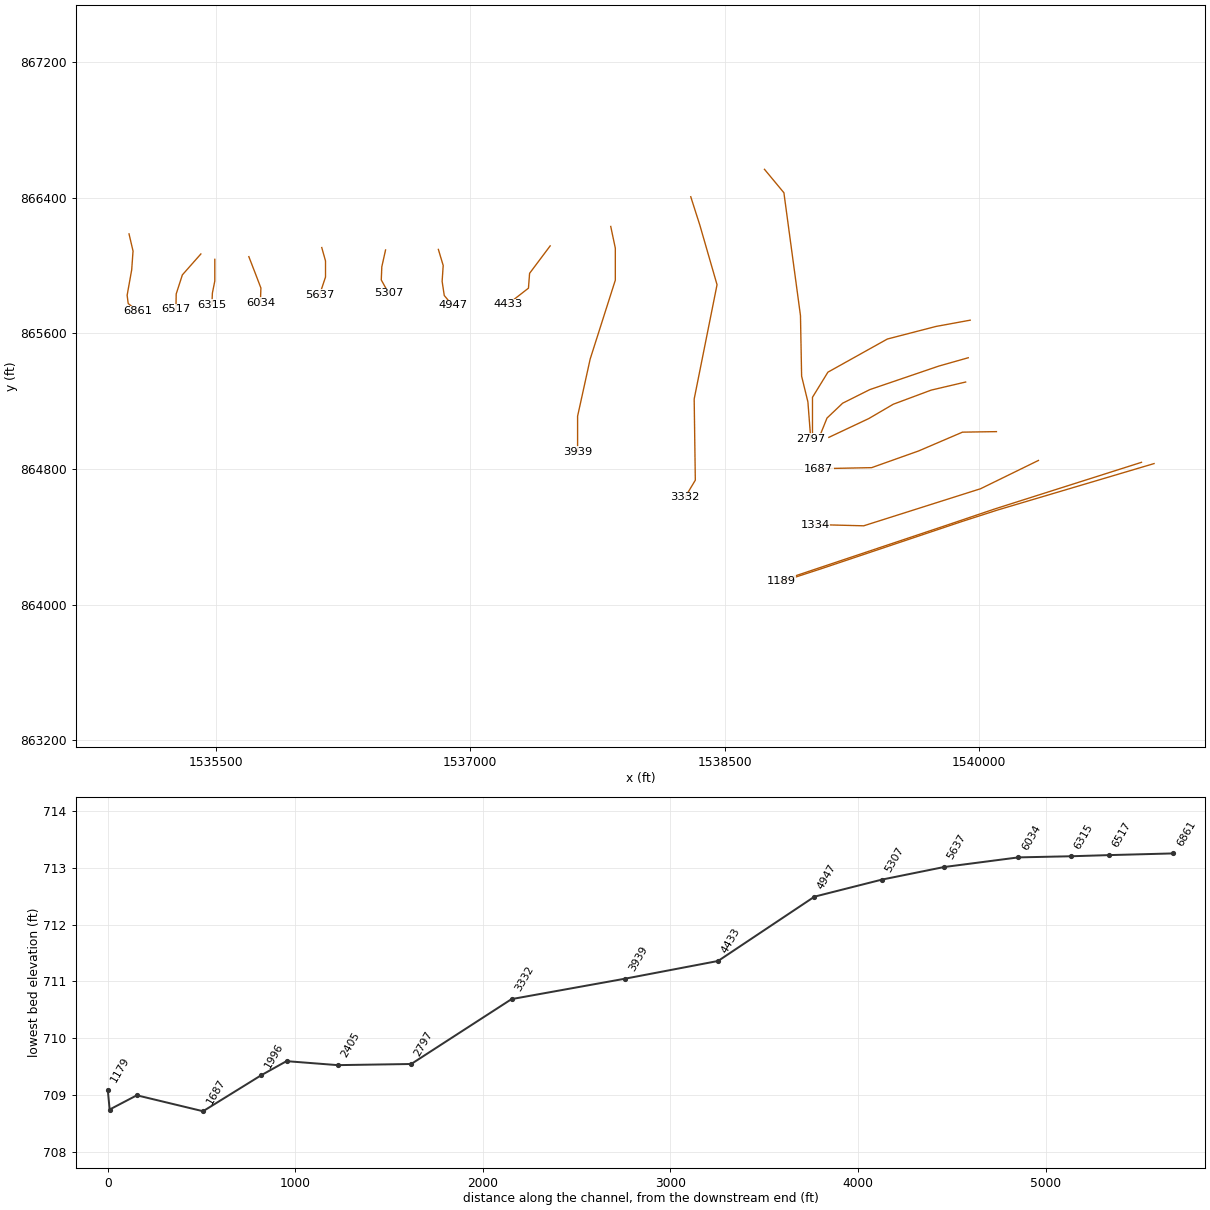
HEC-RAS study North Deep Creek.prj: North Deep Creek Limited Detail Study

--- North Deep Creek.g01 (geometry) --- (continued)

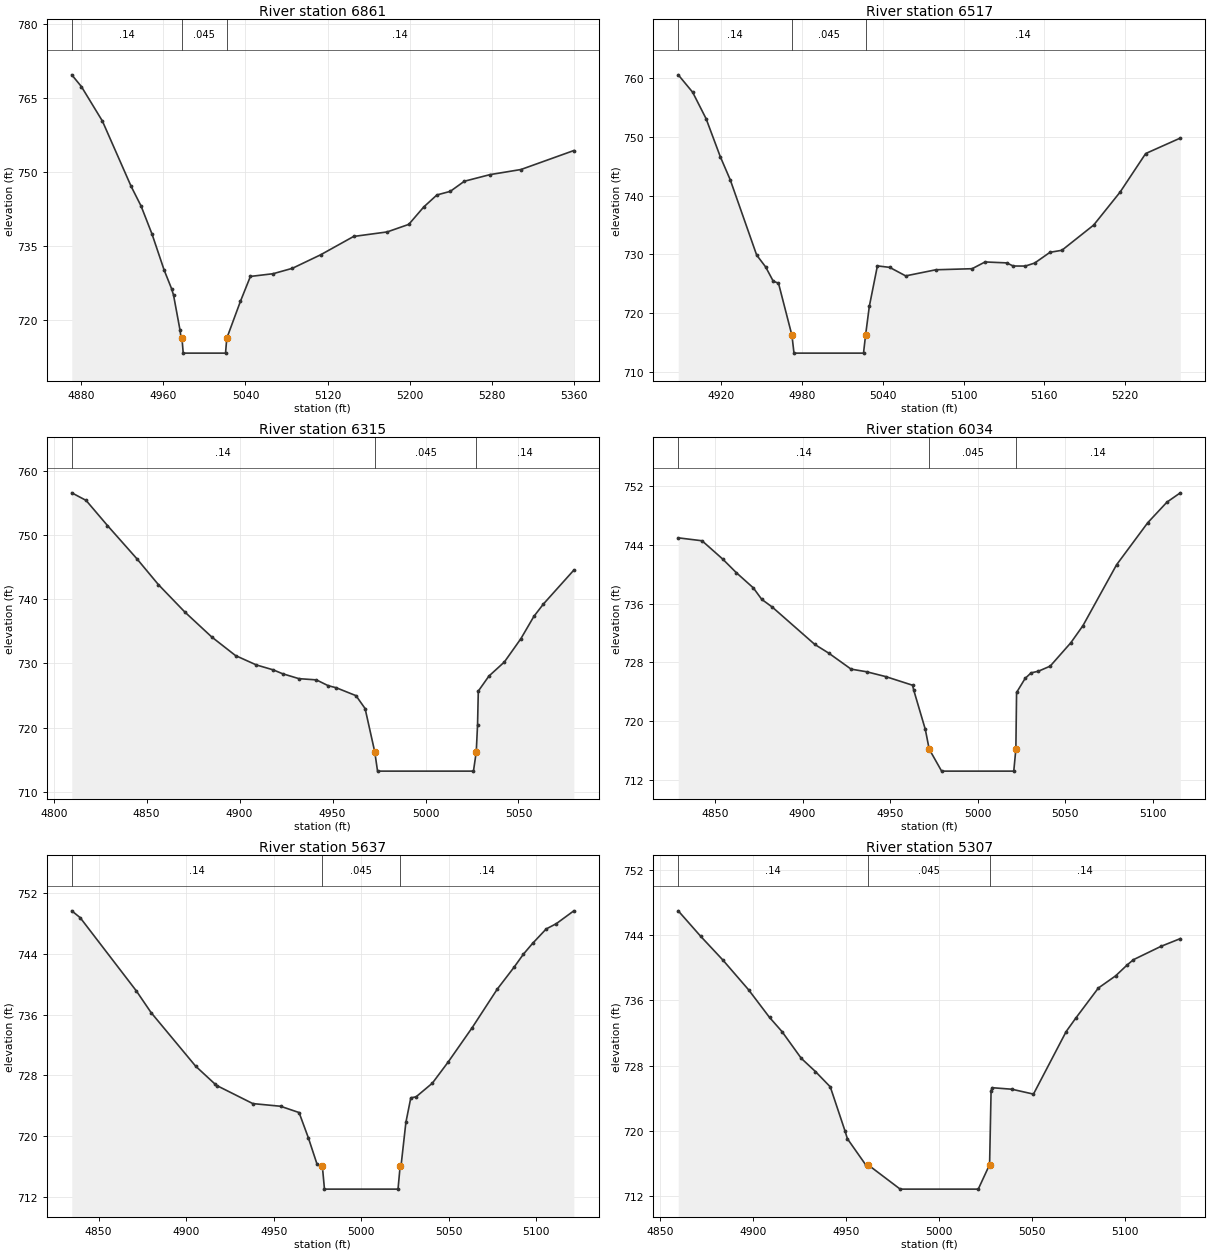
Type RM Length L Ch R = 1 ,6861    ,344,344,344
BEGIN DESCRIPTION:
North Deep Creek 14.0
END DESCRIPTION:
XS GIS Cut Line= 6
      1534989.59       866185.97       1535013.3        866084.8
       1535005.4       865974.18      1534978.53       865824.05
      1534984.85       865775.06      1535041.75       865730.81
#Sta/Elev= 30
  4870.9  769.71  4880.3  767.32  4900.7  760.34  4928.7  747.08  4938.4  743.08
    4949  737.42  4960.9  730.06    4968  726.36    4970     725  4976.2  718.02
  4977.4  716.25  4978.2  716.25  4979.4  713.25  5020.6  713.25  5021.8  716.25
  5035.1  723.76  5044.8  728.81  5066.9  729.36  5085.7  730.46  5113.1  733.19
  5145.3  736.92    5178  737.84    5199  739.37  5213.6  742.91  5226.4  745.34
  5239.4  746.07  5253.1  748.12    5278  749.46  5308.2   750.5  5359.7  754.35
#Mann= 3 ,-1 , 0
  4870.9     .14       0  4978.2    .045       0  5021.8     .14       0
Bank Sta=4978.2,5021.8
Exp/Cntr=0.3,0.1

Type RM Length L Ch R = 1 ,6517    ,202,202,202
BEGIN DESCRIPTION:
North Deep Creek 13.0
END DESCRIPTION:
XS GIS Cut Line= 4
      1535413.12       866067.43      1535304.07       865944.15
      1535267.72       865831.95      1535266.14       865741.89
#Sta/Elev= 30
  4888.3  760.53    4899  757.57    4909  753.06  4919.5  746.62  4926.9  742.68
  4946.5  729.89  4953.2  727.86  4958.8  725.45  4962.7  725.11  4972.7  716.22
  4974.2  713.22  5025.8  713.22  5027.3  716.22  5030.1  721.16  5036.1  728.05
  5045.2   727.8  5057.1  726.35  5079.5  727.39  5106.4  727.57    5116  728.72
    5132  728.56  5136.9  728.03  5145.9  728.02  5152.8  728.53  5164.2  730.36
    5173   730.7  5196.6  734.99  5216.2  740.59  5235.2  747.15  5260.9  749.78
#Mann= 3 ,-1 , 0
  4888.3     .14       0  4972.7    .045       0  5027.3     .14       0
Bank Sta=4972.7,5027.3
Exp/Cntr=0.3,0.1

Type RM Length L Ch R = 1 ,6315    ,281,281,281
BEGIN DESCRIPTION:
North Deep Creek 12.0
END DESCRIPTION:
XS GIS Cut Line= 4
      1535495.28       866035.78      1535495.28        865907.8
      1535481.06       865836.69       1535477.9       865767.16
#Sta/Elev= 29
  4809.7   756.6  4817.4  755.42  4828.9   751.5  4844.7  746.33  4856.3  742.29
  4870.5  738.02    4885  734.12  4897.8  731.22    4909  729.76  4918.1  728.99
  4923.1  728.39  4931.9  727.62  4941.3  727.43  4947.6  726.53    4952   726.2
  4962.6  724.97  4967.5  722.96  4972.7   716.2  4974.2   713.2  5025.8   713.2
  5027.3   716.2    5028  720.44  5028.4  725.68  5034.1  728.02  5042.4  730.21
  5051.3  733.85  5058.3  737.33  5063.4  739.25  5079.8  744.55
#Mann= 3 ,-1 , 0
  4809.7     .14       0  4972.7    .045       0  5027.3     .14       0
Bank Sta=4972.7,5027.3
Exp/Cntr=0.3,0.1

Type RM Length L Ch R = 1 ,6034    ,397,397,397
BEGIN DESCRIPTION:
North Deep Creek 11.0
END DESCRIPTION:
XS GIS Cut Line= 4
      1535695.97       866051.62       1535733.9       865953.63
      1535767.09       865866.72      1535763.93       865778.18
#Sta/Elev= 30
    4829  744.95  4842.6  744.55  4854.3  742.08  4862.2   740.2  4871.9  738.13
  4876.7  736.57  4882.7  735.52    4907  730.43    4915  729.24  4927.7  727.07
  4936.6  726.71  4947.4  726.06  4962.8  724.88  4963.5  724.19  4970.1  718.85
  4972.3  716.18  4979.4  713.18  5020.6  713.18  5021.8  716.18  5022.2  723.89
  5027.1  725.81  5030.5  726.56  5034.7  726.79  5041.4  727.48  5053.2  730.67
  5060.1  732.99  5079.3  741.28  5097.1  747.01  5108.1  749.82  5115.7  751.08
#Mann= 3 ,-1 , 0
    4829     .14       0  4972.3    .045       0  5021.8     .14       0
Bank Sta=4972.3,5021.8
Exp/Cntr=0.3,0.1

Type RM Length L Ch R = 1 ,5637    ,330,330,330
BEGIN DESCRIPTION:
North Deep Creek 10.0
END DESCRIPTION:
XS GIS Cut Line= 4
      1536125.82       866105.31      1536147.94       866026.33
      1536147.94       865931.51       1536113.2       865827.29
#Sta/Elev= 30
  4834.7  749.68  4839.5  748.78  4871.6  739.12    4880  736.27  4905.4  729.22
  4916.7  726.81  4917.5  726.66  4938.1  724.28  4953.9  723.93  4964.5   723.1
  4969.8  719.77  4974.7  716.34  4977.8  716.01    4979  713.01    5021  713.01
  5022.2  716.01  5022.7  716.03  5025.5  721.82  5028.3  725.04  5031.3  725.17
  5040.6  726.97  5049.7  729.78  5063.3  734.27  5077.6  739.34  5087.3  742.26
  5092.6  743.97  5097.8  745.38  5105.6  747.29  5111.4  747.99  5121.4  749.68
#Mann= 3 ,-1 , 0
  4834.7     .14       0  4977.8    .045       0  5022.2     .14       0
Bank Sta=4977.8,5022.2
Exp/Cntr=0.3,0.1

Type RM Length L Ch R = 1 ,5307    ,360,360,360
BEGIN DESCRIPTION:
North Deep Creek 9.0
END DESCRIPTION:
XS GIS Cut Line= 4
      1536501.92       866091.13      1536479.79       865991.56
      1536476.63       865914.13       1536520.9       865835.07
#Sta/Elev= 28
  4859.6  747.03  4871.7  743.89  4883.6  740.98  4897.5   737.3  4908.7  733.92
  4915.4  732.18  4925.8  728.88  4933.4  727.26  4941.4  725.37  4949.4  719.89
  4950.6  718.99  4960.4   715.8  4961.6   715.8    4979  712.79    5021  712.79
  5027.1   715.8  5027.9  724.86  5028.4  725.27  5039.1  725.08  5050.7  724.48
  5068.3  732.18  5073.4  733.81  5085.6  737.53  5094.9  739.03  5101.2  740.39
  5104.5  741.02  5119.3  742.66  5129.7  743.61
#Mann= 3 ,-1 , 0
  4859.6     .14       0  4961.6    .045       0  5027.1     .14       0
Bank Sta=4961.6,5027.1
Exp/Cntr=0.3,0.1

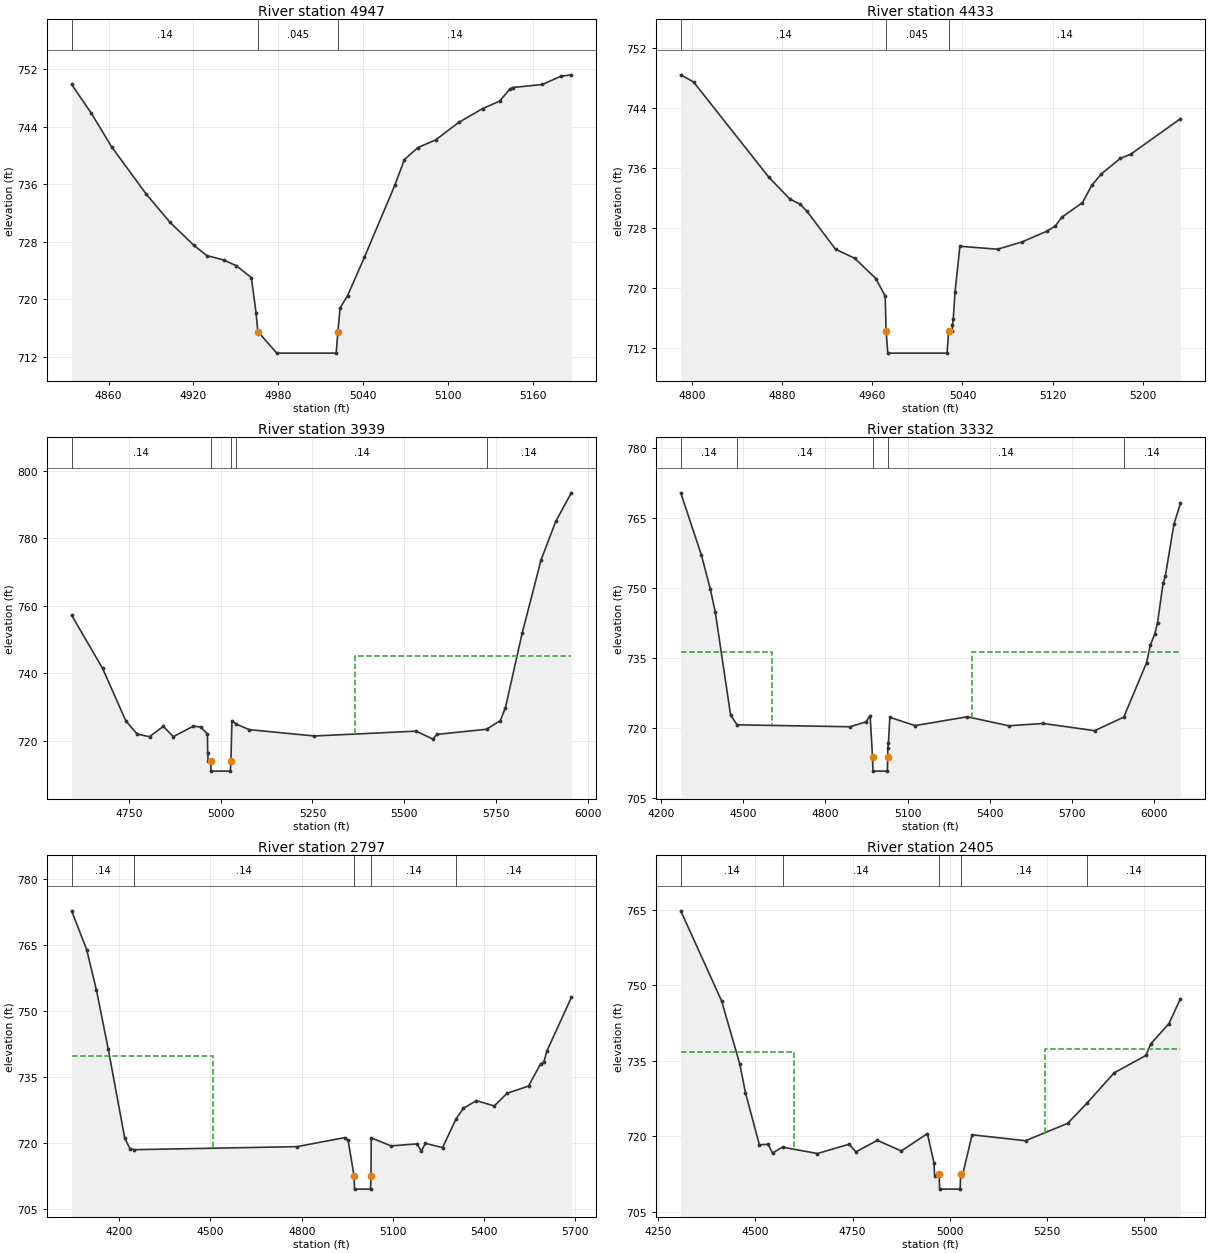
Type RM Length L Ch R = 1 ,4947    ,514,514,514
BEGIN DESCRIPTION:
North Deep Creek 8.0
END DESCRIPTION:
XS GIS Cut Line= 5
      1536813.23       866094.29      1536841.68       865999.46
      1536835.36       865906.22        1536848.       865822.47
      1536896.96       865764.03
#Sta/Elev= 30
  4833.9  749.88  4847.9  745.85  4862.2  741.19  4886.5  734.66  4903.5  730.69
  4920.4  727.48  4929.6  726.06  4941.3  725.46  4950.4  724.65    4961     723
  4964.3  718.13  4965.6  715.49    4979  712.49    5021  712.49  5022.2  715.49
  5023.8   718.8    5029  720.47  5040.9  725.81  5062.5  735.87  5069.2  739.42
  5078.8   741.1  5091.3  742.16  5107.7   744.6  5124.5  746.52  5136.5  747.55
  5143.6   749.2  5145.7  749.45  5166.9  749.88  5179.7  751.01  5187.3  751.22
#Mann= 3 ,-1 , 0
  4833.9     .14       0  4965.6    .045       0  5022.2     .14       0
Bank Sta=4965.6,5022.2
Exp/Cntr=0.3,0.1

Type RM Length L Ch R = 1 ,4433    ,494,494,494
BEGIN DESCRIPTION:
North Deep Creek 7.0
END DESCRIPTION:
XS GIS Cut Line= 4
      1537472.23       866115.11      1537350.97       865953.42
      1537344.23       865865.84      1537222.95       865771.51
#Sta/Elev= 30
  4789.9  748.42  4801.3  747.47    4868   734.8  4886.7  731.89  4896.1  731.17
  4902.1  730.22  4927.3   725.2  4944.5  723.98  4963.1  721.29  4971.4  718.95
  4972.2  714.36  4973.7  711.36  5026.3  711.36  5027.8  714.36    5031  714.37
  5031.1  715.11  5031.8  715.94  5033.4  719.48  5037.7  725.59  5071.2   725.2
  5092.9  726.17  5115.1  727.61  5122.5   728.3  5128.3  729.47  5146.5   731.4
  5154.8   733.7  5163.3  735.23  5180.2   737.3  5189.2  737.83  5233.5  742.58
#Mann= 3 ,-1 , 0
  4789.9     .14       0  4972.2    .045       0  5027.8     .14       0
Bank Sta=4972.2,5027.8
Exp/Cntr=0.3,0.1

Type RM Length L Ch R = 1 ,3939    ,607,607,607
BEGIN DESCRIPTION:
North Deep Creek 6.0
END DESCRIPTION:
XS GIS Cut Line= 6
      1537829.34       866229.65      1537856.29       866101.65
      1537856.29         865913.      1537708.06        865448.1
      1537633.95       865111.22      1537633.95       864902.37
#Sta/Elev= 30
  4593.9  757.19  4678.2  741.48  4741.6   725.9  4772.5  722.01    4806  721.26
  4843.6   724.3  4870.9  721.26  4925.8  724.39  4945.4  724.09  4963.8  722.05
  4964.5  716.33  4965.8  714.05  4972.2  714.05  4973.7  711.05  5026.3  711.05
  5027.8  714.05  5030.5  725.99  5042.8  724.94  5078.2  723.32  5255.3  721.46
  5531.8  722.89  5577.8  720.56  5588.6  721.93  5724.1  723.45  5761.4  725.99
  5775.4  729.78  5821.2  751.92  5872.8  773.65  5912.5  784.98  5955.1  793.46
#Mann= 5 ,-1 , 0
  4593.9     .14       0  4972.2    .045       0  5027.8     .14       0
  5042.8     .14       0  5724.1     .14       0
#XS Ineff= 2 , 0
       0                  5366.6       0   745.2
Permanent Ineff=
       F       F
Bank Sta=4972.2,5027.8
Exp/Cntr=0.3,0.1

Type RM Length L Ch R = 1 ,3332    ,535,535,535
BEGIN DESCRIPTION:
North Deep Creek 5.0
END DESCRIPTION:
XS GIS Cut Line= 6
      1538300.98       866404.82      1538354.87        866236.4
      1538455.93       865886.05      1538321.18       865212.29
      1538327.92       864733.92      1538267.26       864632.82
#Sta/Elev= 30
  4271.8  770.44  4346.9  757.14  4379.6  749.81  4397.8  744.89  4453.7  722.77
  4477.3  720.63  4890.4  720.22  4948.5  721.27  4963.4  722.61  4972.2  713.69
  4973.7  710.69  5026.3  710.69  5027.8  713.69  5028.1  715.73  5030.3  716.64
  5035.3  722.24  5127.5  720.47  5318.4  722.36  5469.4  720.43  5596.1  720.92
  5783.5  719.37  5889.7  722.29    5973  733.97  5986.9  737.74  6003.1  740.16
    6013   742.5  6033.3  751.01  6041.5  752.54  6072.7  763.66  6096.7  768.18
#Mann= 5 ,-1 , 0
  4271.8     .14       0  4477.3     .14       0  4972.2    .045       0
  5027.8     .14       0  5889.7     .14       0
#XS Ineff= 2 , 0
       0  4605.4  736.21  5335.1       0  736.21
Permanent Ineff=
       F       F
Bank Sta=4972.2,5027.8
Exp/Cntr=0.3,0.1

Type RM Length L Ch R = 1 ,2797    ,392,392,392
BEGIN DESCRIPTION:
North Deep Creek 4.0
END DESCRIPTION:
XS GIS Cut Line= 6
      1538735.55       866566.54      1538850.08       866428.43
      1538947.78       865704.13      1538954.52       865347.04
      1538991.57       865195.44      1539008.42       864976.49
#Sta/Elev= 30
  4043.5  772.69    4093  763.86  4125.2  754.66    4164  741.26  4218.1  721.12
    4235  718.76  4249.8   718.5  4784.3  719.19  4941.5  721.24  4952.5  720.66
  4972.2  712.55  4973.7  709.55  5026.3  709.55  5027.8  712.55  5028.6  721.18
  5093.7  719.36  5178.9  719.81  5193.2  718.17  5206.9  719.93  5263.2  718.97
    5308  725.55  5331.8  727.88  5374.1  729.62  5433.3  728.43  5474.8  731.27
  5545.8  732.94  5585.8  738.02  5595.6  738.29  5606.7  740.96  5686.6  753.03
#Mann= 5 ,-1 , 0
  4043.5     .14       0  4249.8     .14       0  4972.2    .045       0
  5027.8     .14       0    5308     .14       0
#XS Ineff= 2 , 0
       0  4507.4  739.69               0
Permanent Ineff=
       F       F
Bank Sta=4972.2,5027.8
Exp/Cntr=0.3,0.1

Type RM Length L Ch R = 1 ,2405    ,273,273,273
BEGIN DESCRIPTION:
North Deep Creek 3.0
END DESCRIPTION:
XS GIS Cut Line= 6
      1539948.33       865677.19      1539746.19       865640.13
      1539459.84       865566.01      1539109.48       865370.62
      1539018.52       865222.39      1539018.52       865013.56
#Sta/Elev= 30
  4307.8  764.76    4413  746.86  4459.6  734.38  4474.2  728.69    4510  718.34
  4532.7  718.42  4543.8   716.7  4569.6  717.86  4659.2   716.6  4740.8  718.44
  4758.4  716.92  4813.4  719.21    4875  717.11  4942.2  720.55  4959.4  714.66
  4960.7  712.15  4972.2  712.53  4973.7  709.53  5026.3  709.53  5027.8  712.53
  5032.1  712.16  5057.1  720.31  5194.6  719.14  5302.9  722.58  5352.3  726.56
  5422.4   732.6  5504.3  736.07  5516.6  738.35  5563.1  742.35    5593  747.31
#Mann= 5 ,-1 , 0
  4307.8     .14       0  4569.6     .14       0  4972.2    .045       0
  5027.8     .14       0  5352.3     .14       0
#XS Ineff= 2 , 0
       0    4600  736.66  5245.3       0  737.27
Permanent Ineff=
       F       F
Bank Sta=4972.2,5027.8
Exp/Cntr=0.5,0.3

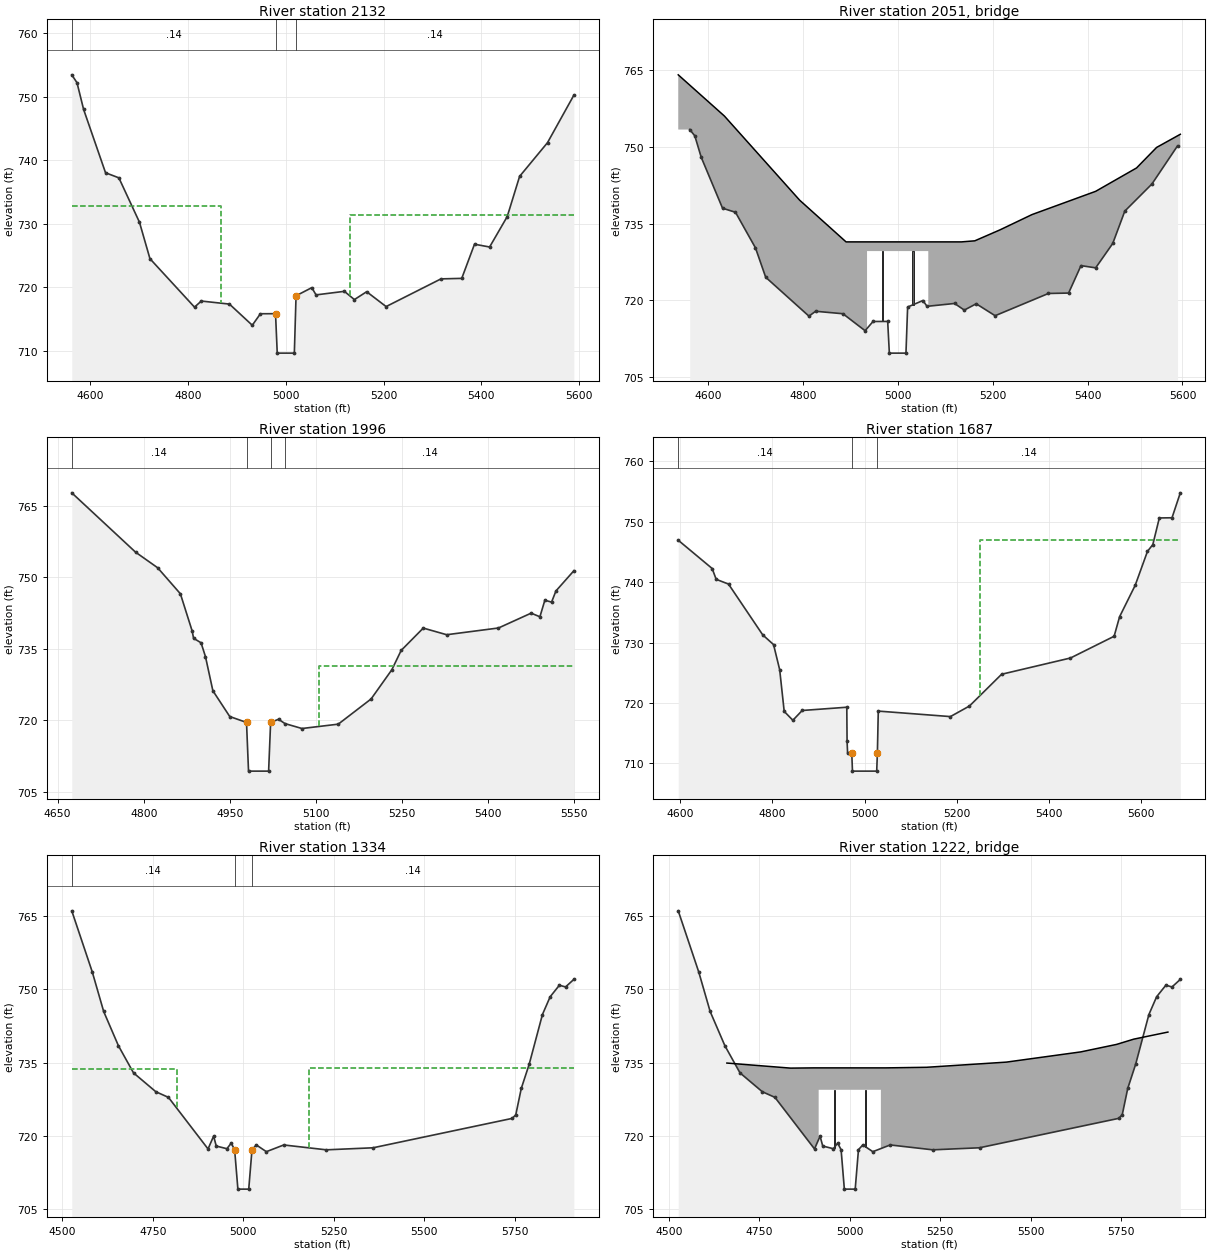
Type RM Length L Ch R = 1 ,2132    ,136,136,136
BEGIN DESCRIPTION:
Shacktown Rd (NDC) us
END DESCRIPTION:
XS GIS Cut Line= 6
      1539936.78       865455.71      1539762.85       865406.45
      1539356.57       865267.95      1539196.53       865187.93
      1539104.19       865100.21      1539062.63       864997.07
#Sta/Elev= 30
    4562  753.42  4572.7  752.18  4586.2  747.98  4631.1     738  4658.4   737.2
  4700.5  730.22    4722  724.47  4813.2  716.84  4827.1   717.8  4884.7  717.32
  4931.4  713.99  4948.1   715.8    4979  715.81  4982.5   709.6  5017.5   709.6
    5021  718.63  5053.2  719.91  5061.9  718.77  5119.9  719.33  5140.4  718.03
  5165.5  719.27  5205.3  716.93  5317.6  721.29  5360.1  721.37  5386.2  726.75
  5417.1  726.31  5453.1  731.09  5478.5  737.43  5535.6  742.74  5589.5  750.21
#Mann= 3 ,-1 , 0
    4562     .14       0    4979    .045       0    5021     .14       0
#XS Ineff= 2 , 0
       0    4868   732.8    5132       0   731.4
Permanent Ineff=
       F       F
Bank Sta=4979,5021
Exp/Cntr=0.5,0.3

Type RM Length L Ch R = 3 ,2051    ,,,
BEGIN DESCRIPTION:
Shacktown Rd (NDC) tor
Structure ID: LDS_NDC_02
Approximate Survey Structure
END DESCRIPTION:
Bridge Culvert--1,0,-1,-1, 0
Deck Dist Width WeirC Skew NumUp NumDn MinLoCord MaxHiCord MaxSubmerge Is_Ogee
67.5,27,3,0, 16, 16, , , 0.95, 0, 1,1,,
  4537.8    4635  4793.6  4891.3  4935.5  4935.5  5064.5  5064.5  5134.3  5162.5
  5215.4  5282.9  5417.1  5503.2  5545.4  5595.4
  764.14  756.07  739.57   731.4   731.4   731.4   731.4   731.4   731.4  731.61
  733.75  736.75  741.31  745.89  749.91  752.49
   689.6   689.6   689.6   689.6   689.6   729.6   729.6   689.6   689.6   689.6
   689.6   689.6   689.6   689.6   689.6   689.6
  4537.8    4635  4793.6  4891.3  4935.5  4935.5  5064.5  5064.5  5134.3  5162.5
  5215.4  5282.9  5417.1  5503.2  5545.4  5595.4
  764.14  756.07  739.57   731.4   731.4   731.4   731.4   731.4   731.4  731.61
  733.75  736.75  741.31  745.89  749.91  752.49
   689.6   689.6   689.6   689.6   689.6   729.6   729.6   689.6   689.6   689.6
   689.6   689.6   689.6   689.6   689.6   689.6
Pier Skew, UpSta & Num, DnSta & Num=  ,4967.8, 2 ,4967.8, 2 , 0 , 0 , 0 ,0,0
       3       3
  712.59   729.6
       3       3
  720.28   729.6
Pier Skew, UpSta & Num, DnSta & Num=  ,5032.3, 2 ,5032.3, 2 , 0 , 0 , 0 ,0,0
       3       3
  715.86   729.6
       3       3
  719.95   729.6
Abutment Skew #Up #Dn= , 2 , 2
  4935.5    4952
   729.6  715.01
  4935.5    4952
   729.6   720.7
Abutment Skew #Up #Dn= , 2 , 2
    5048  5064.5
  719.71   729.6
    5048  5064.5
  719.16   729.6
BR Coef= 1 , 1 , 0 ,1.25, 0 ,,,0.8,0,2,0,
WSPro=,,,, 1 ,,,, 0 ,,,, 0 ,,,,-1 ,-1 ,-1 , 0 , 0 , 0 , 0 , 0
BC Design=,, 0 ,, 0 ,,,,,,
BC HTab HWMax=753.42

Type RM Length L Ch R = 1 ,1996    ,309,309,309
BEGIN DESCRIPTION:
Shacktown Rd (NDC) ds
END DESCRIPTION:
XS GIS Cut Line= 5
      1539921.31       865312.57      1539718.22       865264.87
      1539495.08       865181.77      1539350.42       865097.13
      1539114.93       864986.31
#Sta/Elev= 30
  4674.6  767.66  4785.7  755.23  4824.2  751.96  4863.8  746.51  4884.3  738.72
  4886.8  737.18  4899.8  736.24  4907.5  733.34  4920.4  726.19  4949.8  720.79
    4979  719.55  4982.5  709.35  5017.5  709.35    5021  719.55  5034.8  720.22
    5046  719.31  5075.6  718.28  5138.8  719.19    5196  724.47  5232.1  730.58
  5248.4  734.64  5286.9  739.32  5327.7  737.93  5417.9  739.34  5474.8  742.45
  5490.1  741.69  5498.7  745.16  5510.4  744.76    5518   747.1  5549.2  751.33
#Mann= 4 ,-1 , 0
  4674.6     .14       0    4979    .045       0    5021     .14       0
    5046     .14       0
#XS Ineff= 2 , 0
       0    4894   731.4    5106       0   731.4
Permanent Ineff=
       F       F
Bank Sta=4979,5021
Exp/Cntr=0.5,0.3

Type RM Length L Ch R = 1 ,1687    ,353,353,353
BEGIN DESCRIPTION:
North Deep Creek 2.0
END DESCRIPTION:
XS GIS Cut Line= 5
      1540102.92       865020.19      1539902.89       865017.11
      1539644.35       864906.31      1539367.35       864807.82
      1539053.43       864801.66
#Sta/Elev= 30
  4595.7  746.95  4669.3  742.27    4678  740.48  4704.8  739.69    4779  731.28
  4802.5  729.67  4815.8  725.51  4825.6  718.61  4844.4  717.14  4864.6  718.76
  4961.4   719.3    4962  713.75  4963.1  711.72  4972.2  711.72  4973.7  708.72
  5026.3  708.72  5027.8  711.72  5029.7  718.66  5186.2  717.75  5227.5   719.5
  5297.3  724.76  5446.7  727.45  5541.4  731.05  5553.3  734.29  5587.2   739.5
  5613.8  745.12  5625.3  746.22  5639.5  750.64    5667  750.67    5685   754.8
#Mann= 3 ,-1 , 0
  4595.7     .14       0  4972.2    .045       0  5027.8     .14       0
#XS Ineff= 2 , 0
       0                    5250       0     747
Permanent Ineff=
       F       F
Bank Sta=4972.2,5027.8
Exp/Cntr=0.5,0.3

Type RM Length L Ch R = 1 ,1334    ,145,145,145
BEGIN DESCRIPTION:
US 421 W (NDC) us
END DESCRIPTION:
XS GIS Cut Line= 4
      1540350.48       864850.35      1540009.58        864683.6
      1539320.42         864465.      1539035.11       864472.41
#Sta/Elev= 30
  4525.8  766.15  4582.5  753.59    4614  745.48  4654.8  738.44  4696.5  732.87
  4758.2     729  4793.1  727.84  4902.5  717.25  4917.9  719.88  4925.2  717.85
  4954.6   717.3  4966.5  718.44    4976   717.1    4985     709    5015     709
    5024   717.1    5036  718.07  5063.7  716.69  5111.8  718.07  5229.5  717.07
  5358.6  717.49  5743.5  723.53  5753.2  724.27  5768.4  729.68  5790.3  734.65
  5826.9  744.86  5848.2   748.5  5873.7  750.87  5890.8  750.52  5913.7  752.07
#Mann= 3 ,-1 , 0
  4525.8     .14       0    4976    .045       0    5024     .14       0
#XS Ineff= 2 , 0
       0    4818  733.69    5182       0  733.78
Permanent Ineff=
       F       F
Bank Sta=4976,5024
Exp/Cntr=0.5,0.3

Type RM Length L Ch R = 3 ,1222    ,,,
BEGIN DESCRIPTION:
US 421 W (NDC) tor
Structure ID: LDS_NDC_01
Approximate Survey Structure
END DESCRIPTION:
Bridge Culvert--1,0,-1,-1, 0
Deck Dist Width WeirC Skew NumUp NumDn MinLoCord MaxHiCord MaxSubmerge Is_Ogee
96,32,3,0, 14, 14, , , 0.95, 0, 1,1,,
  4660.3  4836.1  4900.7    4914    4914    5086    5086  5099.7    5212  5432.5
  5638.4  5737.5    5785  5879.4
  734.89  733.85   733.9   733.9   733.9   733.9   733.9   733.9  734.02  735.08
  737.18  738.72   739.8  741.25
     689     689     689     689   729.4   729.4     689     689     689     689
     689     689     689     689
  4660.3  4836.1  4900.7    4914    4914    5086    5086  5099.7    5212  5432.5
  5638.4  5737.5    5785  5879.4
  734.89  733.85   733.9   733.9   733.9   733.9   733.9   733.9  734.02  735.08
  737.18  738.72   739.8  741.25
     689     689     689     689   729.4   729.4     689     689     689     689
     689     689     689     689
Pier Skew, UpSta & Num, DnSta & Num=  ,4957, 2 ,4957, 2 , 0 , 0 , 0 ,0,0
       3       3
  717.49   729.4
       3       3
  715.23   729.4
Pier Skew, UpSta & Num, DnSta & Num=  ,5043, 2 ,5043, 2 , 0 , 0 , 0 ,0,0
       3       3
  717.82   729.4
       3       3
  717.26   729.4
Abutment Skew #Up #Dn= , 2 , 2
    4914    4938
   729.4  717.98
    4914    4938
   729.4  720.34
Abutment Skew #Up #Dn= , 2 , 2
    5062    5086
  716.81   729.4
    5062    5086
  720.31   729.4
BR Coef= 1 , 1 , 0 ,1.25, 0 ,,,0.8,0,2,0,
WSPro=,,,, 1 ,,,, 0 ,,,, 0 ,,,,-1 ,-1 ,-1 , 0 , 0 , 0 , 0 , 0
BC Design=,, 0 ,, 0 ,,,,,,
BC HTab HWMax=766.15

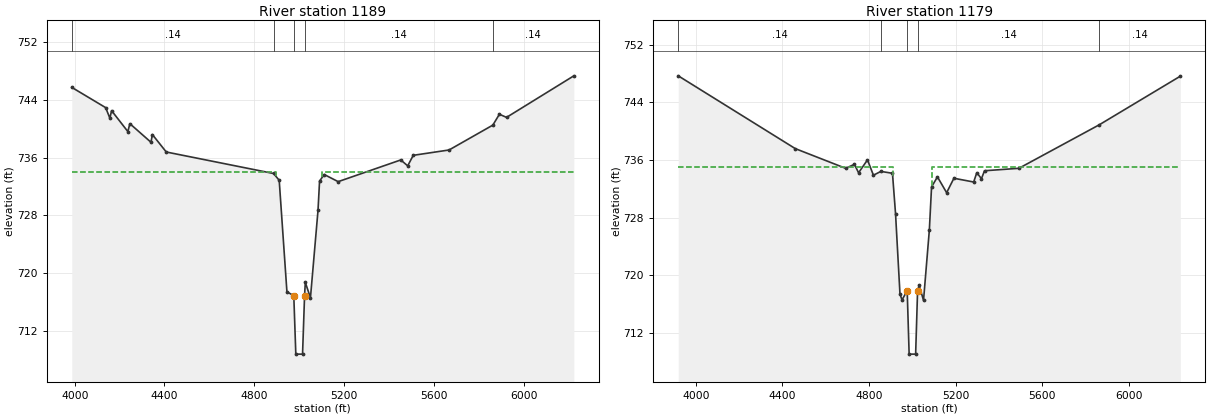
Type RM Length L Ch R = 1 ,1189    ,10,10,10
BEGIN DESCRIPTION:
US 421 W (NDC) ds
END DESCRIPTION:
XS GIS Cut Line= 4
       1540958.1       864839.22      1540091.03       864563.69
       1539805.7       864467.18      1538833.04       864141.62
#Sta/Elev= 30
  3986.9  745.73  4137.9  742.92  4156.6  741.46  4164.3   742.5  4236.8   739.6
  4245.6   740.7  4339.8  738.12    4346  739.19  4407.9  736.77  4885.8  733.79
    4911  732.85  4945.4  717.39    4976  716.85    4985  708.75    5015  708.75
    5024  716.85  5027.3  718.69  5050.2  716.56  5083.9  728.68  5090.8  732.74
  5111.5  733.65  5173.7  732.66  5452.6  735.67  5483.4  734.85  5508.2  736.31
  5667.7  737.05  5862.8   740.5  5891.9     742  5923.8  741.57  6223.6  747.33
#Mann= 5 ,-1 , 0
  3986.9     .14       0  4885.8     .14       0    4976    .045       0
    5024     .14       0  5862.8     .14       0
#XS Ineff= 2 , 0
       0    4897  733.96    5103       0  734.05
Permanent Ineff=
       F       F
Bank Sta=4976,5024
Exp/Cntr=0.5,0.3

Type RM Length L Ch R = 1 ,1179    ,128,128,128
BEGIN DESCRIPTION:
US 421 E (NDC) us
END DESCRIPTION:
XS GIS Cut Line= 5
       1541032.2       864831.81      1540108.41       864557.69
      1539896.82       864489.36      1539070.08       864211.86
      1538822.77       864131.37
#Sta/Elev= 30
  3918.9  747.68  4459.3  737.59  4691.7  734.86  4732.4  735.41  4751.5  734.24
  4792.7  736.03  4820.1   733.9  4854.4  734.43    4908  734.17  4922.2  728.57
  4942.7  717.43  4952.1  716.61    4976   717.9    4985   709.1    5015   709.1
    5024   717.9  5031.4  718.64  5051.4  716.55  5078.4  726.35  5088.5  732.28
  5115.7  733.67  5158.1  731.48  5191.7  733.48    5283  732.96  5297.3  734.25
  5318.8  733.42    5333  734.52  5491.8  734.86  5862.7  740.89    6237  747.63
#Mann= 5 ,-1 , 0
  3918.9     .14       0  4854.4     .14       0    4976    .045       0
    5024     .14       0  5862.7     .14       0
#XS Ineff= 2 , 0
       0    4910     735    5090       0     735
Permanent Ineff=
       F       F
Bank Sta=4976,5024
Exp/Cntr=0.5,0.3