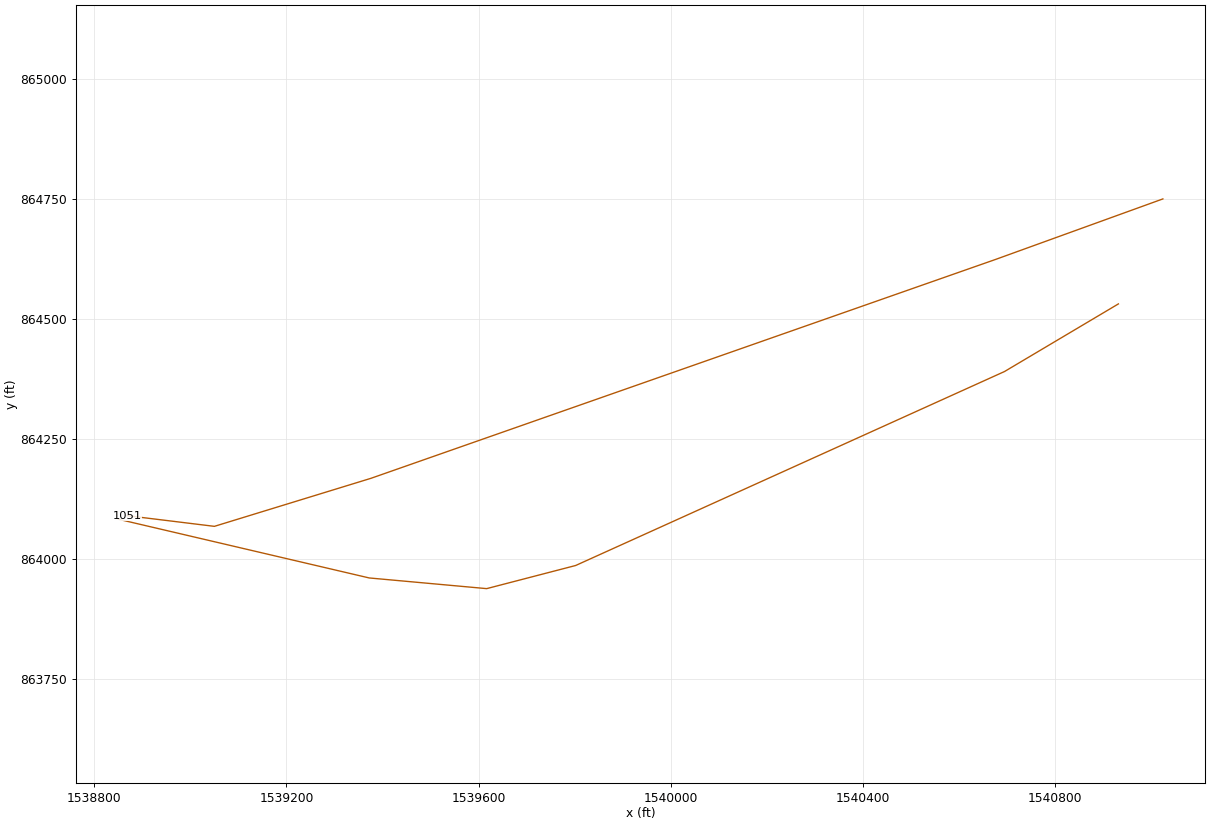
HEC-RAS study North Deep Creek.prj: North Deep Creek Limited Detail Study

--- North Deep Creek.g01 (geometry) --- (continued)

Type RM Length L Ch R = 3 ,1150    ,,,
BEGIN DESCRIPTION:
US 421 E (NDC) tor
Structure ID: LDS_NDC_01A
Approximate Survey Structure
END DESCRIPTION:
Bridge Culvert--1,0,-1,-1, 0
Deck Dist Width WeirC Skew NumUp NumDn MinLoCord MaxHiCord MaxSubmerge Is_Ogee
9,40,3,0, 16, 16, , , 0.95, 0, 1,1,,
  4144.9  4291.9  4429.8  4570.9  4732.2  4894.4    4919    4919    5081    5081
  5368.1  5453.3    5657  5857.5  6173.2  6260.2
  743.31  740.42  738.54  736.92  735.53     735     735     735     735     735
     735  735.67  737.83  741.04  746.75  748.63
   689.1   689.1   689.1   689.1   689.1   689.1   689.1   730.5   730.5   689.1
   689.1   689.1   689.1   689.1   689.1   689.1
  4144.9  4291.9  4429.8  4570.9  4732.2  4894.4    4919    4919    5081    5081
  5368.1  5453.3    5657  5857.5  6173.2  6260.2
  743.31  740.42  738.54  736.92  735.53     735     735     735     735     735
     735  735.67  737.83  741.04  746.75  748.63
   689.1   689.1   689.1   689.1   689.1   689.1   689.1   730.5   730.5   689.1
   689.1   689.1   689.1   689.1   689.1   689.1
Pier Skew, UpSta & Num, DnSta & Num=  ,4959.5, 2 ,4959.5, 2 , 0 , 0 , 0 ,0,0
       3       3
  714.97   730.5
       3       3
  714.86   730.5
Pier Skew, UpSta & Num, DnSta & Num=  ,5040.5, 2 ,5040.5, 2 , 0 , 0 , 0 ,0,0
       3       3
  717.62   730.5
       3       3
  718.19   730.5
Abutment Skew #Up #Dn= , 2 , 2
    4919    4938
   730.5  719.69
    4919    4938
   730.5   716.9
Abutment Skew #Up #Dn= , 2 , 2
    5062    5081
  720.36   730.5
    5062    5081
  717.27   730.5
BR Coef= 1 , 1 , 0 ,1.25, 0 ,,,0.8,0,2,0,
WSPro=,,,, 1 ,,,, 0 ,,,, 0 ,,,,-1 ,-1 ,-1 , 0 , 0 , 0 , 0 , 0
BC Design=,, 0 ,, 0 ,,,,,,
BC HTab HWMax=747.68

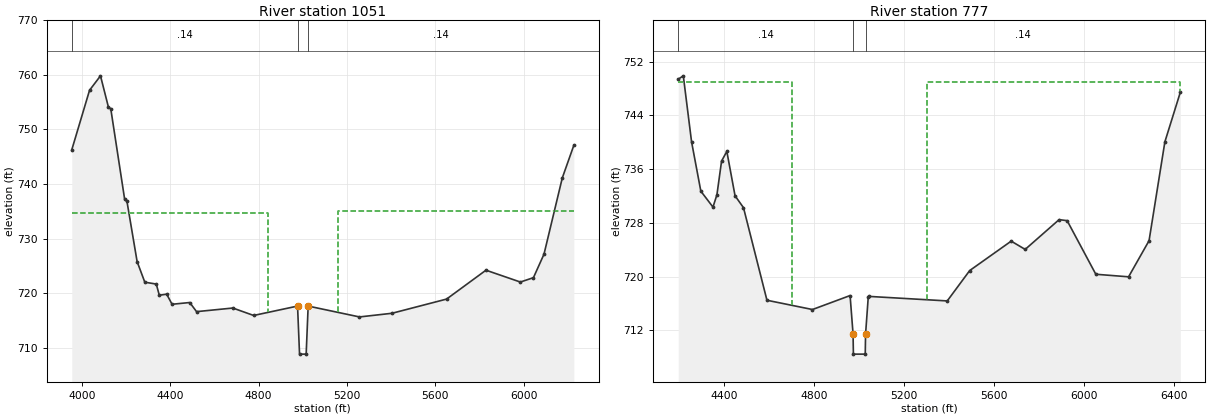
Type RM Length L Ch R = 1 ,1051    ,274,274,274
BEGIN DESCRIPTION:
US 421 E (NDC) ds
END DESCRIPTION:
XS GIS Cut Line= 5
      1541024.79        864750.3      1540676.51       864624.32
        1539376.       864168.59      1539049.94       864068.55
      1538868.37       864090.78
#Sta/Elev= 30
  3954.1  746.26  4034.6  757.17  4084.1  759.81  4120.3  754.03  4130.5  753.81
  4193.5  737.19  4203.8  736.84  4249.9  725.79  4284.7  722.02  4336.6  721.68
  4350.3  719.63  4383.7  719.83    4408  717.98    4488   718.3  4518.9  716.63
  4683.2  717.29  4777.3  715.93    4976  717.65    4985  708.85    5015  708.85
    5024  717.65  5256.2  715.66  5403.4  716.33  5650.5  718.93  5828.8  724.22
  5984.4  722.05  6043.6  722.85  6091.4  727.15  6174.2  741.11  6226.5  747.09
#Mann= 3 ,-1 , 0
  3954.1     .14       0    4976    .045       0    5024     .14       0
#XS Ineff= 2 , 0
       0    4840  734.78    5160       0     735
Permanent Ineff=
       F       F
Bank Sta=4976,5024
Exp/Cntr=0.5,0.3

Type RM Length L Ch R = 1 ,777     ,0,0,0
BEGIN DESCRIPTION:
North Deep Creek 1.0
END DESCRIPTION:
XS GIS Cut Line= 6
      1540932.17        864531.7      1540695.04        864390.9
      1539802.09       863987.03      1539616.83       863938.87
      1539372.29        863961.1      1538849.89       864083.36
#Sta/Elev= 30
  4195.6  749.38  4218.1  749.88  4254.8  740.06    4296  732.71  4349.9  730.34
  4367.5  732.18  4388.1  737.19  4411.5  738.63    4448  732.02  4485.5  730.25
  4589.7  716.47  4791.9  715.09    4959  717.17  4972.2  711.45  4973.7  708.45
  5026.3  708.45  5027.8  711.45  5039.6  716.91  5044.7  717.04  5390.6  716.37
  5490.3  720.89  5674.6  725.27  5736.8  724.04  5887.4  728.47  5923.2  728.32
  6050.6  720.34  6196.1  719.96  6287.1  725.34  6357.4  740.06  6425.9  747.43
#Mann= 3 ,-1 , 0
  4195.6     .14       0  4972.2    .045       0  5027.8     .14       0
#XS Ineff= 2 , 0
       0    4700     749    5300       0     749
Permanent Ineff=
       F       F
Bank Sta=4972.2,5027.8
Exp/Cntr=0.3,0.1

Chan Stop Cuts=-1
Use User Specified Reach Order=0
User Specified Reach Order=North Deep Creek,Reach-1